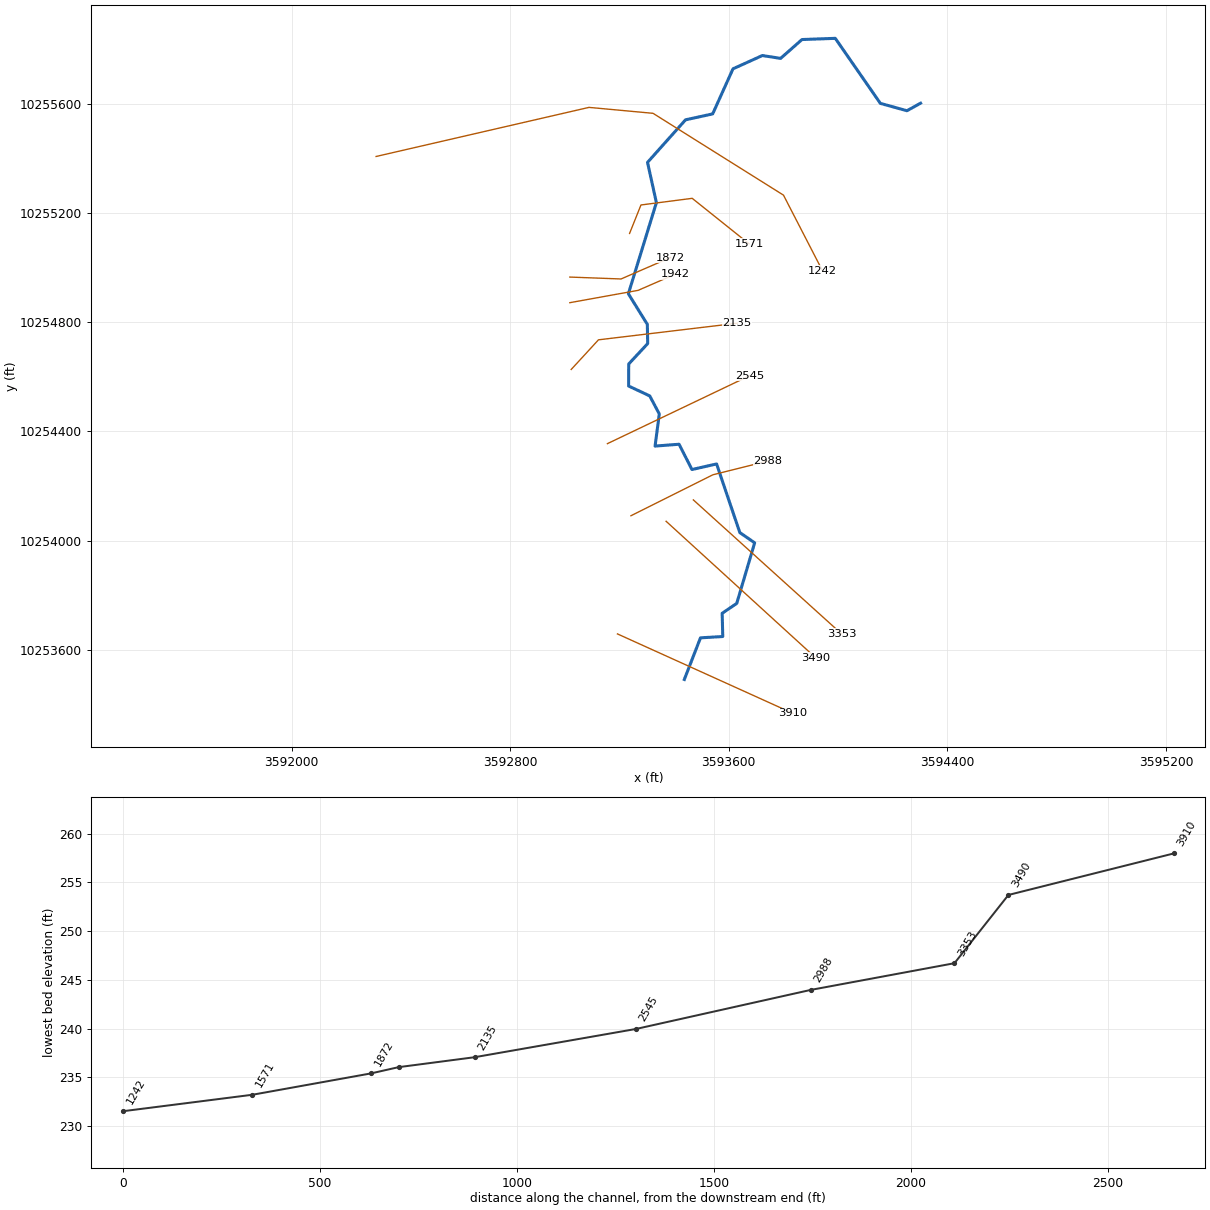
--- BOWMANCREEKTRIB2.prj (project) ---

Proj Title=BOWMAN CREEK TRIB 2
Current Plan=p01
Default Exp/Contr=0.3,0.1
English Units
Geom File=g01
Flow File=f01
Plan File=p01
Y Axis Title=Elevation
X Axis Title(PF)=Main Channel Distance
X Axis Title(XS)=Station
BEGIN DESCRIPTION:
UNT04976 IN WICK
END DESCRIPTION:
DSS Export Rating Curves= 0
DSS Export Rating Curve Sorted= 0
DSS Export Volume Flow Curves= 0
DXF OffsetX= 0
DXF OffsetY= 0
DXF ScaleX= 1
DXF ScaleY= 10

--- BOWMANCREEKTRIB2.p01 (plan) ---

Plan Title=Multiple Run
Short Identifier=Multiple
Geom File=g01
Flow File=f01
Subcritical Flow
K Sum by GR= 0
Std Step Tol= 0.01
Critical Tol= 0.01
Num of Std Step Trials= 20
Max Error Tol= 0.3
Flow Tol Ratio= 0.001
Split Flow NTrial= 30
Split Flow Tol= 0.02
Split Flow Ratio= 0.02
Log Output Level= 0
Friction Slope Method= 1
Unsteady Friction Slope Method= 2
Unsteady Bridges Friction Slope Method= 1
Parabolic Critical Depth
Global Vel Dist=  1 , 1 , 1
Global Log Level= 0
CheckData=True
Encroach Param= -1, 0, 0, 0
BEGIN DESCRIPTION:
Multiple Run
END DESCRIPTION:

--- BOWMANCREEKTRIB2.f01 (steady flow) ---

Flow Title=Multiple
Program Version=4.10
Number of Profiles= 7
Profile Names=10-year,25-year,50-year,1pct_min,100-year,1pct_plu,500-year
River Rch & RM=UNT04976 IN WICK,Reach-1         ,3910
     207     261     302     258     349     471     463
River Rch & RM=UNT04976 IN WICK,Reach-1         ,1242
     307     398     470     407     551     745     758
River Rch & RM=BOWMANCRTRIB2,Reach-1         ,3910
     207     261     302     258     349     471     463
River Rch & RM=BOWMANCRTRIB2,Reach-1         ,1242
     307     398     470     407     551     745     758
Boundary for River Rch & Prof#=BOWMANCRTRIB2,Reach-1         , 1
Up Type= 0
Dn Type= 3
Dn Slope=0.005
Boundary for River Rch & Prof#=BOWMANCRTRIB2,Reach-1         , 2
Up Type= 0
Dn Type= 3
Dn Slope=0.005
Boundary for River Rch & Prof#=BOWMANCRTRIB2,Reach-1         , 3
Up Type= 0
Dn Type= 3
Dn Slope=0.005
Boundary for River Rch & Prof#=BOWMANCRTRIB2,Reach-1         , 4
Up Type= 0
Dn Type= 3
Dn Slope=0.005
Boundary for River Rch & Prof#=BOWMANCRTRIB2,Reach-1         , 5
Up Type= 0
Dn Type= 3
Dn Slope=0.005
Boundary for River Rch & Prof#=BOWMANCRTRIB2,Reach-1         , 6
Up Type= 0
Dn Type= 3
Dn Slope=0.005
Boundary for River Rch & Prof#=BOWMANCRTRIB2,Reach-1         , 7
Up Type= 0
Dn Type= 3
Dn Slope=0.005
DSS Import GetInterval= 0
DSS Import GetPeak= 0
DSS Import FillOption= 0

--- BOWMANCREEKTRIB2.g01 (geometry) ---

Geom Title=Existing Conditions
Program Version=4.10

River Reach=BOWMANCRTRIB2   ,Reach-1
Reach XY= 30
      3593437.43     10253492.44      3593496.58     10253644.79
       3593578.1     10253649.59      3593575.95     10253734.63
      3593629.22     10253770.74      3593694.86     10253992.61
       3593640.6     10254029.94      3593555.53     10254281.24
      3593465.35     10254260.79      3593418.23      10254353.3
      3593330.38     10254346.66      3593345.82     10254464.29
      3593310.81     10254530.27      3593233.49      10254566.4
      3593233.92     10254647.13      3593303.36     10254721.78
      3593302.06     10254792.09      3593232.62     10254904.07
      3593335.21     10255237.69      3593302.74     10255384.98
      3593441.87     10255540.72      3593541.19     10255562.42
      3593615.59     10255727.38      3593723.15     10255776.07
      3593789.72     10255765.51      3593868.15     10255834.56
      3593989.93     10255838.97      3594154.94     10255600.95
       3594252.2     10255573.96      3594302.11     10255601.64

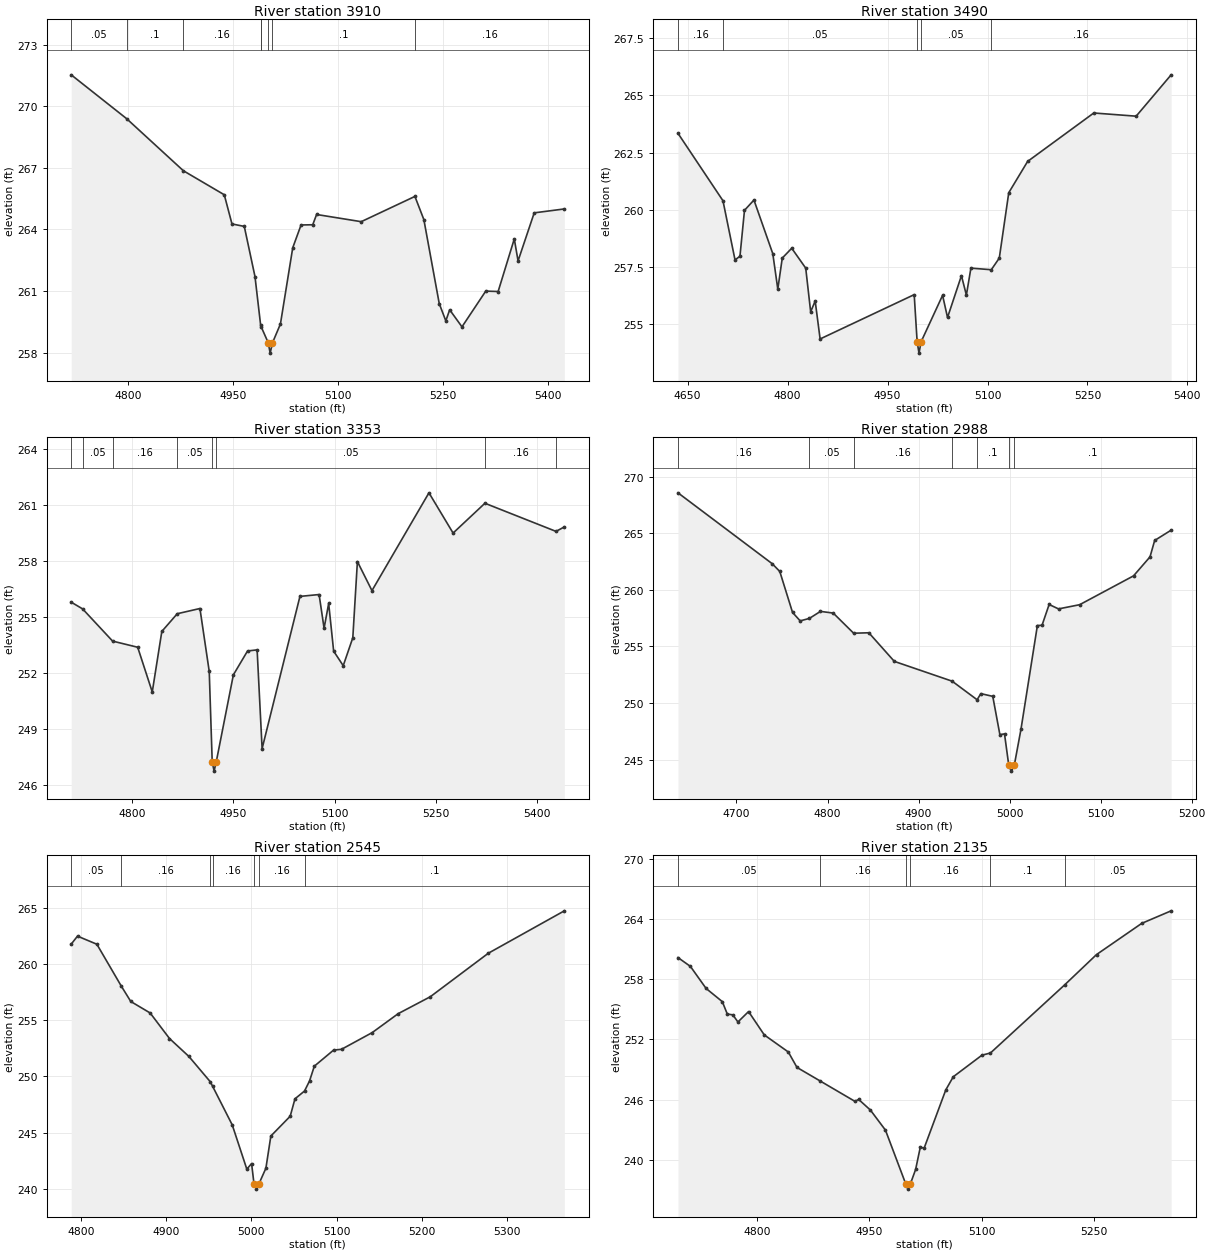
Type RM Length L Ch R = 1 ,3910    ,420,420,420
BEGIN DESCRIPTION:
UNT04976 IN WICK 7.0
END DESCRIPTION:
XS GIS Cut Line= 2
      3593192.69     10253659.17      3593835.12     10253368.34
#Sta/Elev= 30
  4718.1  271.53  4797.2   269.4  4878.5  266.86    4937  265.69    4948  264.27
  4965.6  264.15  4980.9  261.71  4988.9  259.37  4989.8  259.26  4999.9  258.48
  5002.6  257.98  5005.9  258.48  5017.3   259.4  5034.9  263.11  5046.8  264.22
  5063.5  264.23    5069  264.73  5132.8  264.38  5209.6  265.61  5222.4  264.48
  5244.4  260.39  5253.8  259.55  5259.3  260.09  5276.9  259.26  5310.9     261
  5328.6  260.98  5351.7  263.54  5357.1  262.47  5380.2  264.81  5423.3     265
#Mann= 8 ,-1 , 0
  4718.1     .05       0  4797.2      .1       0  4878.5     .16       0
  4988.9     .05       0  4989.8      .1       0  4999.9     .07       0
  5005.9      .1       0  5209.6     .16       0
Bank Sta=4999.9,5005.9
XS Rating Curve= 0 ,0
Exp/Cntr=0.3,0.1

Type RM Length L Ch R = 1 ,3490    ,137,137,137
BEGIN DESCRIPTION:
UNT04976 IN WICK 6.0
END DESCRIPTION:
XS GIS Cut Line= 2
       3593370.7     10254071.45      3593917.35     10253572.53
#Sta/Elev= 30
  4635.5  263.34    4703  260.39  4721.1   257.8  4728.5  257.96  4735.3  259.97
  4749.5  260.42  4777.8  258.07  4785.3  256.52    4792  257.88  4806.2  258.31
  4827.2  257.44  4834.6  255.53  4841.4     256  4848.8  254.34    4990  256.28
  4994.4  254.22  4997.2  253.72  5000.4  254.22  5032.6  256.25    5040  255.28
  5060.9  257.11  5068.3  256.26  5075.1  257.44  5105.7  257.37  5117.7  257.88
  5131.9  260.74  5160.2  262.11  5259.5  264.23  5323.1  264.09  5375.6   265.9
#Mann= 5 ,-1 , 0
  4635.5     .16       0    4703     .05       0  4994.4     .03       0
  5000.4     .05       0  5105.7     .16       0
Bank Sta=4994.4,5000.4
XS Rating Curve= 0 ,0
Exp/Cntr=0.3,0.1

Type RM Length L Ch R = 1 ,3353    ,365,365,365
BEGIN DESCRIPTION:
Mapping XS 989349fd
END DESCRIPTION:
XS GIS Cut Line= 2
       3593470.5      10254149.6      3594012.99     10253659.19
#Sta/Elev= 30
  4709.5  255.79  4726.4  255.43  4770.9   253.7  4808.1  253.37  4829.7  250.97
  4843.9  254.22  4866.8  255.17  4900.4  255.45  4914.2  252.07  4918.6  247.22
  4921.4  246.72  4924.6  247.22    4950  251.89    4971  253.17  4985.2  253.23
  4992.6  247.93  5048.7   256.1  5077.1   256.2  5084.5  254.39  5091.3  255.72
  5098.7  253.16  5112.9  252.38  5127.1  253.88  5133.9  257.97  5155.5  256.41
    5240  261.66  5275.8   259.5    5323   261.1  5428.4  259.59  5440.8  259.83
#Mann= 8 ,-1 , 0
  4709.5     .16       0  4726.4     .05       0  4770.9     .16       0
  4866.8     .05       0  4918.6     .03       0  4924.6     .05       0
    5323     .16       0  5428.4     .05       0
Bank Sta=4918.6,4924.6
XS Rating Curve= 0 ,0
Exp/Cntr=0.3,0.1

Type RM Length L Ch R = 1 ,2988    ,443,443,443
BEGIN DESCRIPTION:
UNT04976 IN WICK 5.0
END DESCRIPTION:
XS GIS Cut Line= 3
      3593242.09     10254091.64      3593542.11     10254241.64
      3593742.13     10254291.65
#Sta/Elev= 30
  4635.8  268.58  4739.2  262.32  4747.6  261.63  4761.6  258.01    4770  257.26
  4780.1  257.48  4792.3   258.1  4806.3  257.95  4828.7  256.17  4845.4  256.21
  4873.4  253.68  4936.9  251.93  4964.3  250.29  4968.4  250.83  4981.5  250.59
  4989.3  247.21  4994.4  247.27  4999.1  244.48  5001.9  243.98  5005.1  244.48
  5012.5  247.69  5030.5  256.85  5035.6  256.87  5043.4  258.71  5053.7  258.32
  5076.9  258.69  5136.1  261.24  5154.2  262.92  5159.3  264.37  5177.4  265.28
#Mann= 7 ,-1 , 0
  4635.8     .16       0  4780.1     .05       0  4828.7     .16       0
  4936.9     .05       0  4964.3      .1       0  4999.1     .07       0
  5005.1      .1       0
Bank Sta=4999.1,5005.1
XS Rating Curve= 0 ,0
Exp/Cntr=0.3,0.1

Type RM Length L Ch R = 1 ,2545    ,410,410,410
BEGIN DESCRIPTION:
UNT04976 IN WICK 4.0
END DESCRIPTION:
XS GIS Cut Line= 2
      3593155.99     10254355.55      3593677.97     10254604.93
#Sta/Elev= 30
  4788.7  261.76  4796.1  262.47  4818.8  261.75  4847.6  258.01  4858.6  256.66
  4881.3  255.64    4904  253.37  4926.7  251.78  4951.9  249.52  4954.6  249.12
  4977.6  245.69  4994.7  241.76  5000.3  242.25  5003.1  240.48  5005.8  239.98
  5009.1  240.48  5017.1  241.84  5022.9   244.7  5045.6  246.46  5051.2  248.01
  5062.4   248.7  5068.3   249.6  5073.9  250.91  5096.5  252.34  5105.8  252.41
  5141.9   253.9  5172.3  255.58  5209.9  257.08    5278  260.95  5367.2  264.72
#Mann= 7 ,-1 , 0
  4788.7     .05       0  4847.6     .16       0  4951.9     .05       0
  4954.6     .16       0  5003.1     .07       0  5009.1     .16       0
  5062.4      .1       0
Bank Sta=5003.1,5009.1
XS Rating Curve= 0 ,0
Exp/Cntr=0.3,0.1

Type RM Length L Ch R = 1 ,2135    ,193,193,193
BEGIN DESCRIPTION:
UNT04976 IN WICK 3.0
END DESCRIPTION:
XS GIS Cut Line= 3
      3593023.44     10254627.03      3593123.28     10254735.54
       3593631.1     10254796.31
#Sta/Elev= 30
  4694.4  260.16    4711  259.28    4732  257.08  4753.6  255.77  4760.3  254.53
  4767.7  254.45  4774.5  253.74  4788.7  254.78  4809.7  252.45  4841.8  250.75
  4853.4  249.21  4883.9  247.88  4930.8  245.83  4935.8  246.02  4951.5  244.96
  4971.6  242.96  4998.8  237.58  5001.6  237.08  5004.8  237.58  5011.9  239.04
  5018.2  241.28  5023.2  241.15  5052.2  246.97  5062.2  248.28  5100.5  250.43
  5111.9  250.65  5210.9  257.43  5253.6  260.46    5314  263.57  5353.3  264.82
#Mann= 6 ,-1 , 0
  4694.4     .05       0  4883.9     .16       0  4998.8     .07       0
  5004.8     .16       0  5111.9      .1       0  5210.9     .05       0
Bank Sta=4998.8,5004.8
XS Rating Curve= 0 ,0
Exp/Cntr=0.3,0.1

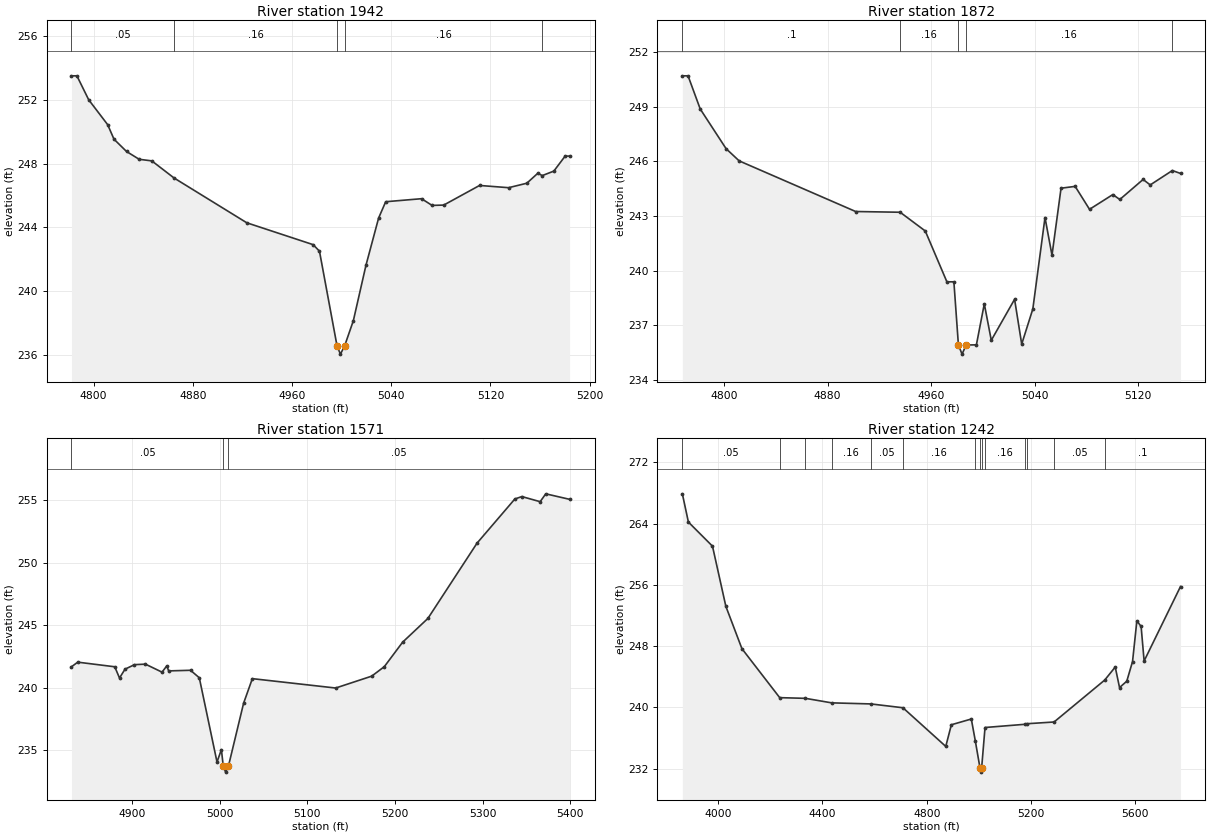
Type RM Length L Ch R = 1 ,1942    ,70,70,70
BEGIN DESCRIPTION:
Mapping XS f72865eb
END DESCRIPTION:
XS GIS Cut Line= 3
      3593018.38     10254871.46      3593268.33     10254916.59
      3593403.73     10254975.61
#Sta/Elev= 30
  4782.1   253.5  4786.5   253.5    4796     252  4811.3  250.44  4816.4  249.53
  4826.5  248.76  4836.7  248.27  4846.9  248.17  4864.8   247.1  4923.5  244.29
    4977  242.92  4982.1  242.51  4996.3  236.56    4999  236.06  5002.3  236.56
  5009.4  238.15  5019.6  241.63  5029.8  244.59  5035.5  245.61  5064.4   245.8
  5072.9  245.38  5082.3   245.4  5111.2  246.63  5134.6  246.49  5149.3  246.77
  5158.1  247.39  5161.8  247.25  5171.1  247.53  5180.2  248.47  5183.8  248.47
#Mann= 5 ,-1 , 0
  4782.1     .05       0  4864.8     .16       0  4996.3     .07       0
  5002.3     .16       0  5161.8      .1       0
Bank Sta=4996.3,5002.3
XS Rating Curve= 0 ,0
Exp/Cntr=0.3,0.1

Type RM Length L Ch R = 1 ,1872    ,301,301,301
BEGIN DESCRIPTION:
Mapping XS e7b670d6
END DESCRIPTION:
XS GIS Cut Line= 3
      3593018.28      10254965.2      3593205.83     10254958.25
      3593386.75     10255036.77
#Sta/Elev= 30
  4767.8   250.7  4772.2   250.7  4781.6  248.88  4801.6   246.7  4811.7  246.03
  4901.7  243.25  4936.1  243.21  4955.5  242.18  4972.2  239.39  4977.6  239.39
  4981.1  235.92  4983.9  235.42  4987.1  235.92    4995  235.93  5001.1  238.18
  5006.5  236.18  5024.5  238.43    5030  235.97  5038.6   237.9    5048  242.92
  5053.4  240.85  5060.4  244.53  5071.3  244.63  5082.4  243.37  5100.4  244.18
  5105.8  243.91  5123.8  245.01  5129.3  244.71  5146.4   245.5  5152.7  245.34
#Mann= 5 ,-1 , 0
  4767.8      .1       0  4936.1     .16       0  4981.1     .07       0
  4987.1     .16       0  5146.4     .05       0
Bank Sta=4981.1,4987.1
XS Rating Curve= 0 ,0
Exp/Cntr=0.3,0.1

Type RM Length L Ch R = 1 ,1571    ,329,329,329
BEGIN DESCRIPTION:
UNT04976 IN WICK 2.0
END DESCRIPTION:
XS GIS Cut Line= 4
      3593237.08     10255124.91      3593278.75     10255229.09
      3593466.25     10255253.39       3593674.6     10255086.71
#Sta/Elev= 30
  4831.1  241.66  4838.3  242.03  4880.5  241.66  4885.9  240.76  4892.2  241.47
    4903  241.83  4915.5  241.87  4934.4  241.23  4939.8  241.73    4942  241.33
  4966.9  241.38  4976.9  240.78  4997.1  234.04  5002.1  235.03  5004.2  233.73
  5006.9  233.23  5010.2  233.73  5027.4  238.74  5037.4  240.71  5132.4  239.96
  5173.5  240.91  5187.9  241.67  5208.8  243.63  5237.6  245.53  5293.6  251.55
  5336.8  255.09  5344.8  255.28  5365.6  254.87    5372   255.5  5399.2  255.06
#Mann= 3 ,-1 , 0
  4831.1     .05       0  5004.2     .03       0  5010.2     .05       0
Bank Sta=5004.2,5010.2
XS Rating Curve= 0 ,0
Exp/Cntr=0.3,0.1

Type RM Length L Ch R = 1 ,1242    ,0,0,0
BEGIN DESCRIPTION:
UNT04976 IN WICK 1.0
END DESCRIPTION:
XS GIS Cut Line= 5
      3592309.45     10255406.58      3593088.55     10255586.24
      3593322.93     10255564.54      3593800.36     10255265.06
      3593943.57     10254987.32
#Sta/Elev= 30
  3862.4   267.9  3885.6  264.21    3978  261.06  4029.3   253.2  4090.9  247.67
  4235.9  241.27  4334.7  241.18  4435.1  240.59  4585.6  240.45  4708.6  239.95
  4872.9   234.9  4894.4  237.73  4970.9  238.48    4986  235.67  5004.4  232.04
  5007.1  231.54  5010.4  232.04  5023.5  237.37  5176.9  237.79  5183.4  237.86
  5288.4  238.09  5482.7  243.57    5523  245.27  5539.5  242.59  5567.3  243.42
  5589.4  245.99    5606  251.31  5622.3  250.57  5633.8  246.06  5773.4  255.79
#Mann= 14 ,-1 , 0
  3862.4     .05       0  4235.9     .16       0  4334.7     .05       0
  4435.1     .16       0  4585.6     .05       0  4708.6     .16       0
    4986     .05       0  5004.4    .035       0  5010.4     .05       0
  5023.5     .16       0  5176.9     .05       0  5183.4     .16       0
  5288.4     .05       0  5482.7      .1       0
Bank Sta=5004.4,5010.4
XS Rating Curve= 0 ,0
Exp/Cntr=0.3,0.1

Chan Stop Cuts=-1
Use User Specified Reach Order=0
Composite Channel Slope=5