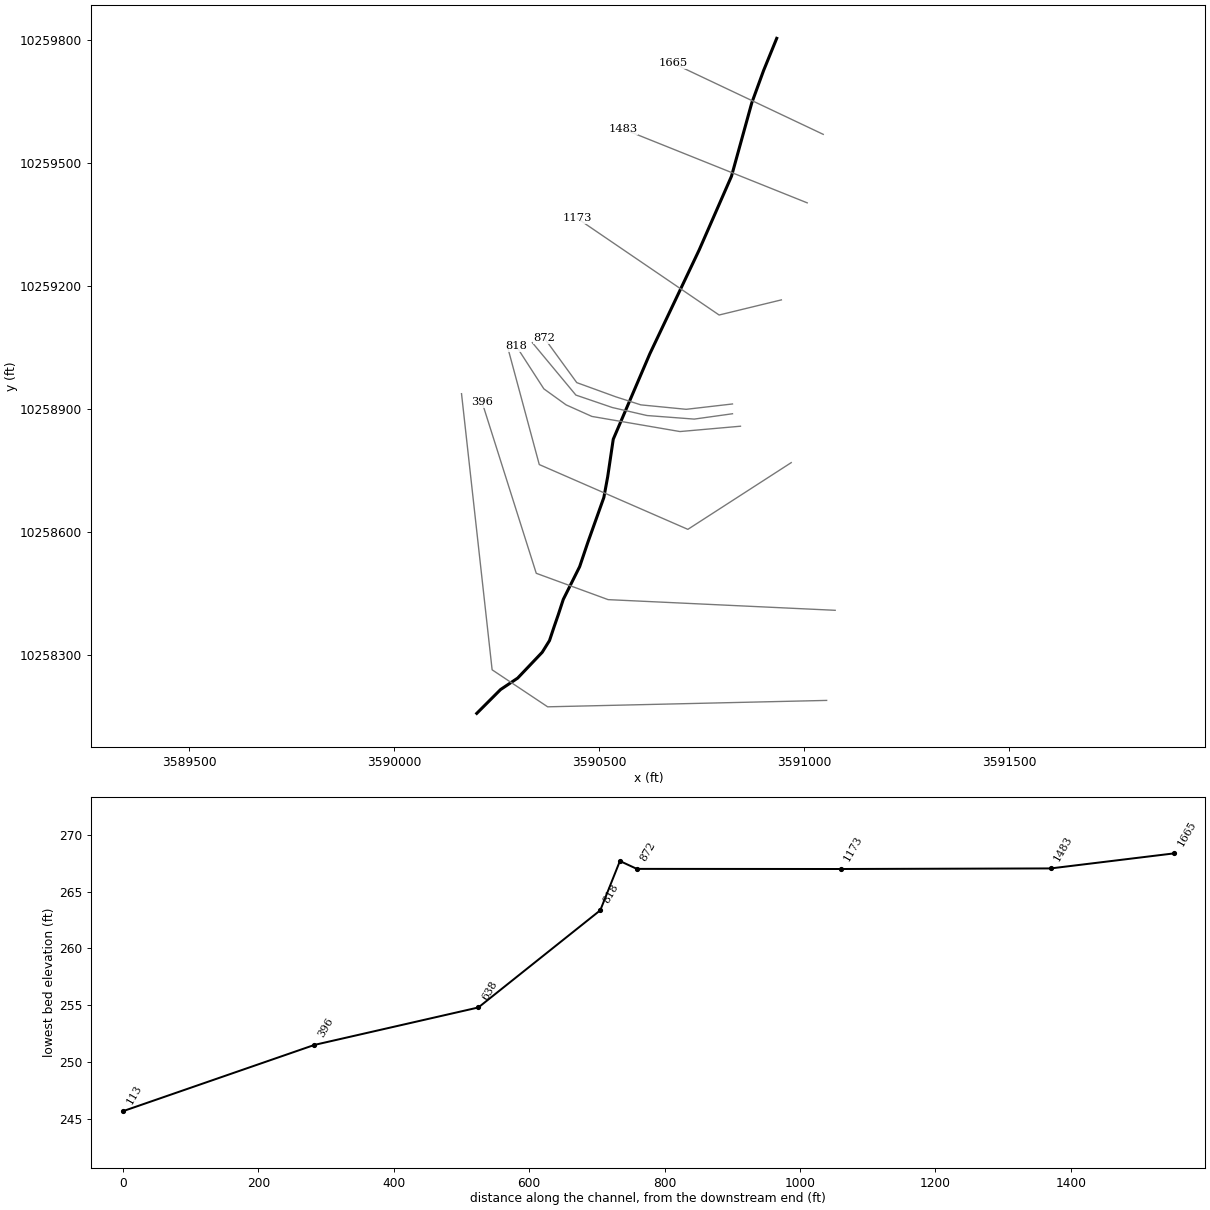
--- BOWMANCRTRIB41.prj (project) ---

Proj Title=BOWMAN CREEK TRIB 4 1
Current Plan=p01
Default Exp/Contr=0.3,0.1
English Units
Geom File=g01
Flow File=f01
Plan File=p01
Y Axis Title=Elevation
X Axis Title(PF)=Main Channel Distance
X Axis Title(XS)=Station
BEGIN DESCRIPTION:
UNT999 IN WICK
END DESCRIPTION:
DSS Export Rating Curves= 0
DSS Export Rating Curve Sorted= 0
DSS Export Volume Flow Curves= 0
DXF Filename=UNT999 IN WICK.
DXF OffsetX= 0
DXF OffsetY= 0
DXF ScaleX= 1
DXF ScaleY= 10

--- BOWMANCRTRIB41.p01 (plan) ---

Plan Title=Multiple Run
Short Identifier=Multiple
Geom File=g01
Flow File=f01
Subcritical Flow
K Sum by GR= 0
Std Step Tol= 0.01
Critical Tol= 0.01
Num of Std Step Trials= 20
Max Error Tol= 0.3
Flow Tol Ratio= 0.001
Split Flow NTrial= 30
Split Flow Tol= 0.02
Split Flow Ratio= 0.02
Log Output Level= 0
Friction Slope Method= 1
Unsteady Friction Slope Method= 2
Unsteady Bridges Friction Slope Method= 1
Parabolic Critical Depth
Global Vel Dist=  1 , 1 , 1
Global Log Level= 0
CheckData=True
Encroach Param= -1, 0, 0, 0
BEGIN DESCRIPTION:
Multiple Run
END DESCRIPTION:

--- BOWMANCRTRIB41.f01 (steady flow) ---

Flow Title=Multiple
Program Version=4.10
Number of Profiles= 7
Profile Names=10-year,25-year,50-year,1pct_min,100-year,1pct_plu,500-year
River Rch & RM=UNT999 IN WICK,Reach-1         ,1665
      85     100     111      91     123     166     150
River Rch & RM=BOWMANCRTRIB41,Reach-1         ,1665
      85     100     111      91     123     166     150
Boundary for River Rch & Prof#=BOWMANCRTRIB41,Reach-1         , 1
Up Type= 0
Dn Type= 3
Dn Slope=0.005
Boundary for River Rch & Prof#=BOWMANCRTRIB41,Reach-1         , 2
Up Type= 0
Dn Type= 3
Dn Slope=0.005
Boundary for River Rch & Prof#=BOWMANCRTRIB41,Reach-1         , 3
Up Type= 0
Dn Type= 3
Dn Slope=0.005
Boundary for River Rch & Prof#=BOWMANCRTRIB41,Reach-1         , 4
Up Type= 0
Dn Type= 3
Dn Slope=0.005
Boundary for River Rch & Prof#=BOWMANCRTRIB41,Reach-1         , 5
Up Type= 0
Dn Type= 3
Dn Slope=0.005
Boundary for River Rch & Prof#=BOWMANCRTRIB41,Reach-1         , 6
Up Type= 0
Dn Type= 3
Dn Slope=0.005
Boundary for River Rch & Prof#=BOWMANCRTRIB41,Reach-1         , 7
Up Type= 0
Dn Type= 3
Dn Slope=0.005
DSS Import GetInterval= 0
DSS Import GetPeak= 0
DSS Import FillOption= 0

--- BOWMANCRTRIB41.g01 (geometry) ---

Geom Title=Existing Conditions
Program Version=4.10

River Reach=BOWMANCRTRIB41  ,Reach-1
Reach XY= 19
      3590933.12     10259803.42      3590901.02     10259724.77
      3590872.23     10259645.87      3590822.77     10259467.05
      3590743.95     10259287.22      3590623.64     10259034.03
      3590534.35     10258825.46      3590520.81     10258734.14
      3590511.44     10258683.45       3590472.2     10258573.38
      3590452.41      10258514.7      3590412.48     10258434.84
      3590400.32     10258397.68      3590389.66     10258366.82
      3590378.85     10258334.39      3590361.09     10258305.84
      3590301.19     10258242.82      3590259.39     10258214.83
      3590201.39     10258156.78

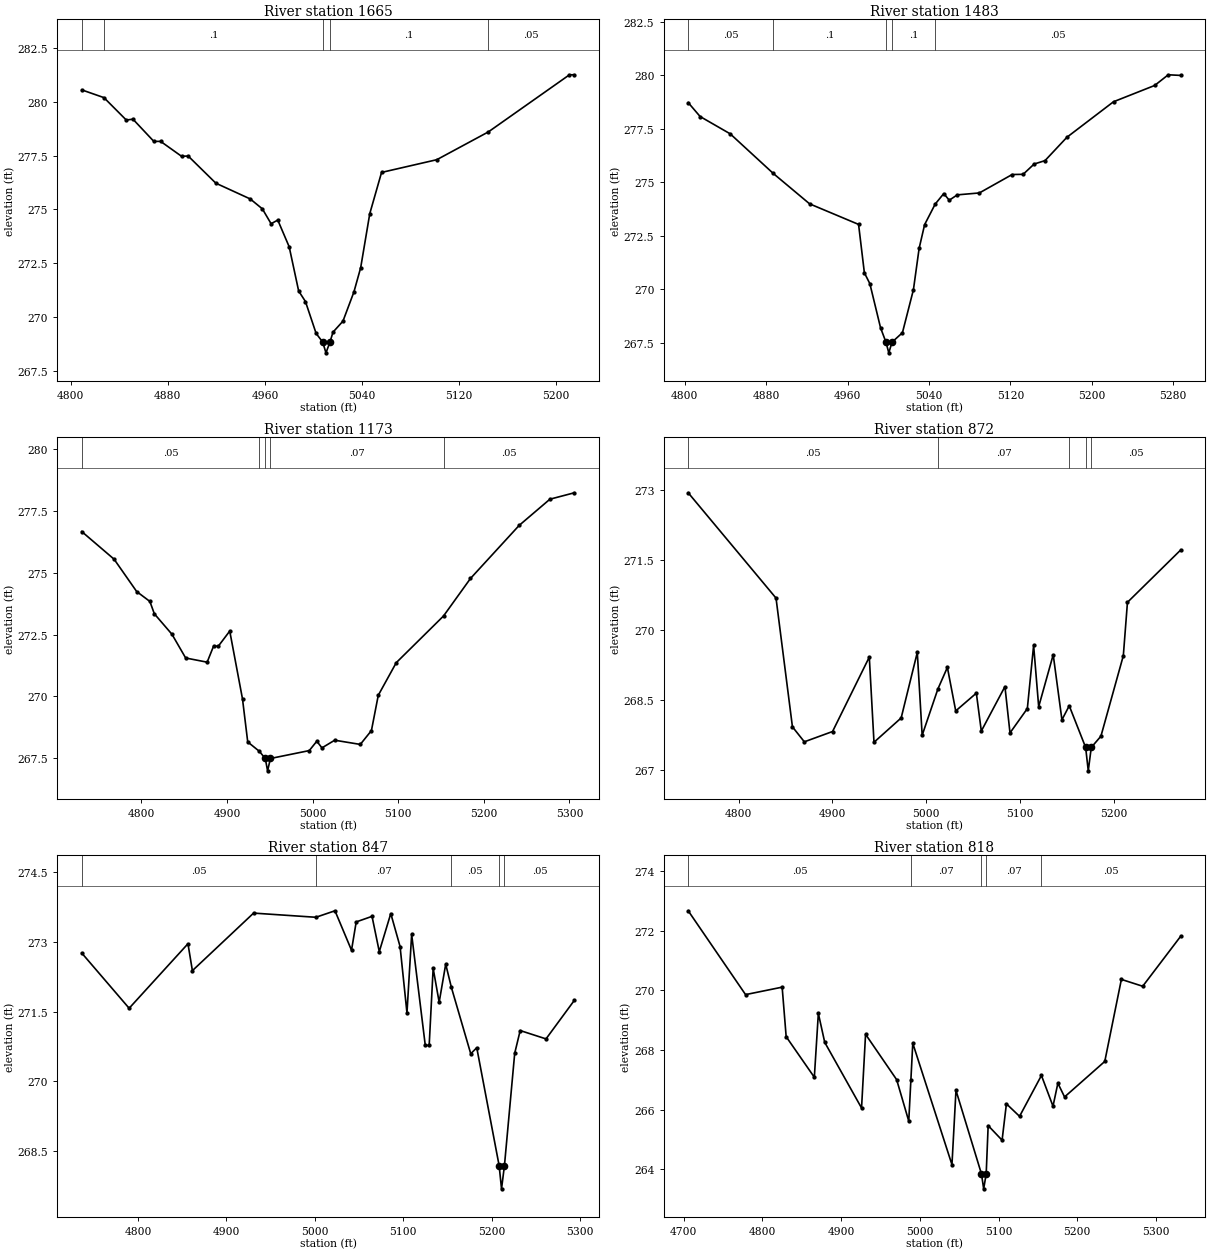
Type RM Length L Ch R = 1 ,1665    ,182,182,182
BEGIN DESCRIPTION:
UNT999 IN WICK 4.0
END DESCRIPTION:
XS GIS Cut Line= 2
       3591046.6      10259569.2      3590679.82     10259742.82
#Sta/Elev= 30
  4809.1  280.55  4827.4  280.19  4845.8  279.15  4851.3  279.19  4868.5  278.16
  4874.1  278.16  4891.3  277.47  4896.8  277.48  4919.6  276.22  4947.9  275.49
  4957.9  275.03  4965.1  274.34  4970.6  274.51    4980  273.27  4987.8  271.22
  4993.4  270.73  5002.2  269.25  5007.6  268.85  5010.3  268.35  5013.6  268.85
  5016.1  269.31  5024.3  269.82  5033.3  271.17  5038.9   272.3  5046.4  274.81
  5056.1  276.72  5101.6  277.31  5144.1   278.6  5210.9  281.25  5214.9  281.25
#Mann= 5 ,-1 , 0
  4809.1     .05       0  4827.4      .1       0  5007.6     .07       0
  5013.6      .1       0  5144.1     .05       0
Bank Sta=5007.6,5013.6
XS Rating Curve= 0 ,0
Exp/Cntr=0.3,0.1

Type RM Length L Ch R = 1 ,1483    ,310,310,310
BEGIN DESCRIPTION:
Mapping XS a3db6ec6
END DESCRIPTION:
XS GIS Cut Line= 2
      3591007.52     10259402.11      3590558.29     10259582.23
#Sta/Elev= 30
  4803.4  278.72  4815.1  278.07  4844.7  277.26    4887  275.41  4922.7  273.99
  4970.8  273.03  4976.5  270.77  4981.9  270.26  4992.4   268.2  4997.7  267.53
  5000.5  267.03  5003.7  267.53  5013.9  267.97  5024.7  269.98  5030.3  271.91
  5035.7  273.02  5046.1  273.98  5054.5  274.47  5059.9  274.16  5067.8  274.41
  5089.5   274.5  5121.7  275.36  5132.5  275.37  5143.3  275.85    5154  276.01
  5175.5   277.1  5221.3  278.76  5261.7  279.52  5275.1  280.02  5287.4  279.99
#Mann= 5 ,-1 , 0
  4803.4     .05       0    4887      .1       0  4997.7     .07       0
  5003.7      .1       0  5046.1     .05       0
Bank Sta=4997.7,5003.7
XS Rating Curve= 0 ,0
Exp/Cntr=0.3,0.1

Type RM Length L Ch R = 1 ,1173    ,301,301,301
BEGIN DESCRIPTION:
UNT999 IN WICK 3.0
END DESCRIPTION:
XS GIS Cut Line= 3
      3590944.48     10259165.42      3590792.59     10259128.53
      3590446.23     10259364.48
#Sta/Elev= 30
  4730.3  276.67  4768.1  275.55  4794.5  274.24  4809.9  273.84  4815.1  273.34
  4835.7  272.51  4851.7  271.55  4876.8  271.38  4884.3  272.03  4889.9  272.03
  4903.2  272.64  4918.1  269.89  4924.2  268.15  4937.8  267.77  4944.7  267.48
  4947.4  266.98  4950.7  267.48  4996.1   267.8  5004.9  268.18  5010.9  267.91
  5025.8  268.22  5055.7  268.05  5068.7  268.61  5076.7  270.04  5097.7  271.36
  5152.9  273.25  5184.4  274.77  5241.3  276.92  5277.2  277.98  5305.7  278.24
#Mann= 5 ,-1 , 0
  4730.3     .05       0  4937.8     .07       0  4944.7     .07       0
  4950.7     .07       0  5152.9     .05       0
Bank Sta=4944.7,4950.7
XS Rating Curve= 0 ,0
Exp/Cntr=0.3,0.1

Type RM Length L Ch R = 1 ,872     ,25,25,25
BEGIN DESCRIPTION:
Mapping XS 2fbf2315
END DESCRIPTION:
XS GIS Cut Line= 6
      3590825.19     10258911.52       3590712.3     10258898.49
      3590601.62     10258909.34      3590540.85     10258928.88
      3590445.37      10258963.6      3590366.08      10259072.6
#Sta/Elev= 30
  4746.2  272.93  4839.9  270.68  4857.4  267.93  4870.1  267.61  4900.2  267.83
  4939.4  269.42  4944.4   267.6  4973.4  268.12  4990.6  269.52  4995.8  267.75
  5012.6  268.74  5022.7   269.2  5031.6  268.27  5053.6  268.65  5058.9  267.84
  5084.1  268.79  5089.5   267.8    5108  268.32  5114.7  269.67  5120.1  268.36
  5135.6  269.47  5144.9  268.08  5152.7  268.38  5170.2  267.49    5173  266.99
  5176.2  267.49  5186.5  267.73  5210.4  269.45  5214.8  270.59  5271.7  271.71
#Mann= 5 ,-1 , 0
  4746.2     .05       0  5012.6     .07       0  5152.7     .05       0
  5170.2     .03       0  5176.2     .05       0
Bank Sta=5170.2,5176.2
XS Rating Curve= 0 ,0
Exp/Cntr=0.3,0.1

Type RM Length L Ch R = 1 ,847     ,29,29,29
BEGIN DESCRIPTION:
Mapping XS ba242ade
END DESCRIPTION:
XS GIS Cut Line= 6
      3590825.19     10258887.65      3590731.83     10258874.62
      3590616.81      10258883.3      3590532.17     10258902.83
       3590443.2     10258933.22      3590337.01     10259061.05
#Sta/Elev= 30
  4736.5  272.76  4790.1  271.57  4856.6  272.96  4861.6  272.38  4930.8  273.62
  5001.2  273.53  5022.8  273.67  5041.5  272.82  5046.8  273.43  5064.7  273.55
  5072.9  272.79  5085.9  273.61  5096.4   272.9  5104.2  271.47  5109.5  273.16
  5124.9  270.77  5129.3  270.77  5133.8  272.43  5140.6   271.7    5148  272.52
  5154.4  272.02  5176.3  270.59  5183.1  270.72  5208.4  268.18  5211.1  267.68
  5214.4  268.18    5226   270.6  5232.2  271.09  5261.4  270.91  5293.4  271.74
#Mann= 5 ,-1 , 0
  4736.5     .05       0  5001.2     .07       0  5154.4     .05       0
  5208.4     .03       0  5214.4     .05       0
Bank Sta=5208.4,5214.4
XS Rating Curve= 0 ,0
Exp/Cntr=0.3,0.1

Type RM Length L Ch R = 1 ,818     ,180,180,180
BEGIN DESCRIPTION:
UNT999 IN WICK 2.0
END DESCRIPTION:
XS GIS Cut Line= 6
       3590844.7     10258857.26       3590697.1     10258844.24
      3590482.26     10258881.13      3590419.33     10258909.34
      3590365.07     10258948.41      3590297.79     10259052.59
#Sta/Elev= 30
  4705.6  272.67  4778.5  269.86    4825  270.11  4830.1  268.45  4865.9  267.09
    4871  269.23  4879.1  268.26  4925.9  266.06    4931  268.53  4970.5  267.01
  4985.9  265.62  4988.6     267    4991  268.23  5040.8  264.16  5045.9  266.65
  5078.3  263.85  5081.1  263.35  5084.3  263.85  5086.8  265.47  5104.5  264.98
    5110   266.2  5126.7  265.78  5154.5  267.15  5169.2  266.12  5175.4  266.89
  5183.9  266.43    5235  267.62  5256.1  270.37  5283.2  270.14  5331.6  271.82
#Mann= 5 ,-1 , 0
  4705.6     .05       0  4988.6     .07       0  5078.3     .07       0
  5084.3     .07       0  5154.5     .05       0
Bank Sta=5078.3,5084.3
XS Rating Curve= 0 ,0
Exp/Cntr=0.3,0.1

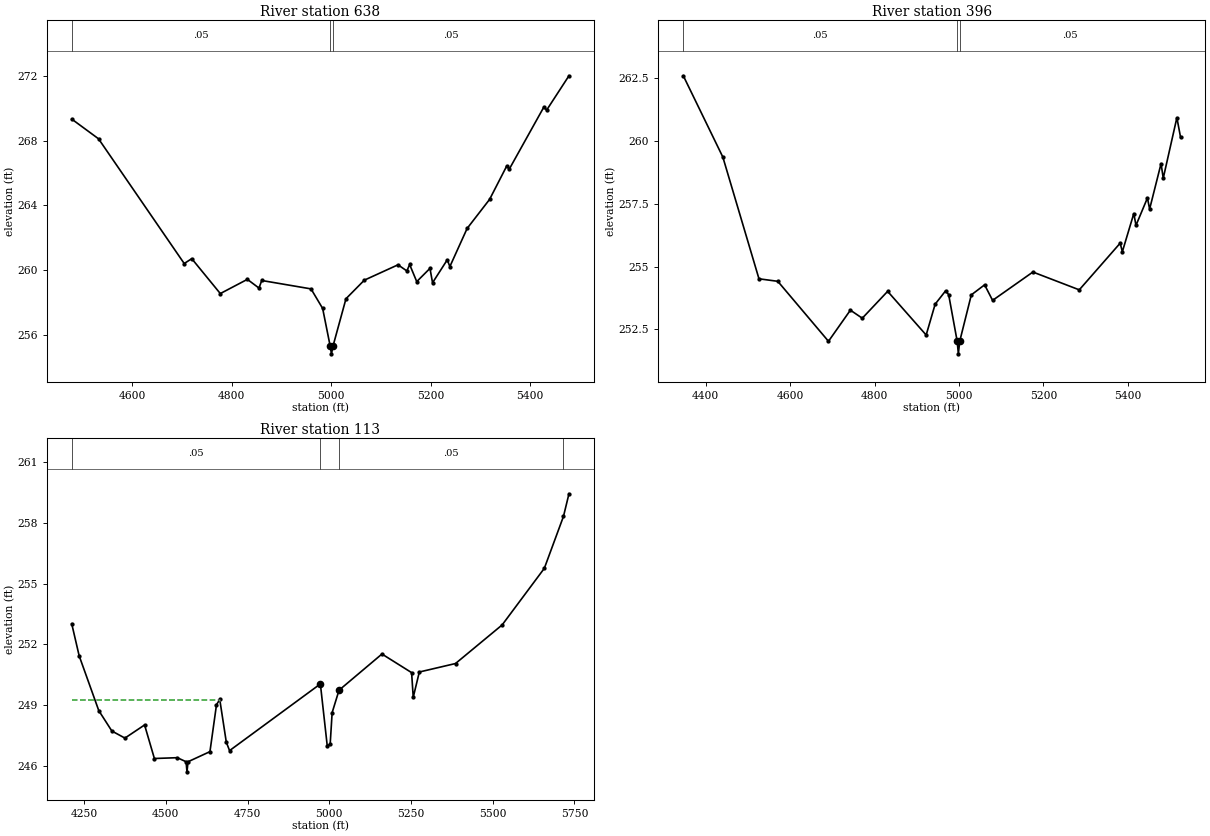
Type RM Length L Ch R = 1 ,638     ,242,242,242
BEGIN DESCRIPTION:
UNT999 IN WICK 1.0
END DESCRIPTION:
XS GIS Cut Line= 4
      3590968.49     10258768.43      3590716.35     10258605.67
      3590353.88     10258763.72      3590274.73      10259057.6
#Sta/Elev= 30
  4478.5  269.34  4532.4  268.12  4704.7   260.4  4719.9   260.7  4777.3  258.54
  4831.7  259.42  4855.1  258.88  4860.6  259.35  4959.7  258.83  4983.1  257.62
  4998.1  255.31  5000.8  254.81  5004.1  255.31    5030  258.22  5066.9  259.37
  5134.6  260.32  5152.5  259.94    5158  260.34  5172.3  259.28  5198.9   260.1
  5204.1  259.21  5233.7  260.63  5238.9  260.21  5273.6  262.57  5318.8  264.37
  5353.5  266.45  5358.7  266.26  5428.2   270.1  5433.4  269.89  5478.4  272.02
#Mann= 3 ,-1 , 0
  4478.5     .05       0  4998.1    .035       0  5004.1     .05       0
Bank Sta=4998.1,5004.1
XS Rating Curve= 0 ,0
Exp/Cntr=0.3,0.1

Type RM Length L Ch R = 1 ,396     ,283,283,283
BEGIN DESCRIPTION:
Mapping XS 5ccdea9d
END DESCRIPTION:
XS GIS Cut Line= 4
      3591075.73      10258408.2      3590521.87     10258434.24
      3590346.53     10258498.48      3590214.57     10258915.18
#Sta/Elev= 30
  4346.8   262.6  4440.5  259.36  4526.1  254.51  4570.7  254.41  4690.8  252.02
  4742.7  253.26  4770.9  252.94    4831  254.01  4922.3  252.27  4943.6   253.5
  4968.3  254.03  4975.6  253.88  4995.8  252.02  4998.6  251.52  5001.8  252.02
  5029.3  253.87  5060.8  254.27  5079.7  253.65  5175.2  254.78  5285.1  254.07
    5382  255.93  5387.2  255.59  5414.3  257.11  5419.5  256.64  5446.6  257.73
  5451.8  257.29  5478.9   259.1  5484.1  258.52  5516.4  260.93  5525.1  260.15
#Mann= 3 ,-1 , 0
  4346.8     .05       0  4995.8    .035       0  5001.8     .05       0
Bank Sta=4995.8,5001.8
XS Rating Curve= 0 ,0
Exp/Cntr=0.3,0.1

Type RM Length L Ch R = 1 ,113     ,0,0,0
BEGIN DESCRIPTION:
UNT04973 IN WICK 2.0
END DESCRIPTION:
XS GIS Cut Line= 4
       3591054.9     10258188.41      3590374.31     10258172.78
      3590238.89     10258263.06      3590164.24     10258936.61
#Sta/Elev= 30
  4212.2  253.02    4235  251.43    4295  248.72    4335  247.71    4375  247.36
  4435.1  248.01  4465.1  246.35  4535.1  246.39  4562.1  246.19  4564.8  245.69
  4568.1  246.19  4635.1  246.69  4655.1  249.01  4665.1  249.27  4685.1  247.16
  4695.1  246.74  4972.9  250.04  4993.9  246.98  5002.9  247.06  5008.9  248.62
    5030  249.73  5161.3  251.52    5252   250.6    5257  249.38  5275.6  250.63
  5386.3  251.05    5529  252.96    5658  255.76  5716.6  258.33  5733.4  259.45
#Mann= 4 ,-1 , 0
  4212.2     .05       0  4972.9    .035       0    5030     .05       0
  5716.6      .1       0
#XS Ineff= 2 , 0
         4666.36  249.23
Permanent Ineff=
       F       F
Bank Sta=4972.9,5030
XS Rating Curve= 0 ,0
Exp/Cntr=0.3,0.1

Chan Stop Cuts=-1
Use User Specified Reach Order=0
Composite Channel Slope=5