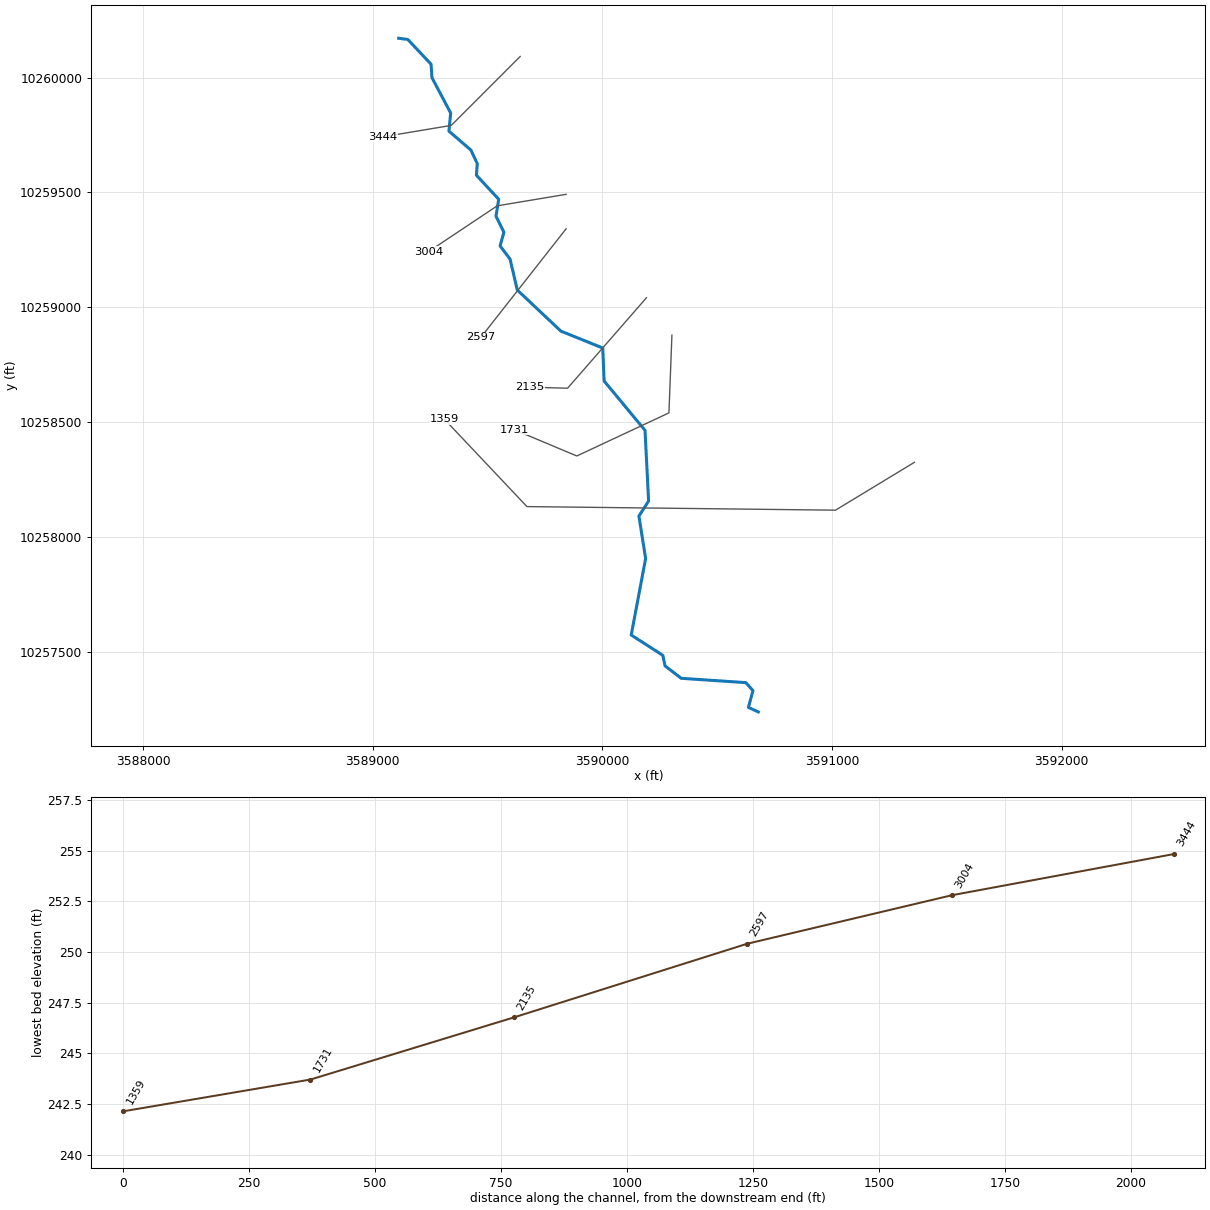
--- BOWMANCREEKTRIB4.prj (project) ---

Proj Title=BOWMAN CREEK TRIB 4
Current Plan=p01
Default Exp/Contr=0.3,0.1
English Units
Geom File=g01
Flow File=f01
Plan File=p01
Y Axis Title=Elevation
X Axis Title(PF)=Main Channel Distance
X Axis Title(XS)=Station
BEGIN DESCRIPTION:
UNT04973 IN WICK
END DESCRIPTION:
DSS Export Rating Curves= 0
DSS Export Rating Curve Sorted= 0
DSS Export Volume Flow Curves= 0
DXF Filename=UNT04973 IN WICK.
DXF OffsetX= 0
DXF OffsetY= 0
DXF ScaleX= 1
DXF ScaleY= 10

--- BOWMANCREEKTRIB4.p01 (plan) ---

Plan Title=Multiple Run
Program Version=4.10
Short Identifier=Multiple Run
Geom File=g01
Flow File=f01
Subcritical Flow
K Sum by GR= 0
Std Step Tol= 0.01
Critical Tol= 0.01
Num of Std Step Trials= 20
Max Error Tol= 0.3
Flow Tol Ratio= 0.001
Split Flow NTrial= 30
Split Flow Tol= 0.02
Split Flow Ratio= 0.02
Log Output Level= 0
Friction Slope Method= 1
Unsteady Friction Slope Method= 2
Unsteady Bridges Friction Slope Method= 1
Parabolic Critical Depth
Global Vel Dist= 1 , 1 , 1
Global Log Level= 0
CheckData=True
Encroach Param=-1 ,0,0, 0
BEGIN DESCRIPTION:
Multiple Run
END DESCRIPTION:
Computation Interval=1HOUR
Output Interval=1HOUR
Run HTab= 0
Run UNet= 0
Run PostProcess= 0
Run WQNet= 0
UNET Theta= 1
UNET Theta Warmup= 1
UNET ZTol= 0.02
UNET ZSATol= 0.05
UNET MxIter= 20
UNET MaxInSteps= 0
UNET DtIC= 0
UNET DtMin= 0
UNET MaxCRTS= 20
UNET WFStab= 2
UNET SFStab= 1
UNET WFX= 1
UNET SFX= 1
UNET DSS MLevel= 4
UNET DZMax Abort= 100
UNET Convert EG Bridges= 0
UNET Use Existing IB Tables=-1
UNET Froude Reduction=False
UNET Froude Limit= 1
UNET Froude Power= 10
UNET Time Slicing=0,0, 5
UNET Junction Losses=0
Instantaneous Interval=1HOUR
DSS File=dss
Write IC File= 0
Write IC File at Sim End=0
Echo Input=False
Echo Parameters=False
Echo Output=False
Write Detailed= 0
WQ AD Non Conservative
WQ ULTIMATE=-1
WQ Max Comp Step=1HOUR
WQ Output Interval=15MIN
WQ Output Selected Increments= 0
WQ Output face flow=0
WQ Output face velocity=0
WQ Output face area=0
WQ Output face dispersion=0
WQ Output cell volume=0
WQ Output cell surface area=0
WQ Output cell continuity=0
WQ Output cumulative cell continuity=0
WQ Output face conc=0
WQ Output face dconc_dx=0
WQ Output face courant=0
WQ Output face peclet=0
WQ Output face adv mass=0
WQ Output face disp mass=0
WQ Output cell mass=0
WQ Output cell source sink temp=0
WQ Output cell source sink nsm=0
WQ Output MaxMinRange=-1
WQ Daily Max Min Mean=-1
WQ Daily Range=0
WQ Daily Time=0
WQ Create Restart=0
WQ Fixed Restart=0
WQ System Summary=0
WQ Use Fixed Temperature=0
Sorting and Armoring Iterations= 10
XS Update Threshold= 0.02
Hydraulics Update Threshold= 0.02
Energy Slope Method= 1
Volume Change Method= 0
XS Weighting Method= 0
Number of US Weighted Cross Sections= 1
Number of DS Weighted Cross Sections= 1
Upstream XS Weight=0.25
Main XS Weight=0.5
Downstream XS Weight=0.25
Number of DS XS's Weighted with US Boundary= 1
Upstream Boundary Weight= 1
Weight of XSs Associated with US Boundary= 0
Number of US XS's Weighted with DS Boundary= 1
Downstream Boundary Weight= 0.5
Weight of XSs Associated with DS Boundary= 0.5
Sediment Output Level= 4
Mass or Volume Output= 0
Output Increment Type= 1
Profile and TS Output Increment= 10
XS Output Flag= 0
XS Output Increment= 10
Disregard all LS=0
Disregard all Conn=0
Disregard all Breaches=0
Disregard all Pumps=0

--- BOWMANCREEKTRIB4.f01 (steady flow) ---

Flow Title=Multiple
Program Version=4.10
Number of Profiles= 7
Profile Names=10-year,25-year,50-year,1pct_min,100-year,1pct_plu,500-year
River Rch & RM=UNT04973 IN WICK,Reach-1         ,3444
     318     412     486     421     570     771     783
River Rch & RM=UNT04973 IN WICK,Reach-1         ,1359
     391     513     611     533     721     975    1007
River Rch & RM=BOWMANCRTRIB4,Reach-1         ,3444
     318     412     486     421     570     771     783
River Rch & RM=BOWMANCRTRIB4,Reach-1         ,1359
     391     513     611     533     721     975    1007
Boundary for River Rch & Prof#=BOWMANCRTRIB4,Reach-1         , 1
Up Type= 0
Dn Type= 3
Dn Slope=0.005
Boundary for River Rch & Prof#=BOWMANCRTRIB4,Reach-1         , 2
Up Type= 0
Dn Type= 3
Dn Slope=0.005
Boundary for River Rch & Prof#=BOWMANCRTRIB4,Reach-1         , 3
Up Type= 0
Dn Type= 3
Dn Slope=0.005
Boundary for River Rch & Prof#=BOWMANCRTRIB4,Reach-1         , 4
Up Type= 0
Dn Type= 3
Dn Slope=0.005
Boundary for River Rch & Prof#=BOWMANCRTRIB4,Reach-1         , 5
Up Type= 0
Dn Type= 3
Dn Slope=0.005
Boundary for River Rch & Prof#=BOWMANCRTRIB4,Reach-1         , 6
Up Type= 0
Dn Type= 3
Dn Slope=0.005
Boundary for River Rch & Prof#=BOWMANCRTRIB4,Reach-1         , 7
Up Type= 0
Dn Type= 3
Dn Slope=0.005
DSS Import GetInterval= 0
DSS Import GetPeak= 0
DSS Import FillOption= 0

--- BOWMANCREEKTRIB4.g01 (geometry) ---

Geom Title=Existing Conditions
Program Version=4.10

River Reach=BOWMANCRTRIB4   ,Reach-1
Reach XY= 30
      3589112.87     10260170.87      3589152.85     10260165.65
      3589254.06     10260057.92      3589258.02      10259999.2
      3589339.44     10259845.62      3589331.92     10259766.63
       3589427.4     10259684.48       3589455.3     10259625.21
      3589451.56     10259574.82      3589548.66     10259470.04
       3589536.8     10259396.79      3589571.17     10259326.67
      3589554.72     10259266.98      3589598.06     10259210.02
      3589629.62     10259075.11       3589819.2      10258896.5
       3590001.7     10258822.76      3590007.69     10258679.16
      3590185.78     10258464.52      3590201.39     10258156.78
      3590159.25     10258091.42      3590188.42     10257906.66
      3590125.74     10257573.77      3590263.44     10257485.23
      3590273.17     10257439.05      3590343.65     10257385.34
      3590624.89     10257366.55       3590655.8     10257331.76
      3590636.06     10257258.67      3590679.07     10257239.05

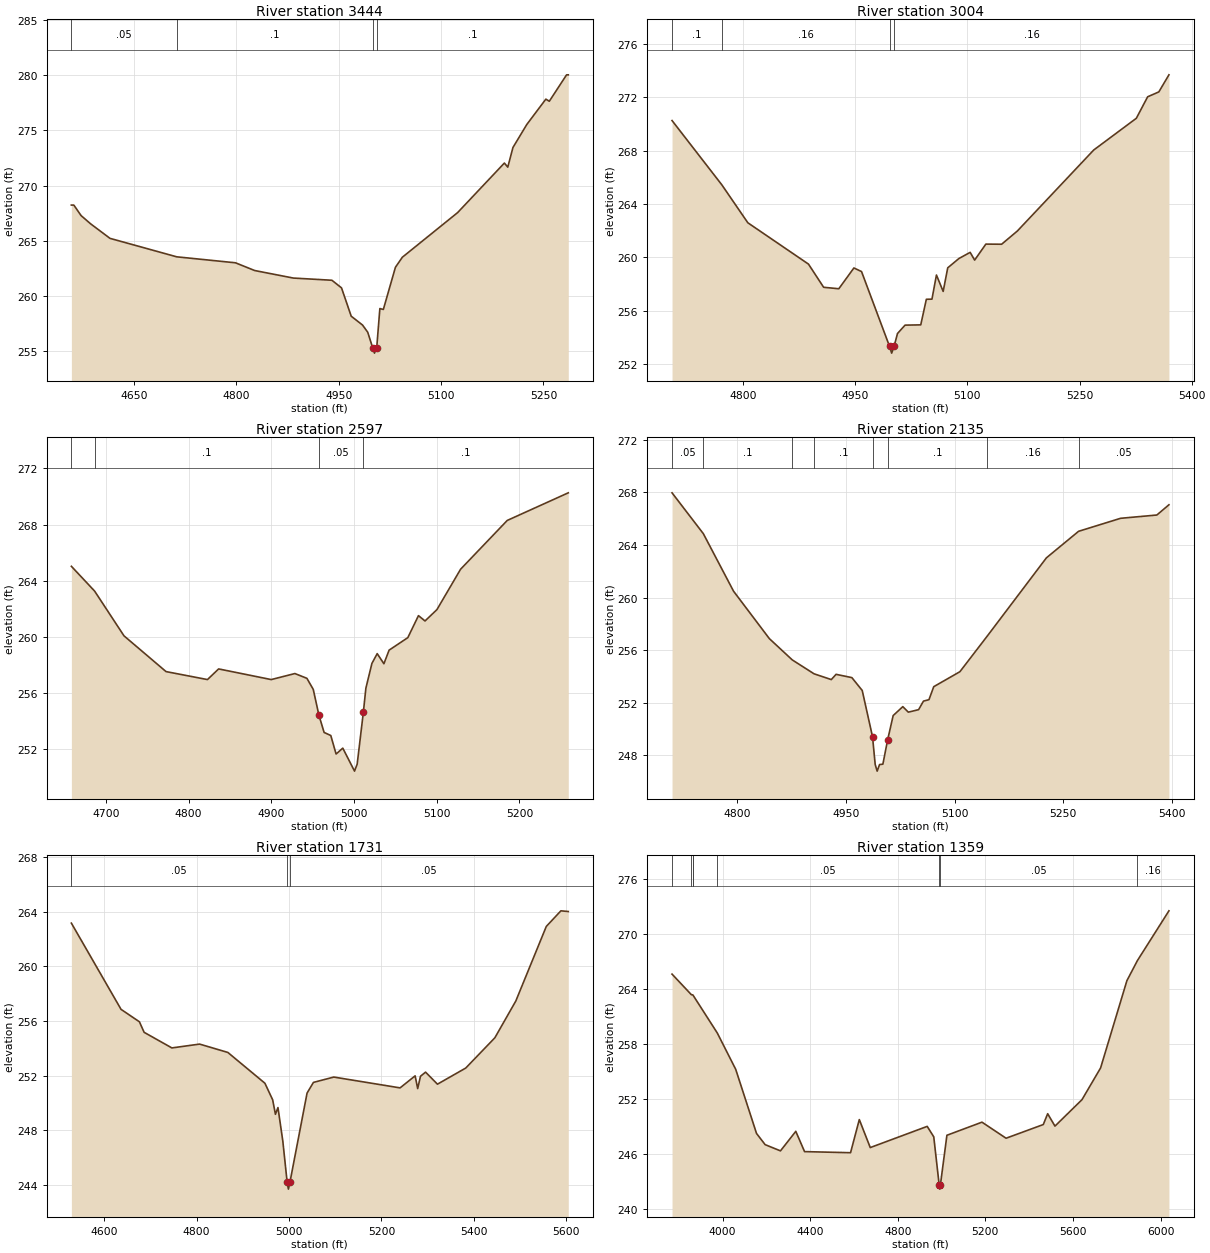
Type RM Length L Ch R = 1 ,3444    ,440,440,440
BEGIN DESCRIPTION:
UNT04973 IN WICK 7.0
END DESCRIPTION:
XS GIS Cut Line= 3
      3589642.14     10260091.67      3589342.11     10259791.64
      3589042.15     10259741.65
#Sta/Elev= 30
  4558.1  268.23  4561.7  268.23  4572.3  267.28  4586.4  266.53  4614.7  265.22
  4712.5  263.55  4798.6  263.01  4826.8  262.31  4883.4  261.63    4940  261.43
  4954.1  260.74  4968.3  258.18  4984.9  257.38  4992.5  256.73  4999.7  255.34
  5002.4  254.84  5005.7  255.34  5010.3  258.87  5015.4  258.79  5033.1   262.6
  5043.2  263.51  5124.3  267.55  5192.8  272.03  5197.8  271.66  5205.4  273.44
  5225.7  275.52  5253.6  277.81  5258.7  277.62    5284  280.01  5286.5  280.01
#Mann= 4 ,-1 , 0
  4558.1     .05       0  4712.5      .1       0  4999.7     .07       0
  5005.7      .1       0
Bank Sta=4999.7,5005.7
XS Rating Curve= 0 ,0
Exp/Cntr=0.3,0.1

Type RM Length L Ch R = 1 ,3004    ,407,407,407
BEGIN DESCRIPTION:
UNT04973 IN WICK 6.0
END DESCRIPTION:
XS GIS Cut Line= 3
      3589842.12     10259491.64      3589542.11     10259441.64
      3589242.11     10259241.65
#Sta/Elev= 30
  4704.9  270.26  4771.6  265.43  4806.3  262.59  4887.4  259.49  4907.7  257.75
    4928  257.64  4948.2   259.2  4958.4  258.93  4995.9  253.31  4998.7  252.81
  5001.9  253.31  5006.5  254.28  5016.6  254.91  5037.6  254.93  5045.1  256.85
  5052.6  256.86  5058.6  258.67  5067.6  257.44  5073.7  259.21  5088.7  259.91
  5103.7  260.37  5109.7  259.79  5124.7  260.99  5145.8  260.98  5166.8  261.97
    5269  268.05    5326  270.43  5341.1  272.04  5356.1  272.41  5369.6  273.69
#Mann= 4 ,-1 , 0
  4704.9      .1       0  4771.6     .16       0  4995.9     .07       0
  5001.9     .16       0
Bank Sta=4995.9,5001.9
XS Rating Curve= 0 ,0
Exp/Cntr=0.3,0.1

Type RM Length L Ch R = 1 ,2597    ,462,462,462
BEGIN DESCRIPTION:
UNT04973 IN WICK 5.0
END DESCRIPTION:
XS GIS Cut Line= 2
       3589842.1     10259341.63      3589471.07     10258869.22
#Sta/Elev= 30
  4658.3  265.02  4686.4  263.25  4721.9  260.06  4772.7  257.51  4822.8  256.94
  4836.3   257.7  4899.9  256.94  4928.5  257.37    4943  257.03  4950.7  256.24
  4957.5  254.41  4963.8  253.17  4971.9  252.95  4978.3  251.63  4986.4  252.05
  5000.6  250.41  5003.8  250.91 5011.25   254.6  5014.3  256.32  5021.6  258.09
    5028  258.79  5036.1  258.07  5042.4  259.04    5065  259.93  5077.9   261.5
  5085.8  261.12  5100.2  261.93  5128.8  264.81  5185.2  268.29    5259  270.26
#Mann= 4 ,-1 , 0
  4658.3      .1       0  4686.4      .1       0  4957.5     .05       0
 5011.25      .1       0
Bank Sta=4957.5,5011.25
XS Rating Curve= 0 ,0
Exp/Cntr=0.3,0.1

Type RM Length L Ch R = 1 ,2135    ,404,404,404
BEGIN DESCRIPTION:
UNT04973 IN WICK 4.0
END DESCRIPTION:
XS GIS Cut Line= 3
      3590192.09     10259041.63      3589848.68     10258647.87
      3589685.41     10258652.17
#Sta/Elev= 30
  4709.9  267.97  4753.1  264.86  4794.8  260.48  4844.2  256.87  4875.8  255.25
  4905.9  254.19  4929.7  253.75  4936.3  254.15  4958.1   253.9  4972.4  252.92
  4986.6   249.4  4990.3  247.28    4993  246.78  4996.3  247.28  5000.9  247.31
  5007.5  249.17  5015.1  251.01  5028.4  251.69    5036  251.27  5050.2  251.46
  5056.9  252.11  5064.5  252.22  5071.1  253.21  5107.2  254.35  5144.5  257.03
  5226.6  263.02    5271  265.04    5329  266.03    5379  266.28  5395.7  267.06
#Mann= 8 ,-1 , 0
  4709.9     .05       0  4753.1      .1       0  4875.8     .05       0
  4905.9      .1       0  4986.6     .03       0  5007.5      .1       0
  5144.5     .16       0    5271     .05       0
Bank Sta=4986.6,5007.5
XS Rating Curve= 0 ,0
Exp/Cntr=0.3,0.1

Type RM Length L Ch R = 1 ,1731    ,372,372,372
BEGIN DESCRIPTION:
Mapping XS cc2e1ee5
END DESCRIPTION:
XS GIS Cut Line= 4
      3590302.95     10258879.05      3590289.93     10258540.49
      3589888.89     10258352.99      3589617.38     10258466.77
#Sta/Elev= 30
  4528.8  263.15  4636.3  256.85  4676.1  255.94  4686.3  255.17  4746.4  254.03
  4806.4  254.31  4867.6   253.7  4947.8  251.45  4964.6  250.24  4970.6  249.18
  4976.1  249.67  4986.6  247.22    4996  244.21  4998.7  243.71    5002  244.21
  5039.1  250.73  5052.9  251.51    5097   251.9  5240.5  251.11  5273.1  251.99
  5278.6  251.06  5284.7  251.96  5295.7  252.26  5321.4  251.38  5382.7  252.56
  5445.7  254.77  5491.1  257.46  5557.1  262.91  5588.7  264.05  5604.7     264
#Mann= 3 ,-1 , 0
  4528.8     .05       0    4996    .035       0    5002     .05       0
Bank Sta=4996,5002
XS Rating Curve= 0 ,0
Exp/Cntr=0.3,0.1

Type RM Length L Ch R = 1 ,1359    ,0,0,0
BEGIN DESCRIPTION:
UNT04973 IN WICK 1.0
END DESCRIPTION:
XS GIS Cut Line= 4
        3591359.     10258325.38      3591015.29     10258117.07
      3589671.54      10258132.7      3589312.18     10258512.89
#Sta/Elev= 30
  3769.4  265.58    3858  263.33  3863.3  263.32  3864.9   263.3  3976.1  259.16
  4060.2   255.2  4155.2  248.21  4194.5  246.99  4264.5  246.31  4334.5  248.44
  4374.5  246.23  4584.5  246.11  4624.5  249.72  4674.5  246.67  4934.5  248.98
  4964.5  247.84    4989  242.64  4991.8  242.14    4995  242.64  5024.5  248.01
  5184.6  249.44  5294.6  247.69  5464.6  249.18  5484.6  250.36  5517.9  249.01
  5641.2  251.89  5726.2  255.35  5846.3  264.86  5894.2  267.05  6038.3  272.48
#Mann= 8 ,-1 , 0
  3769.4     .05       0    3858      .1       0  3863.3     .05       0
  3864.9      .1       0  3976.1     .05       0    4989     .03       0
    4995     .05       0  5894.2     .16       0
Bank Sta=4989,4995
XS Rating Curve= 0 ,0
Exp/Cntr=0.3,0.1

Chan Stop Cuts=-1
Use User Specified Reach Order=0
Composite Channel Slope=5