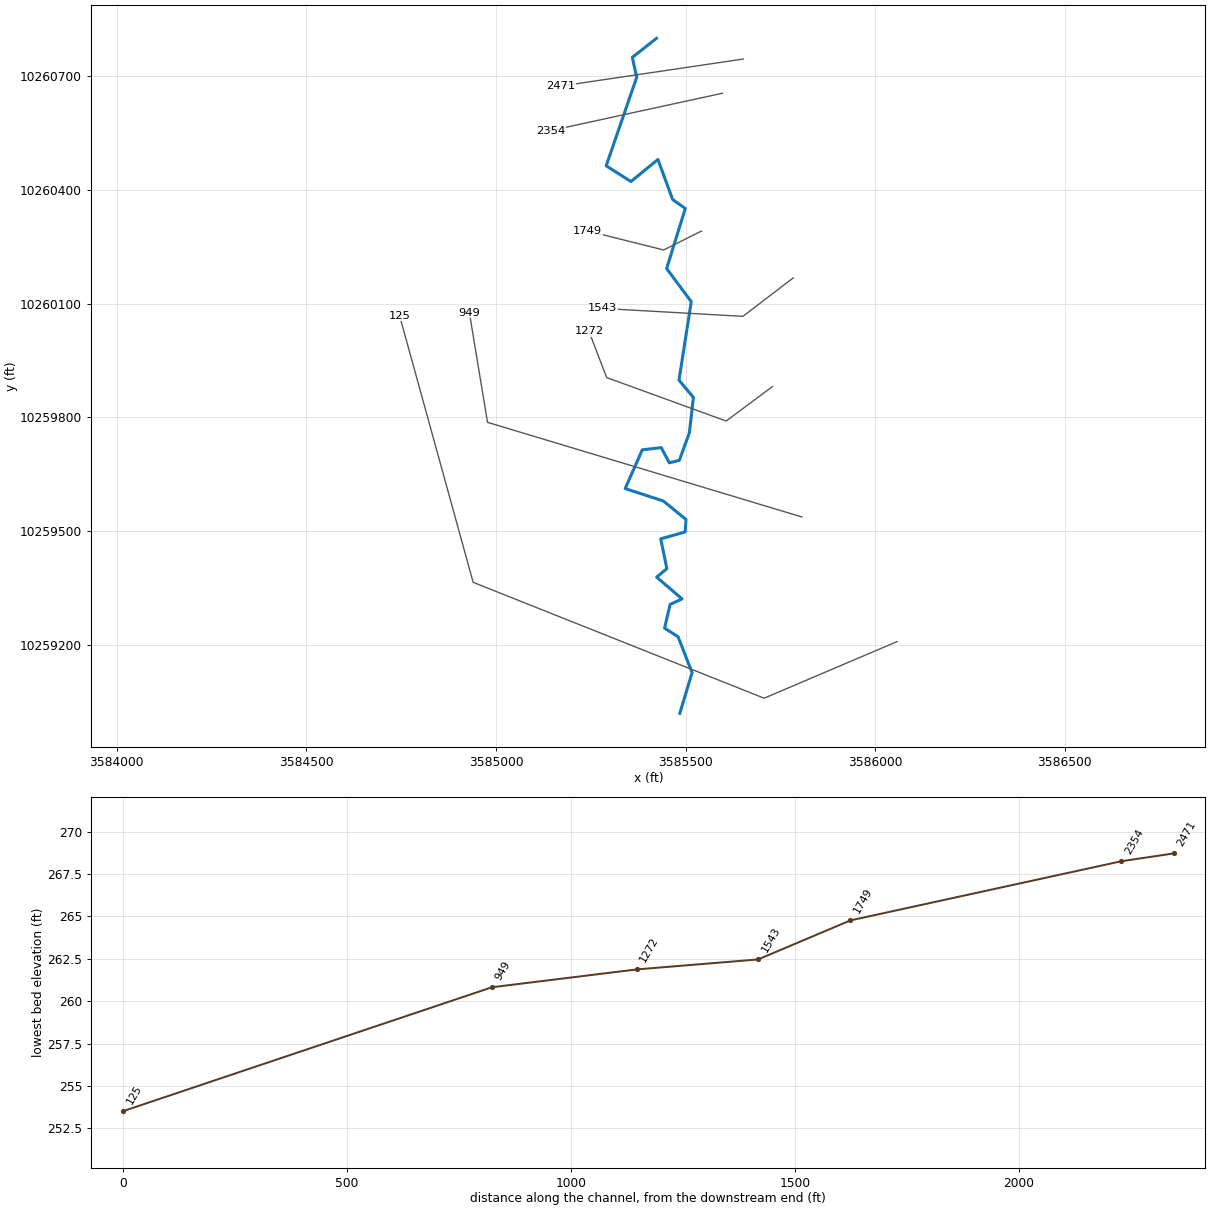
--- BOWMANCREEKTRIB7.prj (project) ---

Proj Title=BOWMAN CREEK TRIB 7
Current Plan=p01
Default Exp/Contr=0.3,0.1
English Units
Geom File=g01
Flow File=f01
Plan File=p01
Y Axis Title=Elevation
X Axis Title(PF)=Main Channel Distance
X Axis Title(XS)=Station
BEGIN DESCRIPTION:
UNT04969 IN WICK
END DESCRIPTION:
DSS Export Rating Curves= 0
DSS Export Rating Curve Sorted= 0
DSS Export Volume Flow Curves= 0
DXF OffsetX= 0
DXF OffsetY= 0
DXF ScaleX= 1
DXF ScaleY= 10

--- BOWMANCREEKTRIB7.p01 (plan) ---

Plan Title=Multiple Run
Short Identifier=Multiple
Geom File=g01
Flow File=f01
Subcritical Flow
K Sum by GR= 0
Std Step Tol= 0.01
Critical Tol= 0.01
Num of Std Step Trials= 20
Max Error Tol= 0.3
Flow Tol Ratio= 0.001
Split Flow NTrial= 30
Split Flow Tol= 0.02
Split Flow Ratio= 0.02
Log Output Level= 0
Friction Slope Method= 1
Unsteady Friction Slope Method= 2
Unsteady Bridges Friction Slope Method= 1
Parabolic Critical Depth
Global Vel Dist=  1 , 1 , 1
Global Log Level= 0
CheckData=True
Encroach Param= -1, 0, 0, 0
BEGIN DESCRIPTION:
Multiple Run
END DESCRIPTION:

--- BOWMANCREEKTRIB7.f01 (steady flow) ---

Flow Title=Multiple
Program Version=4.10
Number of Profiles= 7
Profile Names=10-year,25-year,50-year,1pct_min,100-year,1pct_plu,500-year
River Rch & RM=UNT04969 IN WICK,Reach-1         ,2471
     221     278     321     273     369     499     486
River Rch & RM=BOWMANCRTRIB7,Reach-1         ,2471
     221     278     321     273     369     499     486
Boundary for River Rch & Prof#=BOWMANCRTRIB7,Reach-1         , 1
Up Type= 0
Dn Type= 3
Dn Slope=0.005
Boundary for River Rch & Prof#=BOWMANCRTRIB7,Reach-1         , 2
Up Type= 0
Dn Type= 3
Dn Slope=0.005
Boundary for River Rch & Prof#=BOWMANCRTRIB7,Reach-1         , 3
Up Type= 0
Dn Type= 3
Dn Slope=0.005
Boundary for River Rch & Prof#=BOWMANCRTRIB7,Reach-1         , 4
Up Type= 0
Dn Type= 3
Dn Slope=0.005
Boundary for River Rch & Prof#=BOWMANCRTRIB7,Reach-1         , 5
Up Type= 0
Dn Type= 3
Dn Slope=0.005
Boundary for River Rch & Prof#=BOWMANCRTRIB7,Reach-1         , 6
Up Type= 0
Dn Type= 3
Dn Slope=0.005
Boundary for River Rch & Prof#=BOWMANCRTRIB7,Reach-1         , 7
Up Type= 0
Dn Type= 3
Dn Slope=0.005
DSS Import GetInterval= 0
DSS Import GetPeak= 0
DSS Import FillOption= 0

--- BOWMANCREEKTRIB7.g01 (geometry) ---

Geom Title=Existing Conditions
Program Version=4.10

River Reach=BOWMANCRTRIB7   ,Reach-1
Reach XY= 30
      3585423.16     10260799.71      3585359.61     10260749.45
      3585371.07     10260696.84       3585290.6     10260463.51
      3585355.97      10260422.1      3585427.06     10260480.18
      3585465.95     10260374.71      3585499.28     10260351.01
      3585450.09     10260192.61      3585514.94     10260105.37
      3585482.64     10259898.34      3585520.66     10259852.76
      3585509.99     10259759.27      3585483.43     10259686.88
      3585457.12     10259680.37      3585435.77     10259720.47
      3585385.77     10259714.48      3585340.72      10259612.4
       3585441.5     10259579.59      3585501.13     10259530.89
      3585499.05     10259498.08      3585434.47     10259479.85
      3585450.61      10259401.2      3585423.79      10259378.8
      3585490.72     10259321.51      3585459.21     10259306.93
      3585444.62     10259244.43       3585480.3     10259221.43
      3585517.11     10259126.98      3585484.78     10259019.59

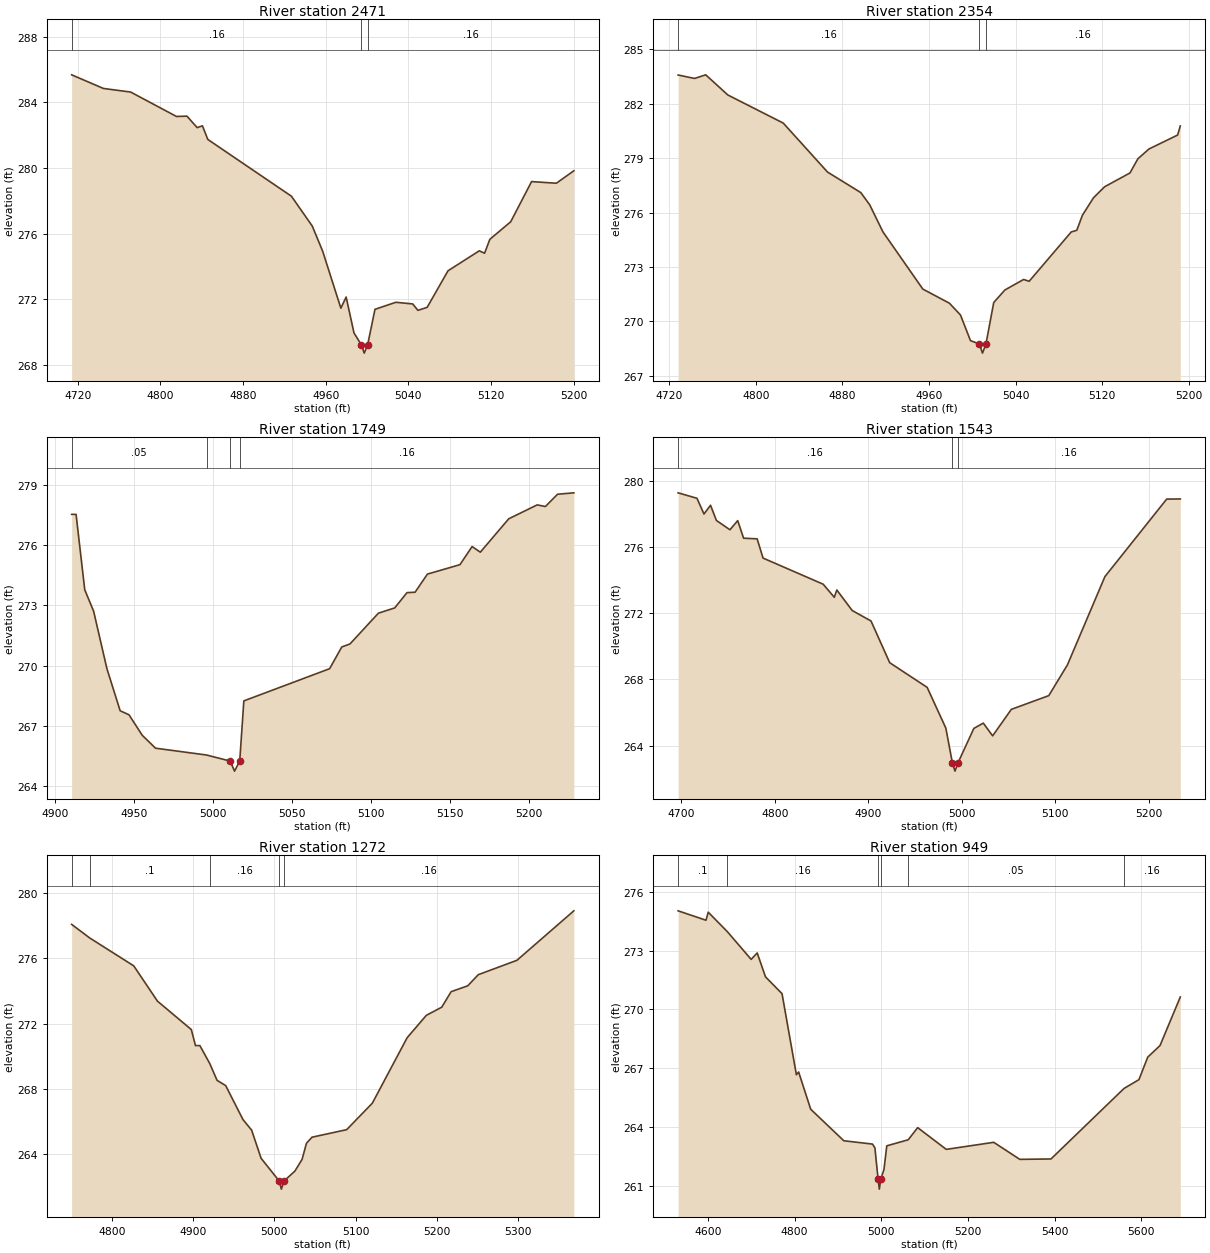
Type RM Length L Ch R = 1 ,2471    ,117,117,117
BEGIN DESCRIPTION:
UNT04969 IN WICK 4.0
END DESCRIPTION:
XS GIS Cut Line= 2
       3585652.5     10260745.15      3585171.64     10260673.98
#Sta/Elev= 30
  4714.1  285.68  4744.8  284.85  4771.2  284.63  4815.6  283.14  4825.7  283.16
  4835.6  282.46  4840.7  282.57  4845.9  281.74  4926.8  278.28    4947  276.46
  4957.1  274.92  4974.7  271.45  4979.8  272.13  4987.4  269.94  4994.6  269.21
  4997.3  268.71  5000.6  269.21  5007.7  271.38  5027.9  271.81  5044.2  271.71
  5049.3  271.32  5058.2   271.5  5078.4  273.73  5108.7  274.95  5113.8   274.8
  5118.9  275.65  5139.1  276.72  5159.3  279.17  5183.3  279.07  5200.2  279.83
#Mann= 3 ,-1 , 0
  4714.1     .16       0  4994.6     .07       0  5000.6     .16       0
Bank Sta=4994.6,5000.6
XS Rating Curve= 0 ,0
Exp/Cntr=0.3,0.1

Type RM Length L Ch R = 1 ,2354    ,605,605,605
BEGIN DESCRIPTION:
Mapping XS a5822fd6
END DESCRIPTION:
XS GIS Cut Line= 2
      3585596.98     10260654.88      3585143.78     10260556.28
#Sta/Elev= 30
  4728.2  283.58  4743.4  283.39  4753.7  283.59  4774.1  282.48  4825.3  280.93
  4866.2  278.23  4896.9   277.1  4905.1  276.43  4917.4  274.93  4954.2  271.78
  4978.8     271    4989  270.35  4998.2  268.94  5006.5  268.75  5009.3  268.25
  5012.5  268.75  5019.7  271.04    5030  271.73  5047.3  272.31  5052.4  272.21
  5091.3  274.93  5096.4  275.02  5101.6  275.85  5111.8  276.81  5122.1  277.42
  5145.5  278.18  5152.8  278.96    5163   279.5  5189.5  280.27    5192  280.77
#Mann= 3 ,-1 , 0
  4728.2     .16       0  5006.5     .07       0  5012.5     .16       0
Bank Sta=5006.5,5012.5
XS Rating Curve= 0 ,0
Exp/Cntr=0.3,0.1

Type RM Length L Ch R = 1 ,1749    ,206,206,206
BEGIN DESCRIPTION:
UNT04969 IN WICK 3.0
END DESCRIPTION:
XS GIS Cut Line= 3
      3585542.07     10260291.63      3585442.11     10260241.64
      3585242.13     10260291.64
#Sta/Elev= 30
  4910.6  277.52  4913.4  277.52  4918.9  273.77  4924.5  272.71  4932.9  269.86
  4941.3  267.76  4946.9  267.56  4955.3  266.54  4963.7   265.9    4996  265.56
    5011  265.26  5013.7  264.76    5017  265.26  5019.6  268.25  5073.9  269.85
  5081.6  270.93  5086.8  271.08  5104.8  272.61  5115.1  272.87  5122.9  273.63
    5128  273.65  5135.8  274.55  5156.4  275.02  5164.1  275.92  5169.3  275.64
  5187.3   277.3  5205.3  277.99  5210.5  277.91  5218.2  278.52  5228.5  278.59
#Mann= 4 ,-1 , 0
  4910.6     .05       0    4996     .16       0    5011     .07       0
    5017     .16       0
Bank Sta=5011,5017
XS Rating Curve= 0 ,0
Exp/Cntr=0.3,0.1

Type RM Length L Ch R = 1 ,1543    ,271,271,271
BEGIN DESCRIPTION:
Mapping XS 43cc287d
END DESCRIPTION:
XS GIS Cut Line= 3
      3585784.13     10260168.16      3585651.28     10260066.58
       3585281.5     10260087.41
#Sta/Elev= 30
  4696.4  279.27  4716.6  278.94  4724.1  277.99  4731.1  278.52  4737.4   277.6
  4751.9  277.04  4760.2  277.59  4766.5  276.53    4781  276.49  4787.3  275.33
  4851.7  273.75  4863.6  272.96  4866.3   273.4  4882.8  272.16  4902.9  271.53
  4922.9  269.01    4963  267.52    4983  265.06    4990  262.96  4992.8  262.46
    4996  262.96    5013  265.04  5023.1  265.36  5033.1  264.59  5053.1  266.19
  5093.2  267.02  5113.2  268.88  5153.3  274.21  5219.4  278.89    5234   278.9
#Mann= 3 ,-1 , 0
  4696.4     .16       0    4990     .07       0    4996     .16       0
Bank Sta=4990,4996
XS Rating Curve= 0 ,0
Exp/Cntr=0.3,0.1

Type RM Length L Ch R = 1 ,1272    ,323,323,323
BEGIN DESCRIPTION:
UNT04969 IN WICK 2.0
END DESCRIPTION:
XS GIS Cut Line= 4
       3585729.4     10259881.68      3585607.01     10259790.54
      3585291.91     10259905.12       3585245.2      10260027.1
#Sta/Elev= 30
  4750.4  278.08  4772.6  277.25  4826.9  275.54  4856.1  273.38  4897.8  271.64
  4902.9  270.66  4908.3  270.66  4920.6  269.55  4929.5  268.53  4940.1  268.21
  4961.4  266.13  4972.1  265.48  4983.7  263.76    5006  262.37  5008.7  261.87
    5012  262.37  5025.3  262.97  5034.2  263.69  5039.6  264.68  5046.5  265.05
  5089.1  265.51  5120.7  267.13  5163.6  271.14  5187.2  272.51  5206.2  273.01
  5217.8  273.96  5238.3  274.32  5251.2     275  5298.8  275.88  5368.9  278.91
#Mann= 5 ,-1 , 0
  4750.4     .16       0  4772.6      .1       0  4920.6     .16       0
    5006     .07       0    5012     .16       0
Bank Sta=5006,5012
XS Rating Curve= 0 ,0
Exp/Cntr=0.3,0.1

Type RM Length L Ch R = 1 ,949     ,824,824,824
BEGIN DESCRIPTION:
Mapping XS 04fab62b
END DESCRIPTION:
XS GIS Cut Line= 3
      3585806.72     10259537.54      3584977.69     10259787.12
      3584929.95     10260075.72
#Sta/Elev= 30
  4531.4  275.03  4595.7  274.55  4600.9  274.96  4644.8  273.97  4699.9  272.55
  4713.8  272.88  4732.9  271.66  4771.1   270.8  4804.2  266.66  4809.4   266.8
  4837.2   264.9  4913.6  263.29  4979.7  263.12  4985.3  262.93  4992.7  261.32
  4995.5  260.82  4998.7  261.32  5006.2  261.82  5012.7  263.03  5062.2  263.34
  5083.9  263.96  5149.9  262.85  5259.4  263.21  5319.5  262.34  5391.4  262.36
  5559.9  265.96  5594.3  266.41  5614.6  267.56  5642.9  268.15  5689.7  270.63
#Mann= 6 ,-1 , 0
  4531.4      .1       0  4644.8     .16       0  4992.7     .07       0
  4998.7     .16       0  5062.2     .05       0  5559.9     .16       0
Bank Sta=4992.7,4998.7
XS Rating Curve= 0 ,0
Exp/Cntr=0.3,0.1

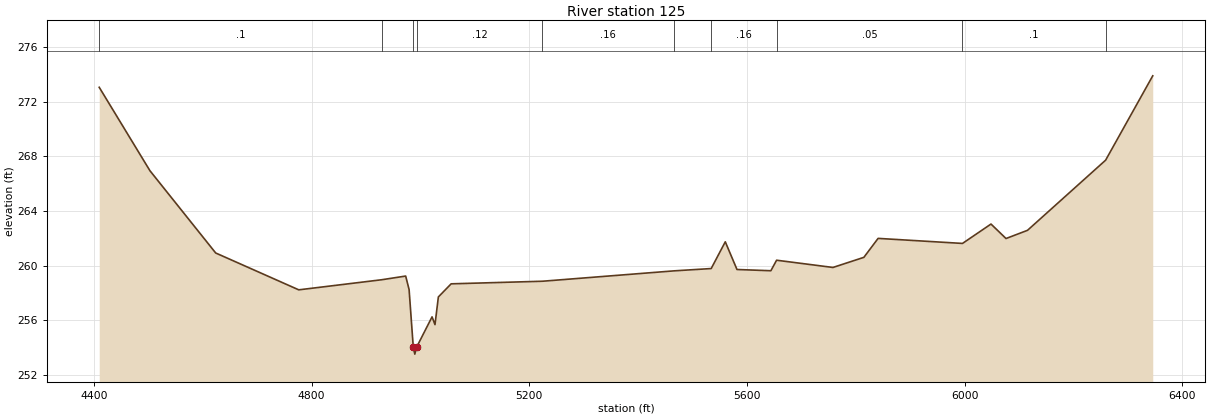
Type RM Length L Ch R = 1 ,125     ,0,0,0
BEGIN DESCRIPTION:
UNT04969 IN WICK 1.0
END DESCRIPTION:
XS GIS Cut Line= 4
      3586057.85     10259208.91      3585707.16     10259059.61
       3584939.8     10259365.16      3584745.83     10260068.28
#Sta/Elev= 30
  4409.5  273.06  4502.7  266.95  4623.6  260.92  4776.3  258.22  4928.9  258.96
  4972.8  259.23  4979.1  258.24  4986.8  254.01  4989.6  253.51  4992.8  254.01
  5021.3  256.24  5026.7  255.67  5032.9   257.7  5056.4  258.66  5224.2  258.85
  5465.9  259.61  5534.4  259.78  5560.3  261.74  5581.8  259.71  5644.1  259.62
  5654.6  260.39  5758.2  259.86    5815   260.6  5841.2  261.99  5996.3  261.62
  6048.7  263.04  6076.3  261.98  6115.8  262.58  6259.4  267.72    6346   273.9
#Mann= 10 ,-1 , 0
  4409.5      .1       0  4928.9     .12       0  4986.8     .07       0
  4992.8     .12       0  5224.2     .16       0  5465.9     .05       0
  5534.4     .16       0  5654.6     .05       0  5996.3      .1       0
  6259.4     .05       0
Bank Sta=4986.8,4992.8
XS Rating Curve= 0 ,0
Exp/Cntr=0.3,0.1

Chan Stop Cuts=-1
Use User Specified Reach Order=0
Composite Channel Slope=5