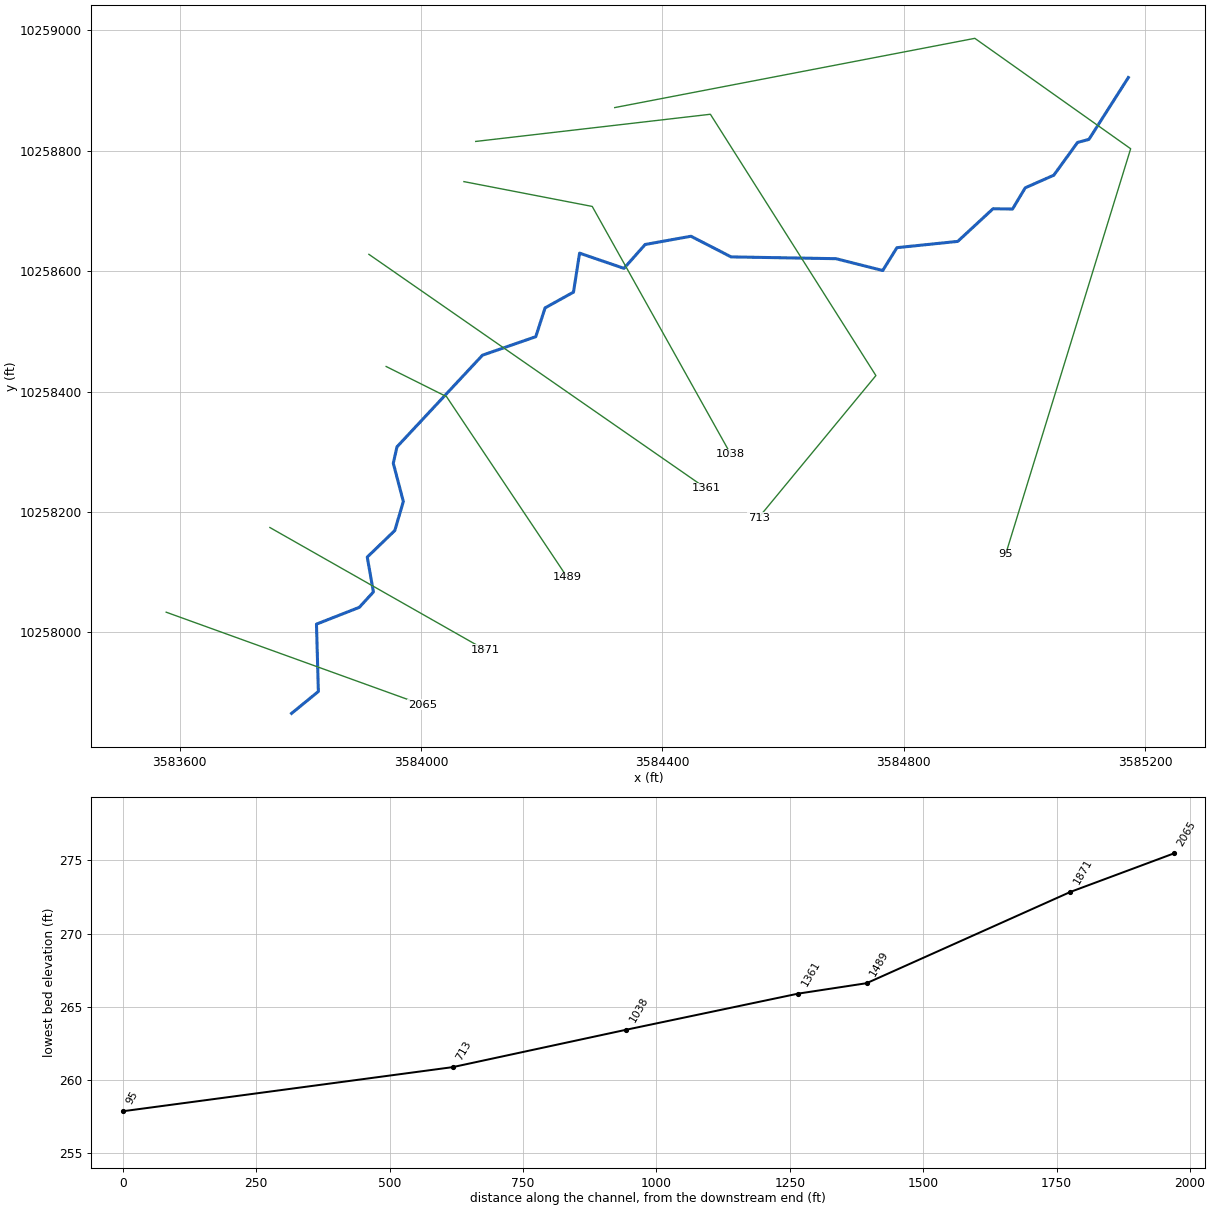
--- BOWMANCREEKTRIB8.prj (project) ---

Proj Title=BOWMAN CREEK TRIB 8
Current Plan=p01
Default Exp/Contr=0.3,0.1
English Units
Geom File=g01
Flow File=f01
Plan File=p01
Y Axis Title=Elevation
X Axis Title(PF)=Main Channel Distance
X Axis Title(XS)=Station
BEGIN DESCRIPTION:
UNT04968 IN WICK
END DESCRIPTION:
DSS Export Rating Curves= 0
DSS Export Rating Curve Sorted= 0
DSS Export Volume Flow Curves= 0
DXF Filename=UNT04968 IN WICK.
DXF OffsetX= 0
DXF OffsetY= 0
DXF ScaleX= 1
DXF ScaleY= 10

--- BOWMANCREEKTRIB8.p01 (plan) ---

Plan Title=Multiple Run
Short Identifier=Multiple
Geom File=g01
Flow File=f01
Subcritical Flow
K Sum by GR= 0
Std Step Tol= 0.01
Critical Tol= 0.01
Num of Std Step Trials= 20
Max Error Tol= 0.3
Flow Tol Ratio= 0.001
Split Flow NTrial= 30
Split Flow Tol= 0.02
Split Flow Ratio= 0.02
Log Output Level= 0
Friction Slope Method= 1
Unsteady Friction Slope Method= 2
Unsteady Bridges Friction Slope Method= 1
Parabolic Critical Depth
Global Vel Dist=  1 , 1 , 1
Global Log Level= 0
CheckData=True
Encroach Param= -1, 0, 0, 0
BEGIN DESCRIPTION:
Multiple Run
END DESCRIPTION:

--- BOWMANCREEKTRIB8.f01 (steady flow) ---

Flow Title=Multiple
Program Version=4.10
Number of Profiles= 7
Profile Names=10-year,25-year,50-year,1pct_min,100-year,1pct_plu,500-year
River Rch & RM=UNT04968 IN WICK,Reach-1         ,2065
     126     153     173     145     196     265     249
River Rch & RM=BOWMANCRTRIB8,Reach-1         ,2065
     126     153     173     145     196     265     249
Boundary for River Rch & Prof#=BOWMANCRTRIB8,Reach-1         , 1
Up Type= 0
Dn Type= 3
Dn Slope=0.005
Boundary for River Rch & Prof#=BOWMANCRTRIB8,Reach-1         , 2
Up Type= 0
Dn Type= 3
Dn Slope=0.005
Boundary for River Rch & Prof#=BOWMANCRTRIB8,Reach-1         , 3
Up Type= 0
Dn Type= 3
Dn Slope=0.005
Boundary for River Rch & Prof#=BOWMANCRTRIB8,Reach-1         , 4
Up Type= 0
Dn Type= 3
Dn Slope=0.005
Boundary for River Rch & Prof#=BOWMANCRTRIB8,Reach-1         , 5
Up Type= 0
Dn Type= 3
Dn Slope=0.005
Boundary for River Rch & Prof#=BOWMANCRTRIB8,Reach-1         , 6
Up Type= 0
Dn Type= 3
Dn Slope=0.005
Boundary for River Rch & Prof#=BOWMANCRTRIB8,Reach-1         , 7
Up Type= 0
Dn Type= 3
Dn Slope=0.005
DSS Import GetInterval= 0
DSS Import GetPeak= 0
DSS Import FillOption= 0

--- BOWMANCREEKTRIB8.g01 (geometry) ---

Geom Title=Existing Conditions
Program Version=4.10

River Reach=BOWMANCRTRIB8   ,Reach-1
Reach XY= 30
      3583785.34     10257865.53      3583829.73     10257901.87
      3583826.58     10258013.74       3583897.6     10258041.66
      3583920.94     10258067.21      3583910.75     10258125.11
      3583956.35     10258169.18      3583970.57     10258217.38
      3583953.88     10258280.98        3583960.     10258308.22
       3584101.7     10258460.43      3584190.05     10258491.19
      3584205.45     10258539.04      3584252.52     10258565.14
      3584262.64     10258629.93      3584336.19     10258604.65
       3584371.3     10258644.32      3584447.25     10258657.99
      3584513.76      10258623.7      3584687.55     10258620.72
      3584765.05     10258601.09      3584788.55     10258639.02
      3584889.36     10258649.45      3584947.87     10258703.69
      3584980.16     10258703.17      3585001.23     10258738.47
      3585048.51     10258759.33      3585087.97     10258813.86
      3585106.72      10258818.8      3585172.11     10258921.64

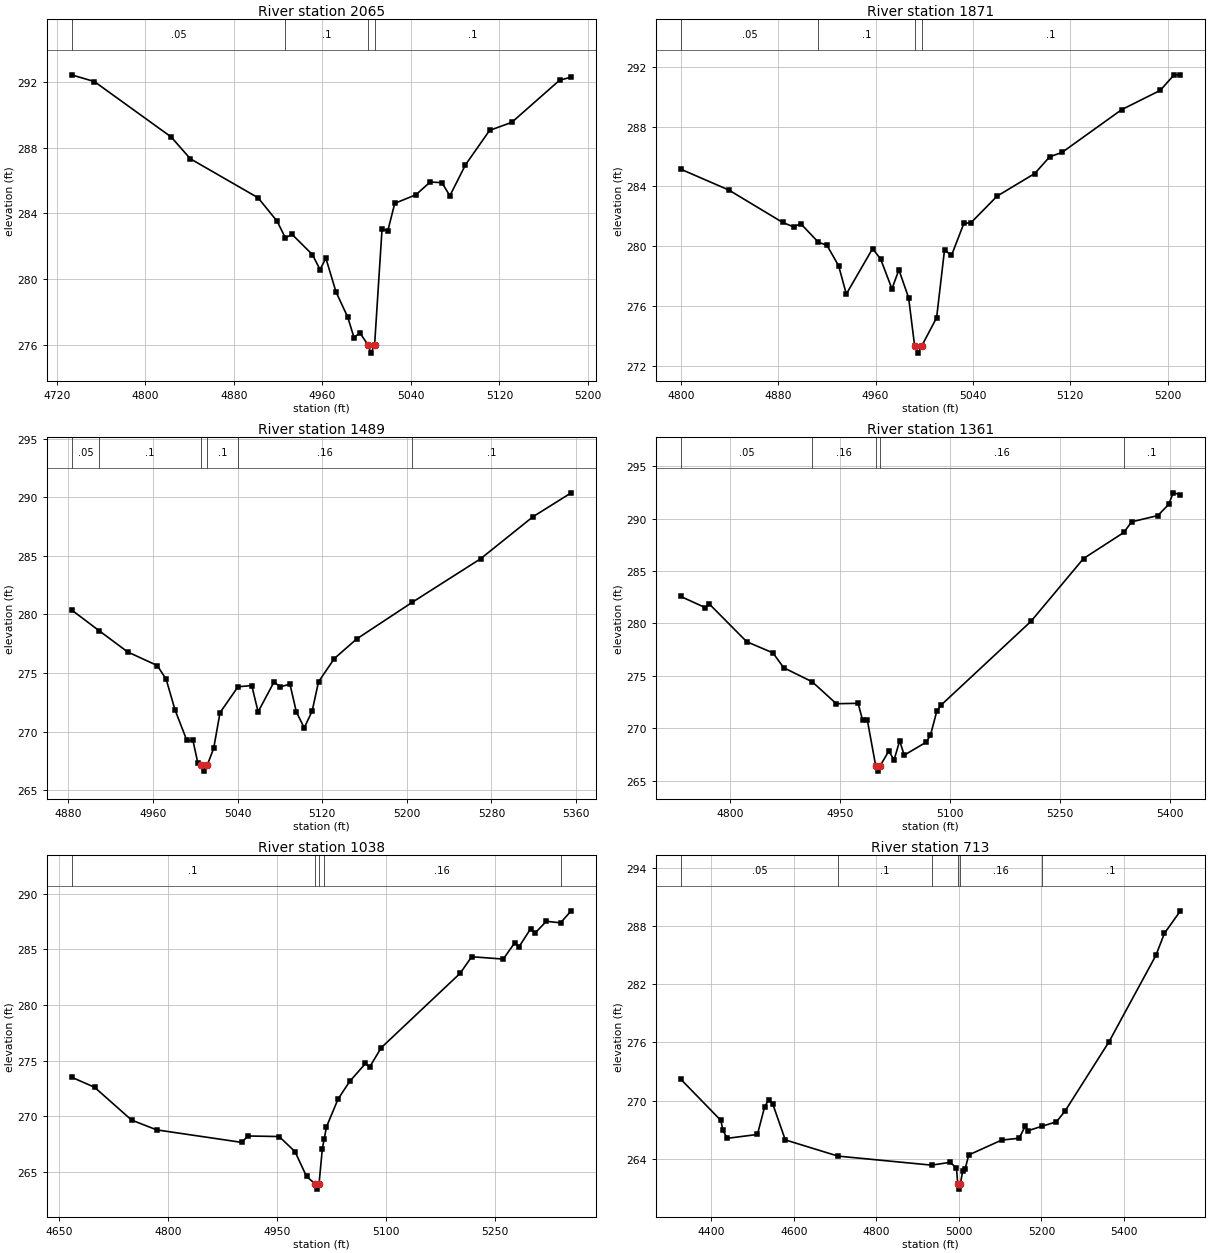
Type RM Length L Ch R = 1 ,2065    ,194,194,194
BEGIN DESCRIPTION:
UNT04968 IN WICK 3.0
END DESCRIPTION:
XS GIS Cut Line= 2
      3583577.49     10258033.59      3584001.94     10257879.96
#Sta/Elev= 30
  4733.4  292.46    4754  292.05  4823.4  288.67  4840.7  287.34  4901.9  284.96
  4919.1  283.53  4926.6  282.51  4932.6  282.73    4951  281.49  4957.9  280.58
  4963.2  281.27  4972.3  279.22  4982.9  277.68  4988.6  276.43  4993.9  276.72
  5001.2  275.98  5003.9  275.48  5007.2  275.98  5013.9  283.03  5019.2  282.96
  5025.4  284.62  5044.5  285.14  5057.4  285.92    5068  285.88  5075.2  285.08
  5089.3  286.97  5111.1  289.07  5131.1  289.56  5174.3  292.13  5184.8  292.32
#Mann= 4 ,-1 , 0
  4733.4     .05       0  4926.6      .1       0  5001.2     .07       0
  5007.2      .1       0
Bank Sta=5001.2,5007.2
XS Rating Curve= 0 ,0
Exp/Cntr=0.3,0.1

Type RM Length L Ch R = 1 ,1871    ,382,382,382
BEGIN DESCRIPTION:
Mapping XS 4ae65332
END DESCRIPTION:
XS GIS Cut Line= 2
       3583749.4      10258174.2      3584106.14      10257971.1
#Sta/Elev= 30
    4800  285.15  4839.4  283.76  4883.7  281.59  4892.8  281.29  4898.5  281.51
    4913  280.27  4920.1  280.06  4929.7  278.69    4936   276.8  4957.6  279.84
  4964.2  279.14  4973.5  277.15  4979.2  278.42  4987.2  276.55  4992.1  273.35
  4994.8  272.85  4998.1  273.35  5010.2  275.22  5016.7  279.76  5022.4  279.38
  5032.6  281.53  5038.3  281.56  5059.9  283.35  5090.8  284.86  5103.1  285.98
  5113.2  286.27  5162.2  289.13  5193.9  290.42  5205.3  291.46  5210.5  291.46
#Mann= 4 ,-1 , 0
    4800     .05       0    4913      .1       0  4992.1     .07       0
  4998.1      .1       0
Bank Sta=4992.1,4998.1
XS Rating Curve= 0 ,0
Exp/Cntr=0.3,0.1

Type RM Length L Ch R = 1 ,1489    ,128,128,128
BEGIN DESCRIPTION:
UNT04968 IN WICK 2.0
END DESCRIPTION:
XS GIS Cut Line= 3
      3583942.09     10258441.65      3584042.11     10258391.64
      3584242.12     10258091.63
#Sta/Elev= 30
    4883  280.38  4909.3  278.59  4936.1  276.79  4964.1  275.63  4972.5  274.45
  4980.8  271.86    4992  269.24  4997.8  269.24  5002.3  267.35  5005.3  267.12
  5008.1  266.62  5011.3  267.12  5017.4  268.57  5023.4  271.61  5040.4  273.82
  5053.4  273.92  5059.4  271.68  5074.4  274.22  5080.5  273.81  5089.5  274.05
  5095.5  271.69    5103  270.31  5110.5  271.75  5116.5  274.24  5131.5  276.23
  5152.6   277.9    5205  281.02  5269.7  284.74  5319.3  288.33  5355.4  290.37
#Mann= 6 ,-1 , 0
    4883     .05       0  4909.3      .1       0  5005.3     .07       0
  5011.3      .1       0  5040.4     .16       0    5205      .1       0
Bank Sta=5005.3,5011.3
XS Rating Curve= 0 ,0
Exp/Cntr=0.3,0.1

Type RM Length L Ch R = 1 ,1361    ,323,323,323
BEGIN DESCRIPTION:
Mapping XS 328efe5f
END DESCRIPTION:
XS GIS Cut Line= 2
      3583913.46     10258627.95       3584472.5     10258239.05
#Sta/Elev= 30
  4732.8  282.57  4765.9  281.52  4771.9  281.84  4822.6  278.26  4858.4  277.19
  4873.2  275.77    4912  274.43  4944.8  272.34  4974.5  272.38  4980.6  270.77
    4987  270.81  4998.5  266.41  5001.2  265.91  5004.5  266.41  5016.3  267.82
  5023.5  266.98  5031.2  268.81  5037.3  267.43    5067  268.66  5073.1  269.33
  5081.8  271.64  5087.9  272.23  5210.1   280.2  5281.7  286.19  5336.7  288.68
  5347.2  289.69  5382.9  290.29  5397.8  291.35  5403.9  292.46  5413.8  292.29
#Mann= 5 ,-1 , 0
  4732.8     .05       0    4912     .16       0  4998.5     .07       0
  5004.5     .16       0  5336.7      .1       0
Bank Sta=4998.5,5004.5
XS Rating Curve= 0 ,0
Exp/Cntr=0.3,0.1

Type RM Length L Ch R = 1 ,1038    ,325,325,325
BEGIN DESCRIPTION:
Mapping XS 4f2805fc
END DESCRIPTION:
XS GIS Cut Line= 3
      3584070.95     10258748.73      3584283.59     10258707.51
      3584513.21     10258295.93
#Sta/Elev= 30
  4666.9  273.51  4698.6   272.6  4749.6  269.65  4784.1  268.77  4901.7  267.64
  4909.3  268.22  4952.7  268.17  4974.5  266.82  4990.4  264.59  5001.7  263.94
  5004.5  263.44  5007.7  263.94  5012.2  267.07  5014.7  267.93  5017.9  269.04
  5033.9  271.55  5049.9  273.13  5071.6  274.74  5077.3  274.42  5093.3  276.16
  5201.9  282.85  5217.8  284.34  5261.3  284.13  5277.3  285.62    5283  285.24
    5299  286.86  5304.7  286.45  5320.7  287.53  5340.1  287.39  5354.8  288.47
#Mann= 5 ,-1 , 0
  4666.9      .1       0  5001.7     .07       0  5007.7      .1       0
  5014.7     .16       0  5340.1      .1       0
Bank Sta=5001.7,5007.7
XS Rating Curve= 0 ,0
Exp/Cntr=0.3,0.1

Type RM Length L Ch R = 1 ,713     ,618,618,618
BEGIN DESCRIPTION:
UNT04968 IN WICK 1.0
END DESCRIPTION:
XS GIS Cut Line= 4
       3584090.5     10258815.46      3584479.41      10258860.6
      3584753.71     10258426.57      3584559.29     10258190.49
#Sta/Elev= 30
  4325.9  272.21    4423  267.97  4428.2  266.94  4438.3  266.12  4511.7  266.52
  4528.9  269.33  4538.9  270.11    4549  269.64  4579.2  265.96    4707  264.29
  4933.6  263.36  4978.8  263.65    4994  263.06  4997.1  261.39  4999.9  260.89
  5003.1  261.39  5009.3  262.78  5015.2  263.01  5023.8  264.41  5103.4  265.94
  5145.8  266.13  5161.1  267.42    5167   266.9  5200.6  267.36  5236.1  267.82
  5256.8  268.91  5363.7  276.07  5477.1  284.95  5497.9  287.23  5536.7  289.55
#Mann= 6 ,-1 , 0
  4325.9     .05       0    4707      .1       0  4933.6     .16       0
  4997.1     .07       0  5003.1     .16       0  5200.6      .1       0
Bank Sta=4997.1,5003.1
XS Rating Curve= 0 ,0
Exp/Cntr=0.3,0.1

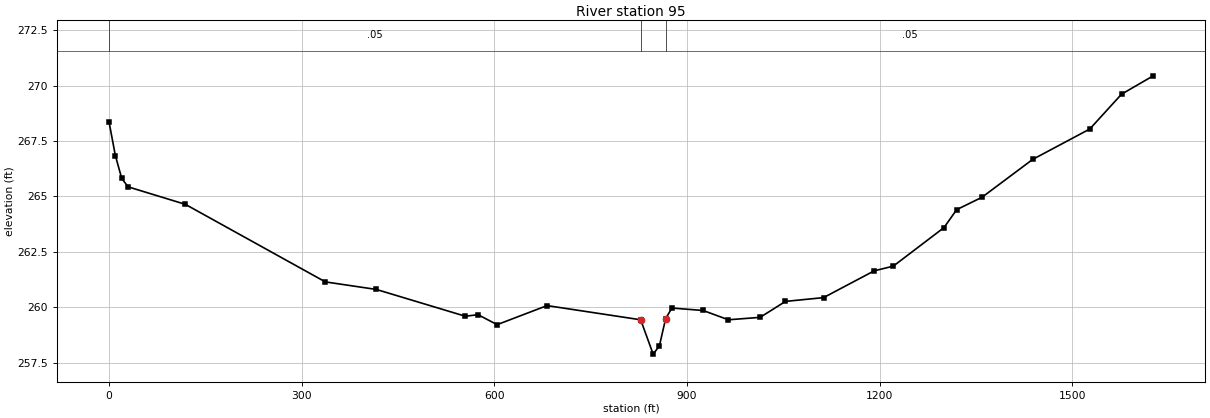
Type RM Length L Ch R = 1 ,95      ,0,0,
XS GIS Cut Line= 4
     3584320.882    10258871.691      3584917.67    10258986.708
     3585175.917    10258803.331     3584968.669    10258129.503
#Sta/Elev= 30
       0  268.37    9.91  266.84   19.82  265.81   29.72  265.43  118.89  264.64
  336.86  261.14  416.12   260.8  554.83  259.59  574.65  259.66  604.37  259.21
   682.1  260.07  827.85  259.43  847.28  257.88     857  258.25  866.71  259.48
  876.43  259.96  925.01  259.85   964.5  259.43 1013.86  259.54 1053.35  260.26
 1112.58  260.43 1191.56  261.64 1221.17  261.85 1300.15  263.59 1319.89   264.4
 1359.38  264.96 1438.36  266.67  1527.2  268.04 1576.56  269.61 1625.92  270.44
#Mann= 3 , 0 , 0
       0     .05       0  827.85     .03       0  866.71     .05       0
Bank Sta=827.85,866.71
XS Rating Curve= 0 ,0
Exp/Cntr=0.3,0.1

Chan Stop Cuts=-1
Use User Specified Reach Order=0
Composite Channel Slope=5