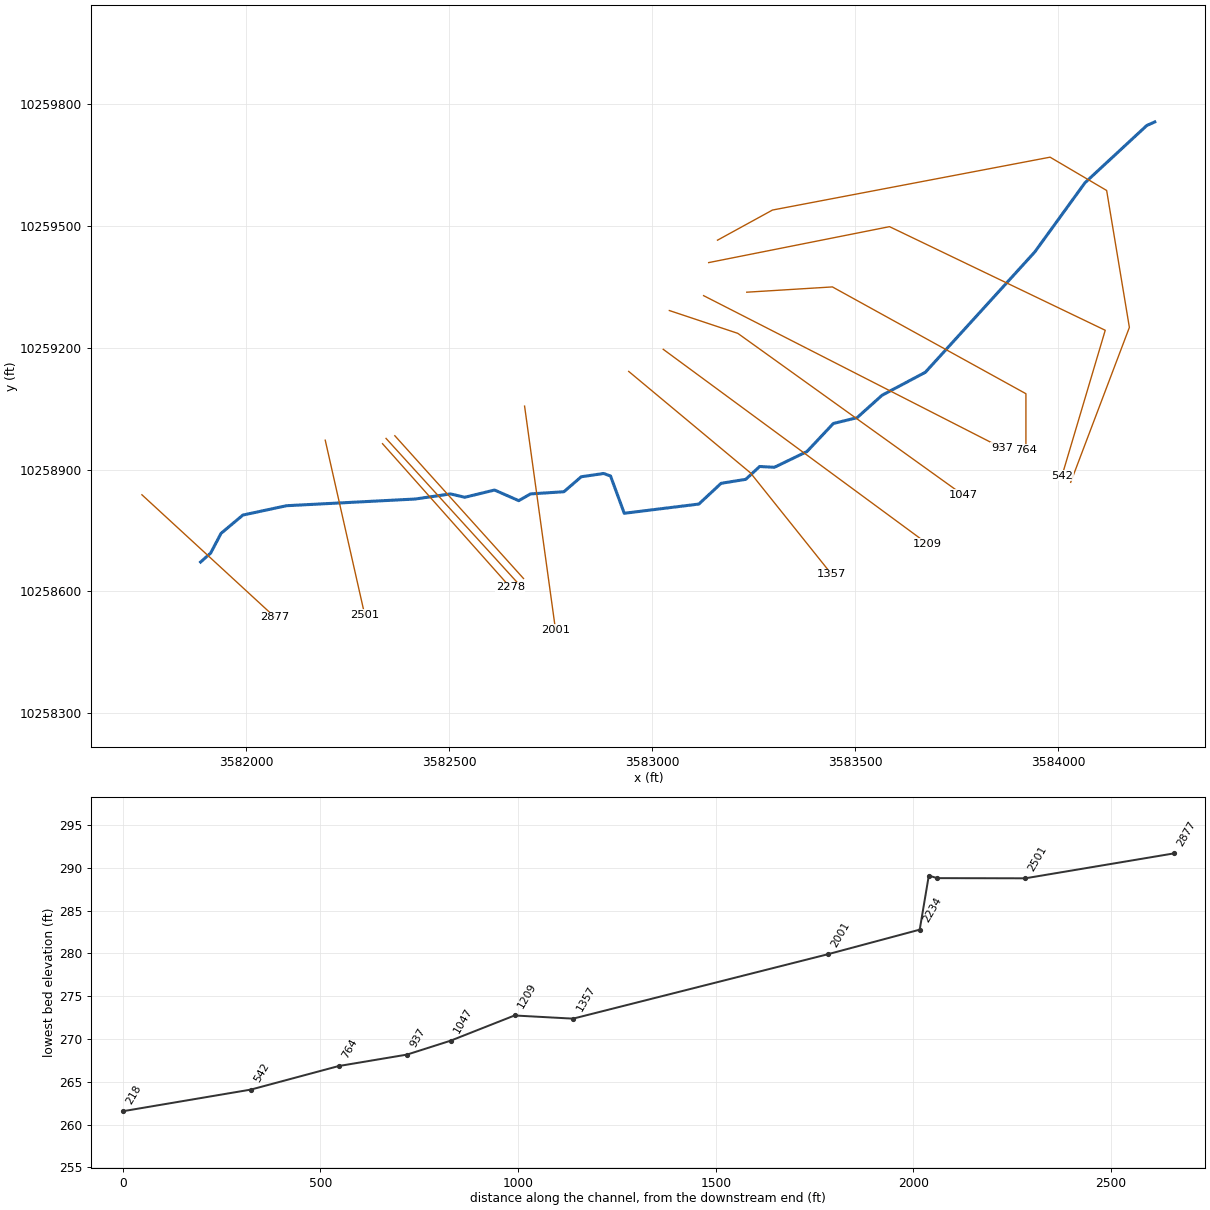
--- BOWMANCREEKTRIB9.prj (project) ---

Proj Title=BOWMAN CREEK TRIB 9
Current Plan=p01
Default Exp/Contr=0.3,0.1
English Units
Geom File=g01
Flow File=f01
Plan File=p01
Y Axis Title=Elevation
X Axis Title(PF)=Main Channel Distance
X Axis Title(XS)=Station
BEGIN DESCRIPTION:
UNT998 IN WICK
END DESCRIPTION:
DSS Export Rating Curves= 0
DSS Export Rating Curve Sorted= 0
DSS Export Volume Flow Curves= 0
DXF Filename=UNT998 IN WICK.
DXF OffsetX= 0
DXF OffsetY= 0
DXF ScaleX= 1
DXF ScaleY= 10

--- BOWMANCREEKTRIB9.p01 (plan) ---

Plan Title=Multiple Run
Short Identifier=Multiple
Geom File=g01
Flow File=f01
Subcritical Flow
K Sum by GR= 0
Std Step Tol= 0.01
Critical Tol= 0.01
Num of Std Step Trials= 20
Max Error Tol= 0.3
Flow Tol Ratio= 0.001
Split Flow NTrial= 30
Split Flow Tol= 0.02
Split Flow Ratio= 0.02
Log Output Level= 0
Friction Slope Method= 1
Unsteady Friction Slope Method= 2
Unsteady Bridges Friction Slope Method= 1
Parabolic Critical Depth
Global Vel Dist=  1 , 1 , 1
Global Log Level= 0
CheckData=True
Encroach Param= -1, 0, 0, 0
BEGIN DESCRIPTION:
Multiple Run
END DESCRIPTION:

--- BOWMANCREEKTRIB9.f01 (steady flow) ---

Flow Title=Multiple
Program Version=4.10
Number of Profiles= 7
Profile Names=10-year,25-year,50-year,1pct_min,100-year,1pct_plu,500-year
River Rch & RM=UNT998 IN WICK,Reach-1         ,2877
     172     215     248     210     285     385     375
River Rch & RM=BOWMANCRTRIB9,Reach-1         ,2877
     172     215     248     210     285     385     375
Boundary for River Rch & Prof#=BOWMANCRTRIB9,Reach-1         , 1
Up Type= 0
Dn Type= 3
Dn Slope=0.005
Boundary for River Rch & Prof#=BOWMANCRTRIB9,Reach-1         , 2
Up Type= 0
Dn Type= 3
Dn Slope=0.005
Boundary for River Rch & Prof#=BOWMANCRTRIB9,Reach-1         , 3
Up Type= 0
Dn Type= 3
Dn Slope=0.005
Boundary for River Rch & Prof#=BOWMANCRTRIB9,Reach-1         , 4
Up Type= 0
Dn Type= 3
Dn Slope=0.005
Boundary for River Rch & Prof#=BOWMANCRTRIB9,Reach-1         , 5
Up Type= 0
Dn Type= 3
Dn Slope=0.005
Boundary for River Rch & Prof#=BOWMANCRTRIB9,Reach-1         , 6
Up Type= 0
Dn Type= 3
Dn Slope=0.005
Boundary for River Rch & Prof#=BOWMANCRTRIB9,Reach-1         , 7
Up Type= 0
Dn Type= 3
Dn Slope=0.005
DSS Import GetInterval= 0
DSS Import GetPeak= 0
DSS Import FillOption= 0

--- BOWMANCREEKTRIB9.g01 (geometry) ---

Geom Title=Existing Conditions
Program Version=4.10

River Reach=BOWMANCRTRIB9   ,Reach-1
Reach XY= 30
      3581887.73     10258672.12      3581912.51      10258694.1
      3581938.11     10258742.71      3581991.93     10258787.85
      3582099.14     10258810.85      3582415.98     10258827.34
      3582503.22     10258839.93      3582538.37     10258831.68
      3582611.72     10258849.48       3582671.3     10258823.34
      3582700.27     10258839.93      3582782.51     10258845.32
      3582825.21     10258882.19      3582880.42     10258890.26
      3582897.34     10258884.01      3582931.16      10258792.2
      3583114.93       10258815.      3583169.64     10258866.04
      3583230.45     10258875.89      3583264.53     10258907.45
       3583300.9     10258905.54      3583381.04     10258944.19
      3583446.09     10259013.43      3583504.53     10259027.68
      3583565.98     10259082.89       3583672.6     10259139.48
      3583942.13     10259435.84      3584065.83     10259606.41
      3584217.92     10259747.29      3584237.64     10259756.11

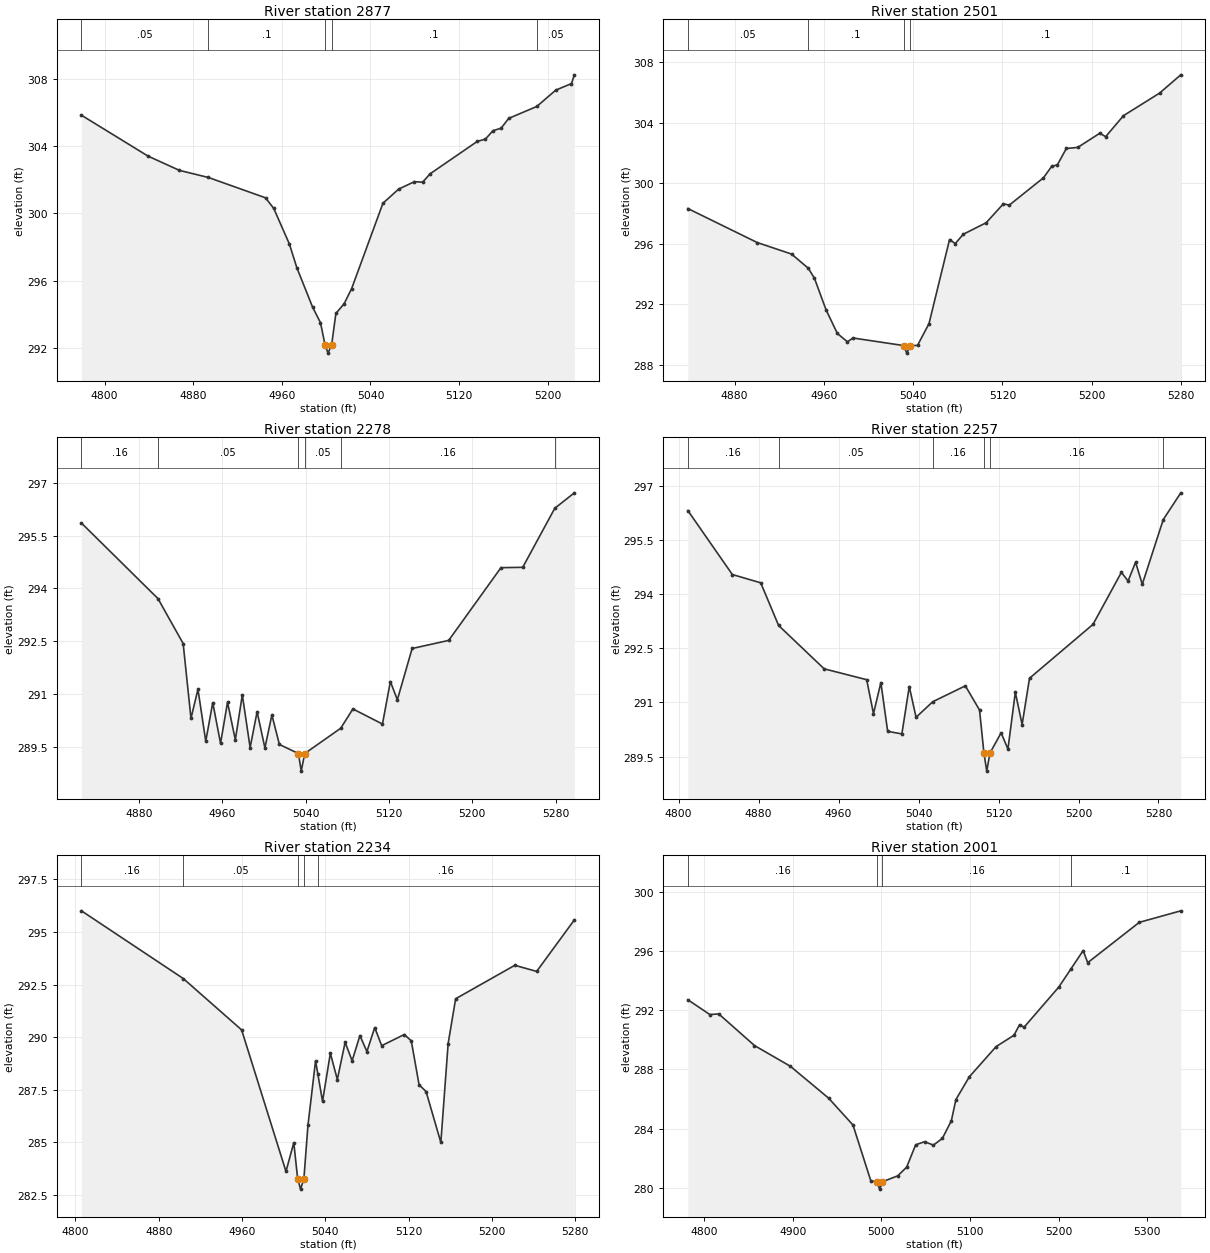
Type RM Length L Ch R = 1 ,2877    ,376,376,376
BEGIN DESCRIPTION:
UNT998 IN WICK 6.0
END DESCRIPTION:
XS GIS Cut Line= 2
      3581743.32      10258837.8      3582070.73     10258536.42
#Sta/Elev= 30
  4779.1  305.83  4839.2   303.4  4867.6  302.55  4893.7  302.13  4945.3  300.92
  4952.7  300.29  4966.8  298.18  4973.6  296.76  4987.8  294.42  4994.9   293.5
    4999  292.19  5001.7  291.69    5005  292.19  5008.8  294.05  5016.2  294.62
    5023  295.52  5051.3   300.6  5065.5  301.44  5079.7  301.88  5087.1  301.85
  5093.9  302.35  5136.4  304.27  5143.8  304.41  5150.6  304.91    5158  305.06
  5164.8  305.64  5190.2  306.35  5207.3  307.32  5221.5  307.71  5224.1  308.23
#Mann= 5 ,-1 , 0
  4779.1     .05       0  4893.7      .1       0    4999     .07       0
    5005      .1       0  5190.2     .05       0
Bank Sta=4999,5005
XS Rating Curve= 0 ,0
Exp/Cntr=0.3,0.1

Type RM Length L Ch R = 1 ,2501    ,223,223,223
BEGIN DESCRIPTION:
UNT998 IN WICK 5.0
END DESCRIPTION:
XS GIS Cut Line= 2
      3582194.75     10258972.28       3582292.1     10258541.65
#Sta/Elev= 30
  4838.2  298.34  4900.4  296.09  4931.1  295.33  4946.1  294.39  4951.6  293.73
  4961.9  291.66  4972.1  290.08  4981.1  289.53  4986.2  289.78  5031.5  289.28
  5034.3  288.78  5037.5  289.28  5043.9  289.29  5054.2  290.73  5072.6  296.29
  5077.7  296.02  5084.9  296.64  5105.4   297.4  5120.9  298.66    5126  298.56
  5156.7  300.37  5164.1  301.13  5169.2  301.23  5177.2  302.31  5187.4  302.38
  5207.2  303.32  5212.4  303.09  5228.4  304.48  5260.7  305.97  5279.7  307.18
#Mann= 4 ,-1 , 0
  4838.2     .05       0  4946.1      .1       0  5031.5     .07       0
  5037.5      .1       0
Bank Sta=5031.5,5037.5
XS Rating Curve= 0 ,0
Exp/Cntr=0.3,0.1

Type RM Length L Ch R = 1 ,2278    ,21,21,21
BEGIN DESCRIPTION:
Mapping XS 8ce63c75
END DESCRIPTION:
XS GIS Cut Line= 2
       3582335.8     10258963.65      3582650.44     10258609.94
#Sta/Elev= 30
  4824.6  295.86  4898.1  293.71  4922.3  292.43  4929.8   290.3  4936.5  291.13
    4944  289.65  4950.7  290.75  4958.2  289.59  4964.9  290.76  4972.4  289.69
  4979.1  290.97  4986.6  289.47  4993.3  290.49  5000.8  289.46  5007.5   290.4
  5014.7  289.56    5033   289.3  5035.7   288.8    5039   289.3  5073.6  290.02
  5085.3  290.57  5113.7  290.14  5121.3  291.35    5128  290.83  5142.2  292.29
  5177.3  292.52  5227.5  294.59  5248.4   294.6  5279.2  296.28    5298  296.72
#Mann= 6 ,-1 , 0
  4824.6     .16       0  4898.1     .05       0    5033     .03       0
    5039     .05       0  5073.6     .16       0  5279.2      .1       0
Bank Sta=5033,5039
XS Rating Curve= 0 ,0
Exp/Cntr=0.3,0.1

Type RM Length L Ch R = 1 ,2257    ,23,23,23
BEGIN DESCRIPTION:
Mapping XS e6ac9a09
END DESCRIPTION:
XS GIS Cut Line= 2
      3582344.51     10258976.63      3582676.53     10258612.06
#Sta/Elev= 30
  4809.2  296.31  4853.7  294.54  4882.1  294.31    4900  293.13  4945.6  291.93
  4988.1  291.63  4994.9  290.69  5002.3  291.55  5009.1   290.2  5023.3  290.13
  5030.7  291.44  5037.5  290.59  5054.2  291.02  5086.8  291.46    5101  290.79
  5105.4   289.6  5108.2   289.1  5111.4   289.6  5122.6  290.16  5129.4  289.71
  5136.8  291.28  5143.6  290.39    5151  291.67  5214.5  293.16  5242.9   294.6
  5249.6  294.36  5257.1  294.88  5263.8  294.27  5284.8  296.06  5302.3   296.8
#Mann= 6 ,-1 , 0
  4809.2     .16       0    4900     .05       0  5054.2     .16       0
  5105.4     .03       0  5111.4     .16       0  5284.8      .1       0
Bank Sta=5105.4,5111.4
XS Rating Curve= 0 ,0
Exp/Cntr=0.3,0.1

Type RM Length L Ch R = 1 ,2234    ,233,233,233
BEGIN DESCRIPTION:
Mapping XS 2bab61ee
END DESCRIPTION:
XS GIS Cut Line= 2
      3582366.18     10258983.18      3582683.04     10258631.59
#Sta/Elev= 30
  4805.8  296.01  4903.6  292.79  4959.6  290.35  5002.2  283.62  5009.7  284.99
  5013.4  283.28  5016.2  282.78  5019.4  283.28  5023.3  285.81  5030.6  288.88
  5032.8  288.25  5037.3  286.95  5044.8  289.24  5051.5  287.99    5059  289.76
  5065.7  288.88  5073.2  290.08  5079.9  289.32  5087.4  290.46  5094.1   289.6
  5115.8  290.13  5122.5  289.83    5130  287.74  5136.7  287.42  5150.9     285
  5157.9   289.7  5165.1  291.83  5221.9  293.42  5242.9  293.13  5279.1  295.58
#Mann= 5 ,-1 , 0
  4805.8     .16       0  4903.6     .05       0  5013.4     .03       0
  5019.4     .05       0  5032.8     .16       0
Bank Sta=5013.4,5019.4
XS Rating Curve= 0 ,0
Exp/Cntr=0.3,0.1

Type RM Length L Ch R = 1 ,2001    ,644,644,644
BEGIN DESCRIPTION:
UNT998 IN WICK 4.0
END DESCRIPTION:
XS GIS Cut Line= 2
      3582685.66     10259056.17      3582761.88     10258505.32
#Sta/Elev= 30
  4781.7  292.72  4806.5  291.72  4816.6  291.76  4856.9  289.62  4897.3  288.22
  4940.5  286.06    4968  284.24  4988.2  280.45  4995.3   280.4    4998   279.9
  5001.3   280.4  5018.5   280.8  5028.6  281.39  5038.7   282.9  5048.7  283.11
  5058.8  282.88  5068.9  283.34    5079  284.53  5084.1  285.96  5099.2   287.5
  5129.5  289.55  5149.7  290.32  5155.9  291.03    5161  290.86  5200.2  293.58
  5213.8   294.8  5227.7  296.05  5232.8  295.23    5291  297.96  5337.8  298.74
#Mann= 4 ,-1 , 0
  4781.7     .16       0  4995.3     .07       0  5001.3     .16       0
  5213.8      .1       0
Bank Sta=4995.3,5001.3
XS Rating Curve= 0 ,0
Exp/Cntr=0.3,0.1

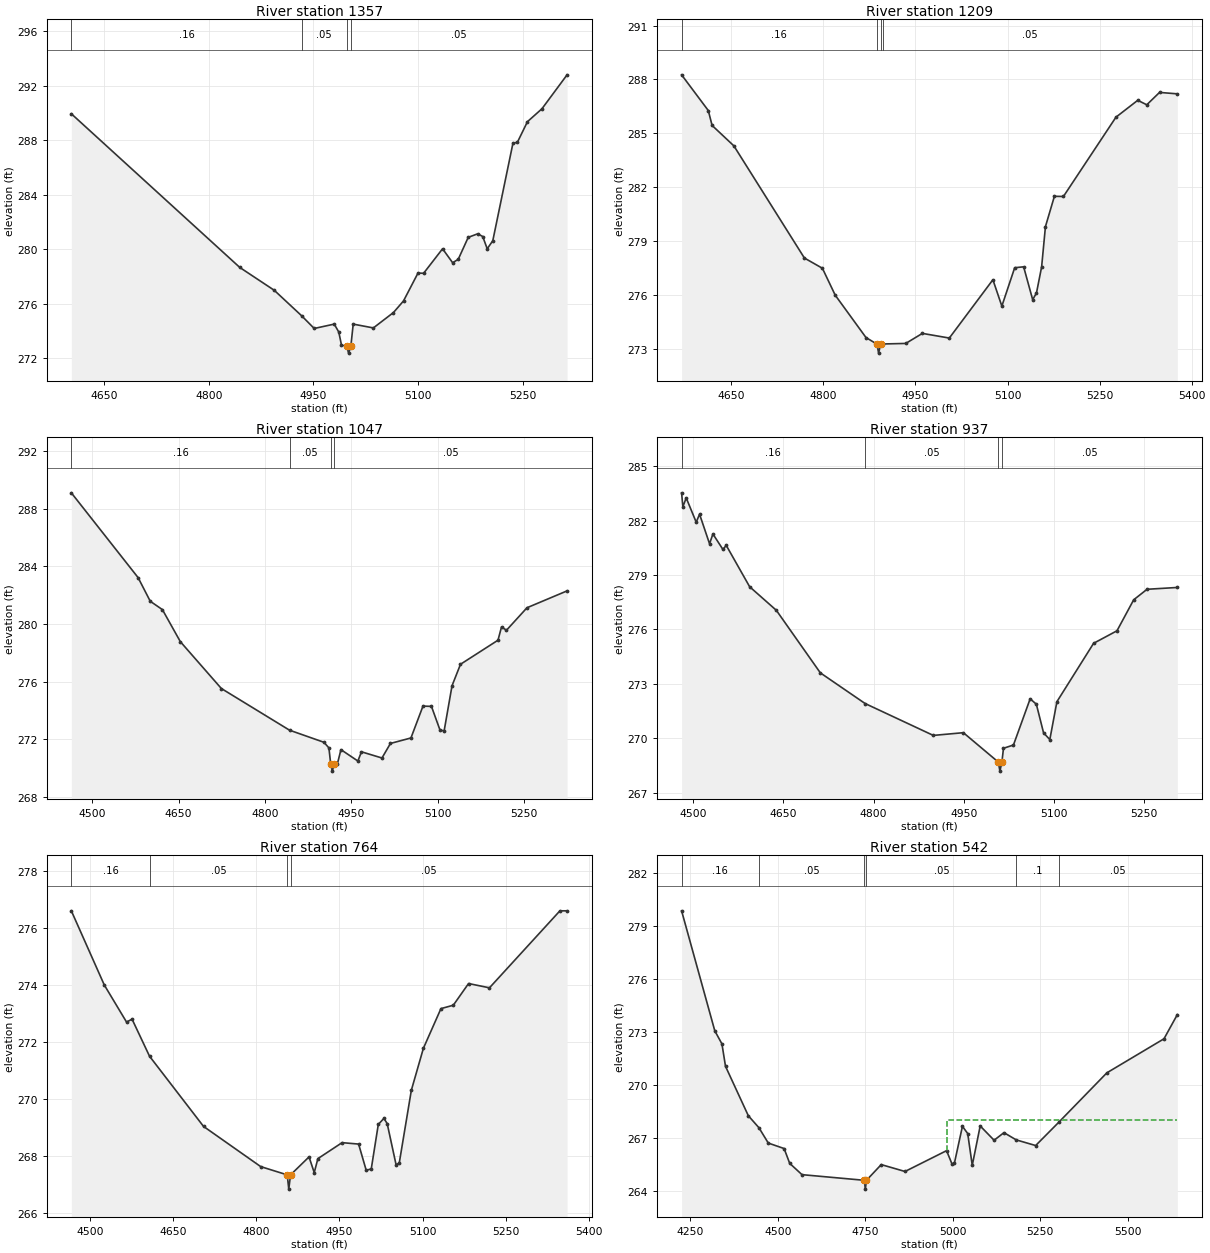
Type RM Length L Ch R = 1 ,1357    ,148,148,148
BEGIN DESCRIPTION:
UNT998 IN WICK 3.0
END DESCRIPTION:
XS GIS Cut Line= 3
      3582942.09     10259141.66      3583242.11     10258891.64
      3583442.11     10258641.63
#Sta/Elev= 30
    4603  289.95  4844.5  278.67    4894  276.99    4933  275.13  4951.2  274.19
  4979.9  274.51  4986.4  273.93  4990.3  272.97  4997.7  272.88  5000.5  272.38
  5003.7  272.88  5007.1  274.51    5036  274.23  5064.8  275.36  5079.2  276.21
    5100  278.26    5108  278.24  5135.2  280.04  5149.6  279.02  5157.6  279.26
    5172  280.88  5185.6  281.14  5192.8  280.94  5199.2  280.04  5207.2  280.63
  5236.1  287.79  5242.5  287.86  5256.9  289.37  5277.7  290.32  5313.7  292.81
#Mann= 4 ,-1 , 0
    4603     .16       0    4933     .05       0  4997.7     .04       0
  5003.7     .05       0
Bank Sta=4997.7,5003.7
XS Rating Curve= 0 ,0
Exp/Cntr=0.3,0.1

Type RM Length L Ch R = 1 ,1209    ,162,162,162
BEGIN DESCRIPTION:
Mapping XS d25bc581
END DESCRIPTION:
XS GIS Cut Line= 2
      3583027.08     10259196.13      3583677.58     10258717.35
#Sta/Elev= 30
    4569  288.26  4612.5  286.27  4618.7  285.44  4654.2   284.3  4769.1  278.05
  4798.4  277.48  4819.3  275.98  4869.4  273.62  4887.3  273.25    4890  272.75
  4893.3  273.25  4896.9  273.26  4934.2  273.29  4961.3  273.85  5005.2  273.59
  5076.2  276.84  5090.8  275.37  5111.7  277.51  5126.3  277.56    5141  275.73
  5147.2   276.1  5155.6  277.56  5161.8   279.8  5176.4  281.49  5191.1  281.48
  5276.7   285.9  5312.2  286.84  5326.9  286.59  5347.7  287.28  5376.7   287.2
#Mann= 4 ,-1 , 0
    4569     .16       0  4887.3     .04       0  4893.3     .16       0
  4896.9     .05       0
Bank Sta=4887.3,4893.3
XS Rating Curve= 0 ,0
Exp/Cntr=0.3,0.1

Type RM Length L Ch R = 1 ,1047    ,110,110,110
BEGIN DESCRIPTION:
UNT998 IN WICK 2.0
END DESCRIPTION:
XS GIS Cut Line= 3
      3583042.13     10259291.63       3583210.7     10259235.44
      3583765.51     10258837.42
#Sta/Elev= 30
  4463.8   289.1  4579.7  283.22  4600.8  281.58  4621.9     281    4653  278.78
  4724.2  275.53  4842.5  272.64  4902.3   271.8  4910.9  271.41    4914   270.3
  4916.8   269.8    4920   270.3  4925.6   270.3  4931.8  271.29  4961.2   270.5
  4967.4  271.14    5003  270.71  5017.7  271.72  5053.3   272.1  5074.2  274.31
  5088.9  274.29  5103.7  272.65  5110.9  272.59  5124.6  275.72  5139.3  277.21
  5204.4  278.88  5210.5   279.8  5219.1  279.57  5254.7  281.13  5324.3   282.3
#Mann= 4 ,-1 , 0
  4463.8     .16       0  4842.5     .05       0    4914     .04       0
    4920     .05       0
Bank Sta=4914,4920
XS Rating Curve= 0 ,0
Exp/Cntr=0.3,0.1

Type RM Length L Ch R = 1 ,937     ,173,173,173
BEGIN DESCRIPTION:
Mapping XS 0d00e6d5
END DESCRIPTION:
XS GIS Cut Line= 2
      3583126.57     10259328.24      3583860.97     10258953.23
#Sta/Elev= 30
  4480.7  283.53  4482.8  282.76  4488.4  283.25    4505  281.91  4510.6  282.35
  4527.2  280.72  4532.8  281.26  4549.4  280.41    4555  280.63  4593.9  278.35
  4638.3  277.05  4711.5   273.6  4785.9  271.91  4899.4  270.15  4949.4   270.3
  5007.5  268.68  5010.2  268.18  5013.5  268.68  5016.1  269.44  5032.7  269.62
  5060.5  272.17  5070.8  271.87  5082.8  270.29  5093.2  269.92    5105  272.01
    5166  275.23  5204.9  275.92  5232.7  277.63  5254.9  278.21  5305.3  278.31
#Mann= 4 ,-1 , 0
  4480.7     .16       0  4785.9     .05       0  5007.5     .04       0
  5013.5     .05       0
Bank Sta=5007.5,5013.5
XS Rating Curve= 0 ,0
Exp/Cntr=0.3,0.1

Type RM Length L Ch R = 1 ,764     ,222,222,222
BEGIN DESCRIPTION:
Mapping XS 6db5c7d4
END DESCRIPTION:
XS GIS Cut Line= 4
      3583232.82     10259336.74      3583443.75     10259349.77
      3583920.31     10259086.74      3583920.31     10258948.71
#Sta/Elev= 30
  4466.8   276.6  4526.2     274  4566.3   272.7  4576.3   272.8  4607.8   271.5
  4705.1  269.04  4808.2  267.63    4856  267.34  4858.8  266.84    4862  267.34
  4895.3  267.97  4904.7  267.42  4911.3  267.91  4954.9  268.47  4984.7  268.42
  4998.4   267.5  5007.5  267.55  5020.2  269.11  5030.3  269.32  5036.2  269.14
  5052.3  267.69    5058  267.76  5079.8  270.31  5101.5  271.78  5133.1  273.17
  5155.4  273.29  5182.9  274.05  5220.6   273.9  5347.6   276.6  5360.5   276.6
#Mann= 4 ,-1 , 0
  4466.8     .16       0  4607.8     .05       0    4856     .04       0
    4862     .05       0
Bank Sta=4856,4862
XS Rating Curve= 0 ,0
Exp/Cntr=0.3,0.1

Type RM Length L Ch R = 1 ,542     ,324,324,324
BEGIN DESCRIPTION:
UNT998 IN WICK 1.0
END DESCRIPTION:
XS GIS Cut Line= 4
      3583139.02     10259409.65      3583584.38      10259498.2
      3584115.63     10259242.99       3584009.3      10258885.1
#Sta/Elev= 30
  4224.8  279.86  4319.7  273.06  4340.1  272.32  4350.3  271.05  4415.5  268.25
  4445.8  267.57  4472.6   266.7  4517.8  266.39  4533.8  265.55  4568.9  264.91
  4747.1  264.59  4749.9  264.09  4753.1  264.59  4795.4  265.48  4863.3  265.09
  4982.1  266.27  4998.1  265.49  5004.7  265.58  5027.4  267.65  5042.5  267.24
  5055.5  265.44  5078.2  267.67  5117.9  266.86  5146.1  267.29  5181.2  266.88
  5236.7  266.56  5303.8   267.9  5440.2  270.68  5603.5  272.61  5641.6  273.98
#Mann= 6 ,-1 , 0
  4224.8     .16       0  4445.8     .05       0  4747.1     .04       0
  4753.1     .05       0  5181.2      .1       0  5303.8     .05       0
#XS Ineff= 2 , 0
                         4983.04          268.03
Permanent Ineff=
       F       F
Bank Sta=4747.1,4753.1
XS Rating Curve= 0 ,0
Exp/Cntr=0.3,0.1

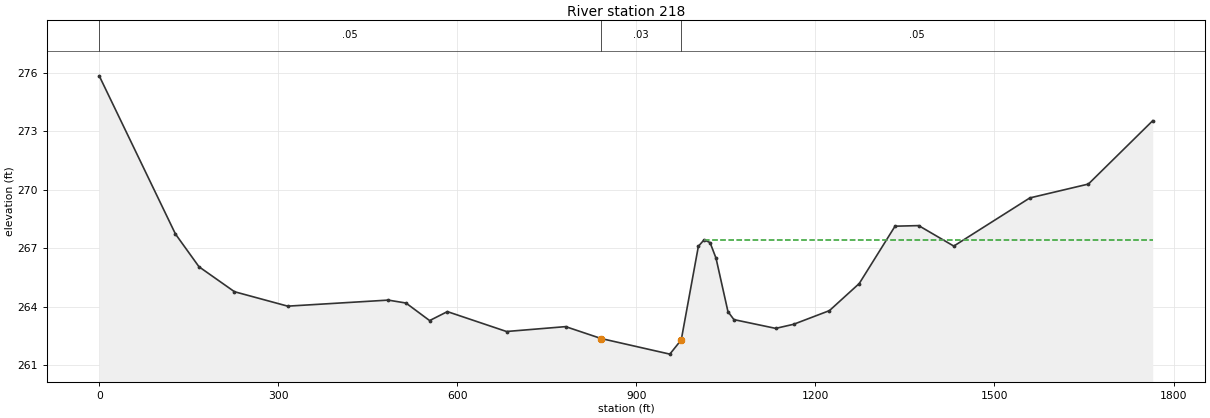
Type RM Length L Ch R = 1 ,218     ,0,0,0
XS GIS Cut Line= 6
     3583160.777    10259464.892     3583296.194     10259539.11
     3583979.787    10259669.319      3584119.11    10259587.287
       3584175.1    10259250.048     3584030.569    10258868.537
#Sta/Elev= 30
       0  275.83  127.72  267.72  167.18  266.04  226.64  264.76  315.81  264.02
  484.26  264.33  513.99  264.18  553.62  263.28  583.35  263.74  682.43  262.72
  781.52  262.97  840.97  262.36  956.09  261.56  975.21  262.29 1003.91  267.09
 1013.47  267.42 1023.47  267.28 1033.47  266.48 1053.47  263.74 1063.46  263.33
 1133.45  262.88 1163.45  263.09 1223.44  263.79 1273.43  265.18 1333.42  268.12
 1373.03  268.15 1431.86   267.1 1559.31  269.57 1657.35  270.28  1765.2  273.53
#Mann= 3 , 0 , 0
       0     .05       0  840.97     .03       0  975.21     .05       0
#XS Ineff= 2 , 0
                         1012.97          267.41
Permanent Ineff=
       F       F
Bank Sta=840.97,975.21
XS Rating Curve= 0 ,0
Exp/Cntr=0.3,0.1

Chan Stop Cuts=-1
Use User Specified Reach Order=0
Composite Channel Slope=5