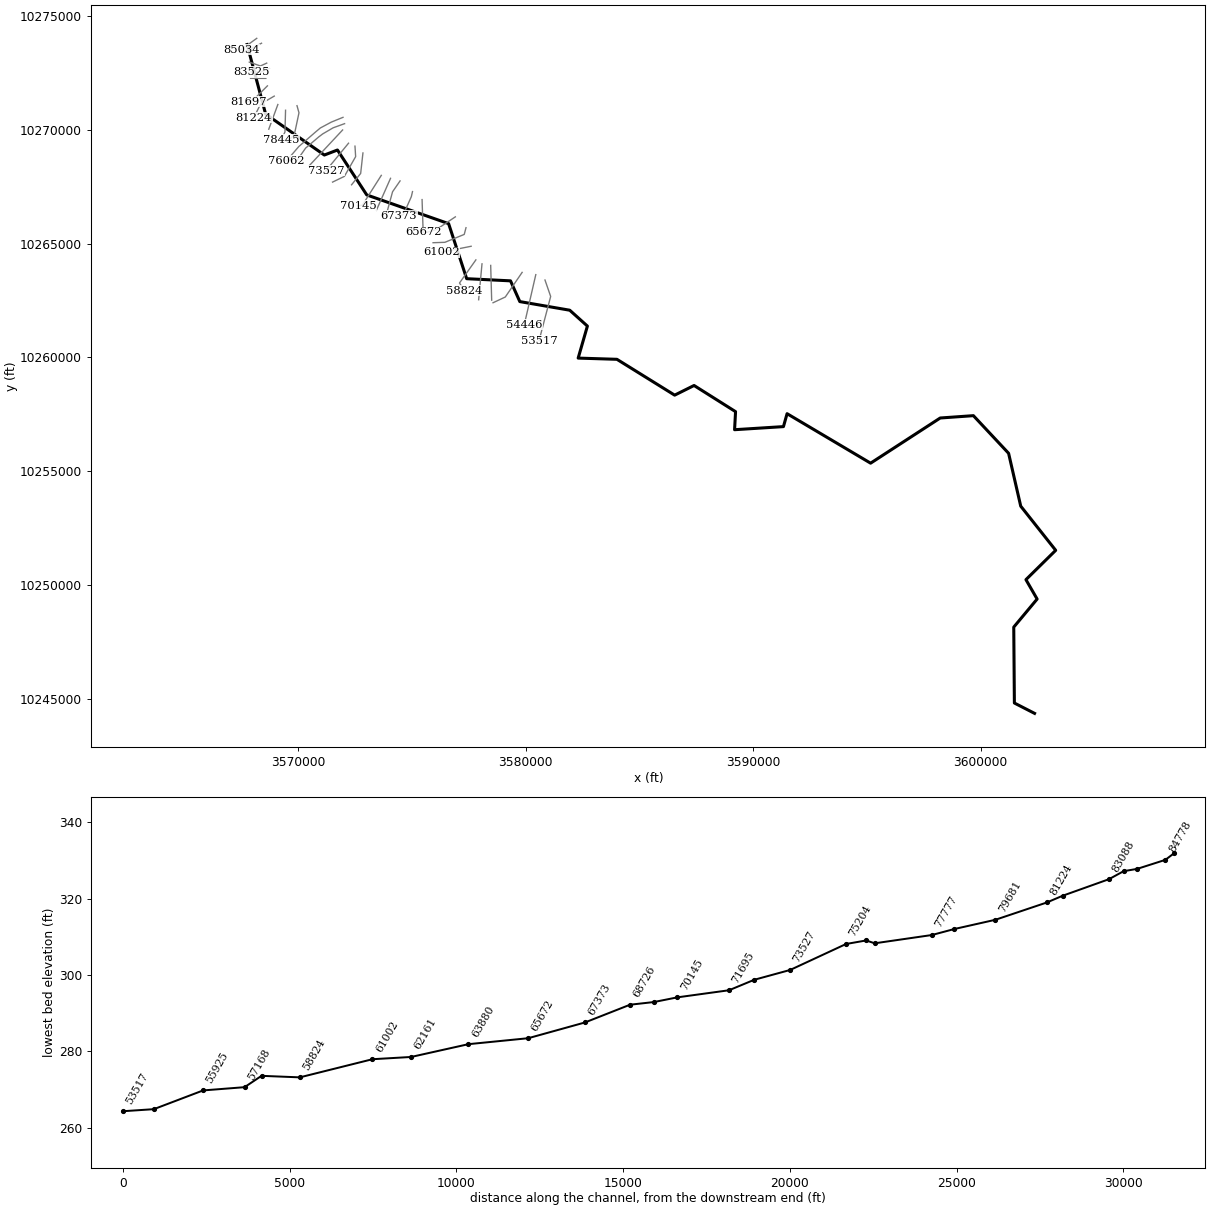
--- BOWMAN CREEK.prj (project) ---

Proj Title=BOWMAN CREEK Base Level Engineering
Current Plan=p01
Default Exp/Contr=0.3,0.1
English Units
Geom File=g01
Flow File=f01
Plan File=p01
Y Axis Title=Elevation
X Axis Title(PF)=Main Channel Distance
X Axis Title(XS)=Station
BEGIN DESCRIPTION:
BOWMAN CREEK
END DESCRIPTION:
DSS Export Rating Curves= 0
DSS Export Rating Curve Sorted= 0
DSS Export Volume Flow Curves= 0
DXF OffsetX= 0
DXF OffsetY= 0
DXF ScaleX= 1
DXF ScaleY= 10

--- BOWMAN CREEK.p01 (plan) ---

Plan Title=Multiple Run
Short Identifier=Multiple
Geom File=g01
Flow File=f01
Subcritical Flow
K Sum by GR= 0
Std Step Tol= 0.01
Critical Tol= 0.01
Num of Std Step Trials= 20
Max Error Tol= 0.3
Flow Tol Ratio= 0.001
Split Flow NTrial= 30
Split Flow Tol= 0.02
Split Flow Ratio= 0.02
Log Output Level= 0
Friction Slope Method= 1
Unsteady Friction Slope Method= 2
Unsteady Bridges Friction Slope Method= 1
Parabolic Critical Depth
Global Vel Dist=  1 , 1 , 1
Global Log Level= 0
CheckData=True
Encroach Param= -1, 0, 0, 0
BEGIN DESCRIPTION:
Multiple Run
END DESCRIPTION:

--- BOWMAN CREEK.f01 (steady flow) ---

Flow Title=Multiple
Program Version=4.10
Number of Profiles= 7
Profile Names=10-year,25-year,50-year,1pct_min,100-year,1pct_plu,500-year
River Rch & RM=BOWMAN CREEK,Reach-1         ,85034
     264     338     395     339     458     620     618
River Rch & RM=BOWMAN CREEK,Reach-1         ,81697
     488     646     771     675     913    1234    1281
River Rch & RM=BOWMAN CREEK,Reach-1         ,76062
     778    1055    1283    1140    1542    2085    2234
River Rch & RM=BOWMAN CREEK,Reach-1         ,70145
     962    1316    1607    1435    1940    2624    2835
River Rch & RM=BOWMAN CREEK,Reach-1         ,65672
    1103    1518    1862    1668    2256    3051    3321
River Rch & RM=BOWMAN CREEK,Reach-1         ,63880
    1180    1625    1994    1787    2417    3268    3559
River Rch & RM=BOWMAN CREEK,Reach-1         ,58824
    1350    1872    2306    2073    2804    3792    4159
River Rch & RM=BOWMAN CREEK,Reach-1         ,55925
    1425    1974    2432    2186    2956    3997    4380
River Rch & RM=BOWMAN CREEK,Reach-1         ,51745
    1668    2324    2872    2588    3500    4734    5216
River Rch & RM=BOWMAN CREEK,Reach-1         ,47270
    1851    2589    3210    2901    3924    5306    5881
River Rch & RM=BOWMAN CREEK,Reach-1         ,45497
    1851    2589    3210    2901    3924    5306    5881
River Rch & RM=BOWMAN CREEK,Reach-1         ,37141
    1935    2711    3365    3044    4116    5567    6181
River Rch & RM=BOWMAN CREEK,Reach-1         ,35026
    2075    2913    3620    3279    4434    5997    6674
River Rch & RM=BOWMAN CREEK,Reach-1         ,31201
    2096    2944    3659    3315    4483    6062    6748
River Rch & RM=BOWMAN CREEK,Reach-1         ,27520
    2143    3003    3726    3369    4556    6161    6830
Boundary for River Rch & Prof#=BOWMAN CREEK,Reach-1         , 1
Up Type= 0
Dn Type= 3
Dn Slope=0.00107
Boundary for River Rch & Prof#=BOWMAN CREEK,Reach-1         , 2
Up Type= 0
Dn Type= 3
Dn Slope=0.00107
Boundary for River Rch & Prof#=BOWMAN CREEK,Reach-1         , 3
Up Type= 0
Dn Type= 3
Dn Slope=0.00107
Boundary for River Rch & Prof#=BOWMAN CREEK,Reach-1         , 4
Up Type= 0
Dn Type= 3
Dn Slope=0.00107
Boundary for River Rch & Prof#=BOWMAN CREEK,Reach-1         , 5
Up Type= 0
Dn Type= 3
Dn Slope=0.00107
Boundary for River Rch & Prof#=BOWMAN CREEK,Reach-1         , 6
Up Type= 0
Dn Type= 3
Dn Slope=0.00107
Boundary for River Rch & Prof#=BOWMAN CREEK,Reach-1         , 7
Up Type= 0
Dn Type= 3
Dn Slope=0.00107
DSS Import GetInterval= 0
DSS Import GetPeak= 0
DSS Import FillOption= 0

--- BOWMAN CREEK.g01 (geometry) ---

Geom Title=Existing Conditions
Program Version=4.10

River Reach=BOWMAN CREEK    ,Reach-1
Reach XY= 30
      3567749.28     10273758.76      3568563.12     10270702.67
      3571145.12     10268900.71      3571722.07     10269121.13
      3573009.67      10267146.9      3576608.73     10265884.09
      3577402.82     10263463.63      3579330.85     10263368.85
       3579739.6     10262456.62      3581934.84      10262077.6
      3582710.88     10261380.12      3582305.02     10259972.34
      3584009.15     10259919.22      3586547.63     10258343.55
      3587400.83     10258768.34      3589224.69     10257618.09
      3589182.48     10256824.24       3591330.8     10256959.88
      3591490.23      10257528.7      3595162.52     10255352.57
      3598223.17     10257338.76      3599682.38     10257441.51
       3601229.6     10255787.41      3601763.23     10253463.11
       3603300.8      10251521.1      3601992.11     10250231.64
      3602484.05     10249378.24      3601456.46      10248145.1
      3601484.14     10244807.22      3602371.68     10244351.95

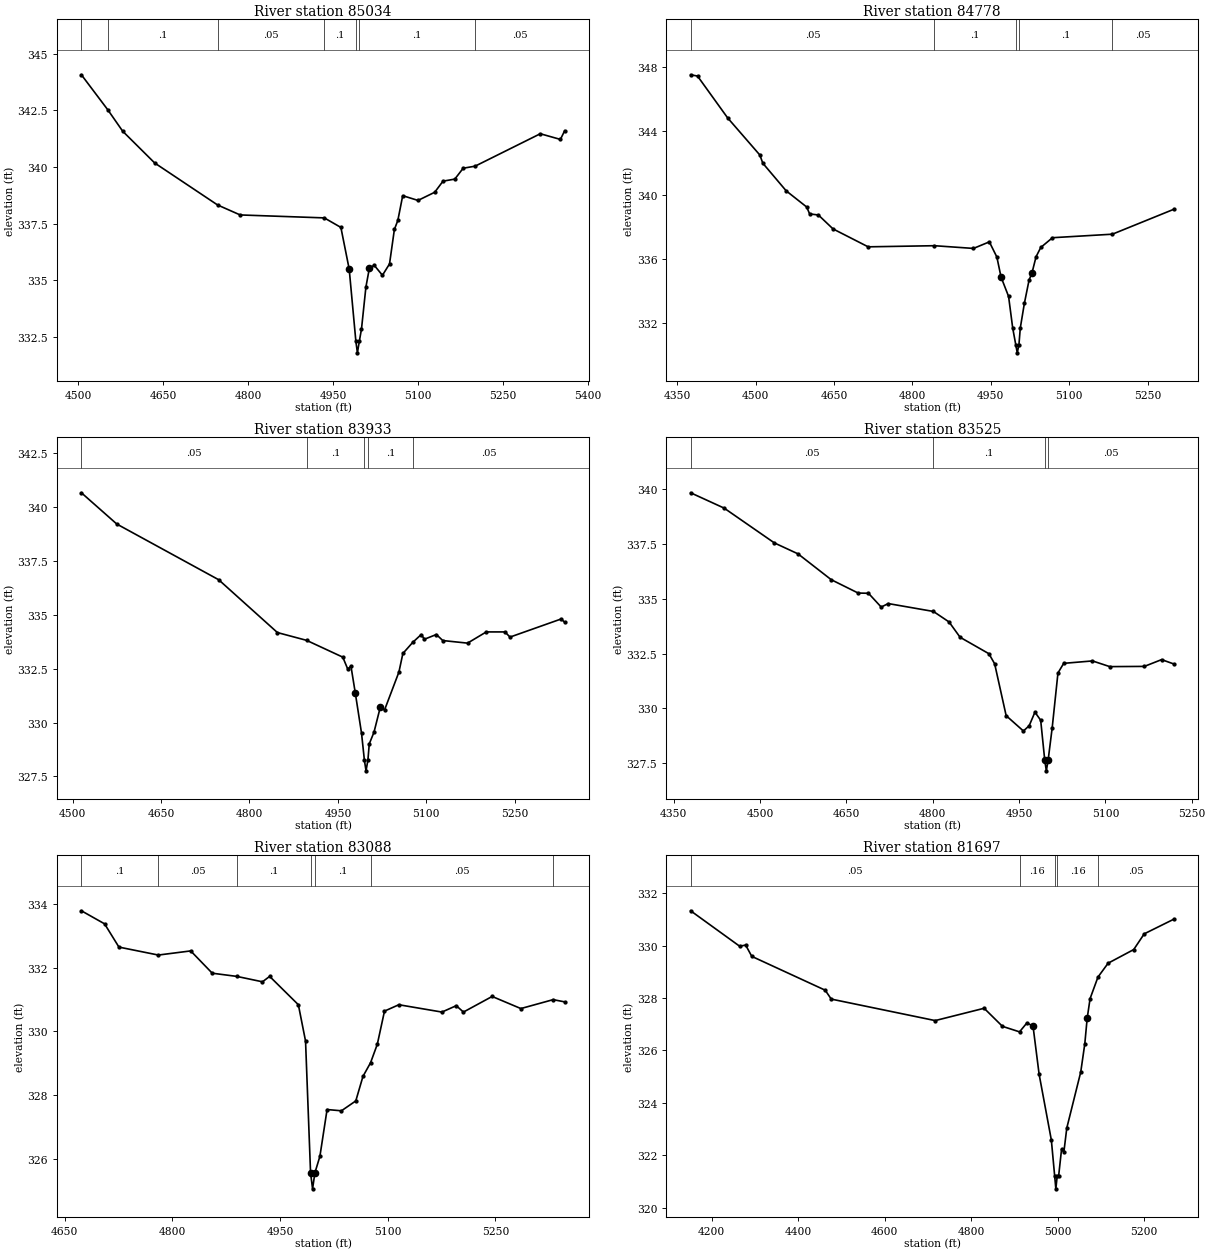
Type RM Length L Ch R = 1 ,85034   ,256,256,256
BEGIN DESCRIPTION:
BOWMAN CREEK 95.0
END DESCRIPTION:
XS GIS Cut Line= 2
      3568173.42     10274031.41       3567481.1     10273532.25
#Sta/Elev= 30
  4505.2  344.07    4552  342.52  4578.2  341.58  4634.7  340.18  4745.7  338.33
  4785.6  337.89  4934.2  337.76  4963.5  337.34  4978.2   335.5    4990  332.31
  4992.7  331.81    4996  332.31  4999.9  332.86  5007.7  334.71  5013.8  335.54
  5022.4  335.67  5036.9  335.23  5049.4  335.73    5058  337.25  5064.1  337.65
  5072.7  338.74  5099.7  338.53  5129.2  338.89  5143.9  339.38  5164.7  339.47
  5179.5  339.95  5200.5  340.04  5315.7  341.47  5351.2  341.22  5358.7   341.6
#Mann= 7 ,-1 , 0
  4505.2     .05       0    4552      .1       0  4745.7     .05       0
  4934.2      .1       0    4990     .07       0    4996      .1       0
  5200.5     .05       0
Bank Sta=4978.2,5013.8
XS Rating Curve= 0 ,0
Exp/Cntr=0.3,0.1

Type RM Length L Ch R = 1 ,84778   ,845,845,845
BEGIN DESCRIPTION:
Mapping XS d358b093
END DESCRIPTION:
XS GIS Cut Line= 2
      3568383.92     10273816.57      3567555.98     10273404.76
#Sta/Elev= 30
  4375.7  347.51  4388.9  347.43  4446.6  344.81  4508.2  342.49  4513.8  341.98
  4558.6  340.25  4597.8  339.24  4603.4  338.81  4620.2  338.74  4648.2  337.87
  4715.4  336.75  4842.3  336.82  4916.9  336.65  4947.3  337.06  4961.7  336.11
  4969.7  334.86  4984.1  333.65    4992  331.67  4997.9  330.62  5000.7  330.12
  5003.9  330.62  5006.5  331.67  5014.3  333.21  5023.3  334.67  5028.9  335.12
  5036.7  336.13  5045.7  336.71  5068.1  337.32  5182.7  337.54  5300.4   339.1
#Mann= 5 ,-1 , 0
  4375.7     .05       0  4842.3      .1       0  4997.9     .07       0
  5003.9      .1       0  5182.7     .05       0
Bank Sta=4969.7,5028.9
XS Rating Curve= 0 ,0
Exp/Cntr=0.3,0.1

Type RM Length L Ch R = 1 ,83933   ,408,408,408
BEGIN DESCRIPTION:
BOWMAN CREEK 94.0
END DESCRIPTION:
XS GIS Cut Line= 3
      3568610.81     10272941.92      3568334.78     10272816.93
      3567846.51     10272985.91
#Sta/Elev= 30
  4514.9  340.65    4575   339.2  4747.7  336.62  4847.4  334.17  4896.8  333.81
  4958.3  333.03  4966.8  332.47  4972.1  332.62  4979.5  331.37  4990.1   329.5
  4994.9  328.26  4997.7  327.76  5000.9  328.26  5003.2  329.01  5011.2  329.55
  5021.8   330.7  5029.1  330.58  5053.5  332.34  5060.2   333.2  5077.1  333.72
  5091.4  334.08  5096.7  333.86    5117  334.08  5127.9   333.8  5169.9  333.68
  5201.7   334.2  5233.4   334.2  5241.9  333.96  5328.7   334.8  5334.6  334.65
#Mann= 5 ,-1 , 0
  4514.9     .05       0  4896.8      .1       0  4994.9     .07       0
  5000.9      .1       0  5077.1     .05       0
Bank Sta=4979.5,5021.8
XS Rating Curve= 0 ,0
Exp/Cntr=0.3,0.1

Type RM Length L Ch R = 1 ,83525   ,437,437,437
BEGIN DESCRIPTION:
BOWMAN CREEK 93.0
END DESCRIPTION:
XS GIS Cut Line= 3
      3568725.37     10272712.75      3568345.19     10272546.09
      3567920.77     10272553.96
#Sta/Elev= 30
  4379.4  339.85  4437.6  339.15  4524.9  337.56    4566  337.06  4623.7  335.88
  4670.5  335.27  4688.4  335.26  4710.5  334.63  4722.7  334.79  4801.2  334.43
  4828.4  333.95  4847.6  333.25  4897.6   332.5  4907.6  332.04  4927.6  329.67
  4957.6  328.97  4967.6  329.21  4977.6  329.83  4987.6  329.46  4994.6  327.65
  4997.4  327.15  5000.6  327.65  5007.6  329.12  5017.6  331.62  5027.6  332.06
  5077.6  332.17  5107.6  331.91  5167.7  331.92  5197.7  332.23    5219  332.03
#Mann= 4 ,-1 , 0
  4379.4     .05       0  4801.2      .1       0  4994.6     .03       0
  5000.6     .05       0
Bank Sta=4994.6,5000.6
XS Rating Curve= 0 ,0
Exp/Cntr=0.3,0.1

Type RM Length L Ch R = 1 ,83088   ,1391,1391,1391
BEGIN DESCRIPTION:
Mapping XS 452c849a
END DESCRIPTION:
XS GIS Cut Line= 2
      3568574.42     10272270.67      3567901.12     10272272.24
#Sta/Elev= 30
  4673.2  333.79  4705.5  333.38  4725.5  332.65  4780.4   332.4  4825.5  332.53
  4855.5  331.83  4889.7  331.73  4925.5  331.56  4935.5  331.73  4975.5  330.84
  4985.5   329.7  4992.5  325.56  4995.3  325.06  4998.5  325.56  5005.5  326.08
  5015.5  327.55  5035.5  327.51  5055.5  327.82  5065.5  328.59  5076.1  329.02
  5085.5   329.6  5095.5  330.64  5115.5  330.84  5175.5  330.61  5195.5  330.81
  5205.5  330.61  5245.5   331.1  5285.5  330.72  5330.5     331  5346.5  330.93
#Mann= 7 ,-1 , 0
  4673.2      .1       0  4780.4     .05       0  4889.7      .1       0
  4992.5     .07       0  4998.5      .1       0  5076.1     .05       0
  5330.5     .12       0
Bank Sta=4992.5,4998.5
XS Rating Curve= 0 ,0
Exp/Cntr=0.3,0.1

Type RM Length L Ch R = 1 ,81697   ,473,473,473
BEGIN DESCRIPTION:
BOWMAN CREEK 92.0
END DESCRIPTION:
XS GIS Cut Line= 3
      3568642.13     10271941.66      3568042.11     10271341.64
      3567792.12     10271241.65
#Sta/Elev= 30
  4151.2  331.33  4264.4  329.98  4278.5  330.02  4292.7  329.59  4462.4   328.3
  4476.5  327.96  4716.9  327.14  4830.1  327.61  4872.5  326.92    4912  326.71
    4929  327.05  4943.2  326.93  4957.3  325.09  4985.6  322.58  4993.2  321.22
    4996  320.72  4999.2  321.22  5002.5  321.22  5009.2  322.23  5014.6  322.13
  5021.3  323.04  5053.6  325.18    5063  326.26  5068.4  327.22  5075.2  327.98
  5093.4   328.8  5116.9  329.33  5176.1  329.85  5200.4  330.45    5269  331.01
#Mann= 5 ,-1 , 0
  4151.2     .05       0    4912     .16       0  4993.2     .07       0
  4999.2     .16       0  5093.4     .05       0
Bank Sta=4943.2,5068.4
XS Rating Curve= 0 ,0
Exp/Cntr=0.3,0.1

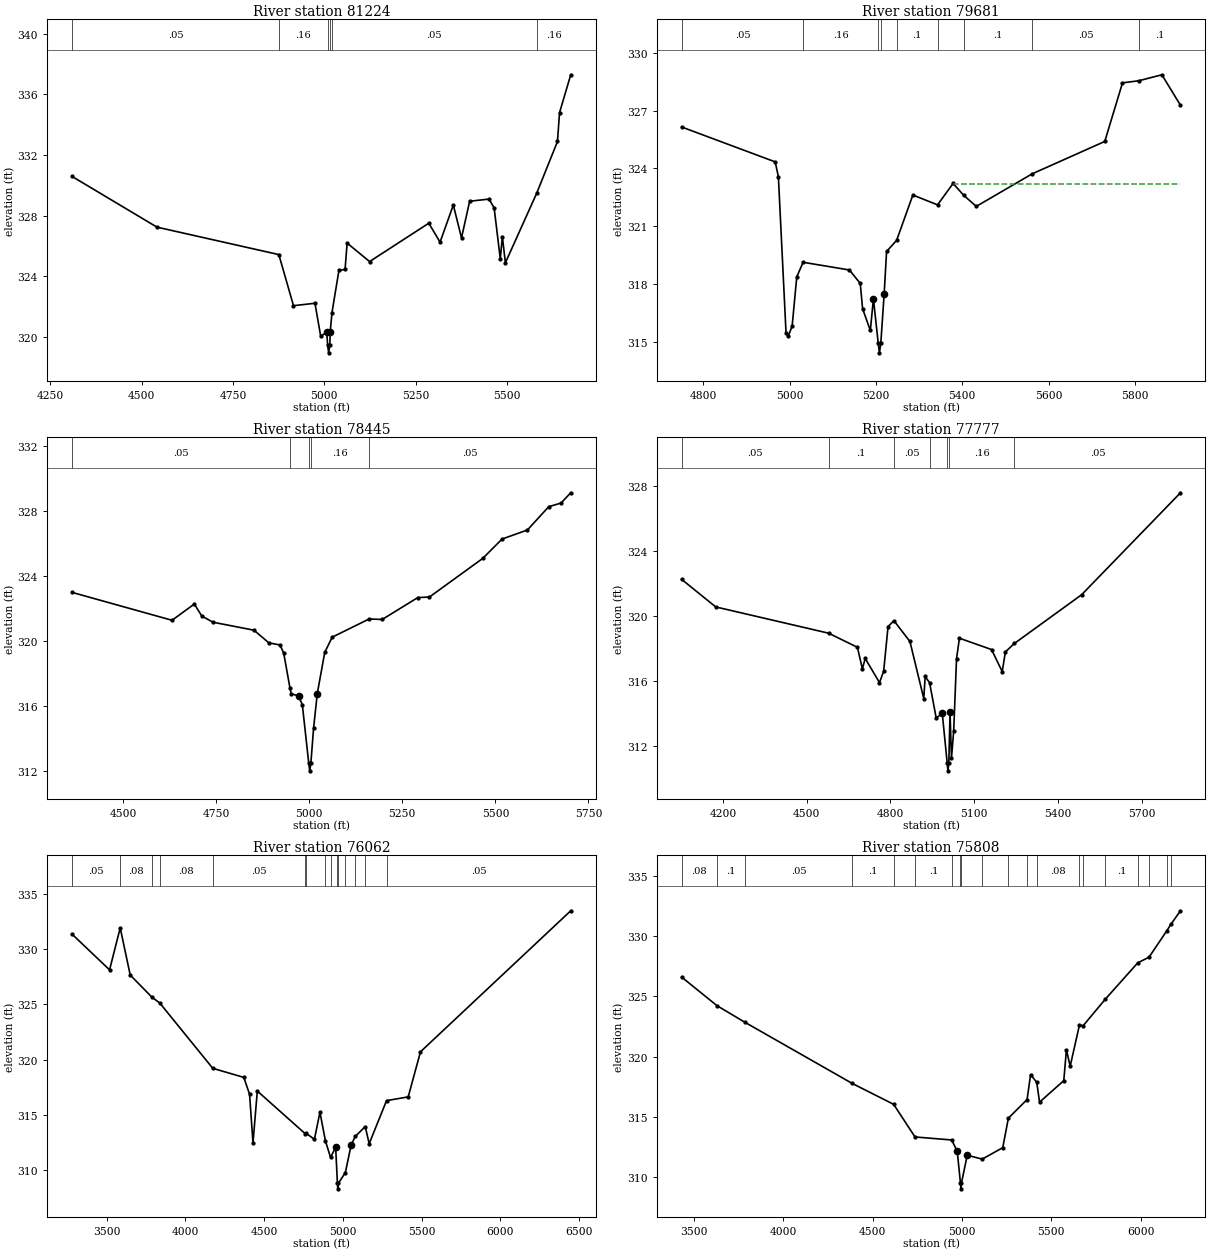
Type RM Length L Ch R = 1 ,81224   ,1543,1543,1543
BEGIN DESCRIPTION:
BOWMAN CREEK 91.0
END DESCRIPTION:
XS GIS Cut Line= 3
      3568942.09     10271491.64      3568342.11     10271141.64
      3568042.12     10270541.67
#Sta/Elev= 30
  4309.1   330.6  4541.9  327.25  4875.5  325.44  4915.6  322.07  4974.4  322.23
  4990.1  320.05  5006.5  320.33  5009.1  319.46  5011.8  318.96  5015.1  319.46
 5016.08  320.33    5021  321.62    5040   324.4  5056.8  324.46  5062.4   326.2
  5123.9  324.98    5286  327.51  5316.8  326.26  5353.1  328.71  5375.5  326.54
  5397.8  328.96  5450.9   329.1  5464.9  328.51  5481.7  325.15  5487.3  326.63
  5495.6   324.9  5581.2  329.48  5638.2   332.9  5643.8   334.8  5674.5   337.3
#Mann= 6 ,-1 , 0
  4309.1     .05       0  4875.5     .16       0  5009.1     .07       0
  5015.1     .16       0    5021     .05       0  5581.2     .16       0
Bank Sta=5006.5,5016.08
XS Rating Curve= 0 ,0
Exp/Cntr=0.3,0.1

Type RM Length L Ch R = 1 ,79681   ,1236,1236,1236
BEGIN DESCRIPTION:
BOWMAN CREEK 90.0
END DESCRIPTION:
XS GIS Cut Line= 2
      3569101.26     10271122.03      3568701.96     10270036.97
#Sta/Elev= 30
  4749.5  326.15  4966.3  324.34  4973.7  323.57  4991.4  315.48  4996.8   315.3
  5005.6  315.82  5016.3  318.37    5031  319.13  5138.4  318.73  5163.5  318.03
  5168.9  316.72  5186.8  315.59    5194  317.23  5205.1  314.93  5207.9  314.43
  5211.1  314.93  5218.8  317.46  5224.5  319.69  5247.8  320.27  5285.4  322.62
  5342.6  322.11  5378.6  323.22  5403.5   322.6  5432.4  322.03    5562  323.72
  5730.2   325.4  5771.3  328.44  5808.9  328.55  5862.6  328.86  5905.7  327.28
#Mann= 9 ,-1 , 0
  4749.5     .05       0    5031     .16       0  5205.1     .03       0
  5211.1     .16       0  5247.8      .1       0  5342.6     .16       0
  5403.5      .1       0    5562     .05       0  5808.9      .1       0
#XS Ineff= 2 , 0
                         5377.95          323.21
Permanent Ineff=
       F       F
Bank Sta=5194,5218.8
XS Rating Curve= 0 ,0
Exp/Cntr=0.3,0.1

Type RM Length L Ch R = 1 ,78445   ,668,668,668
BEGIN DESCRIPTION:
BOWMAN CREEK 89.0
END DESCRIPTION:
XS GIS Cut Line= 3
      3569439.81     10270870.35      3569413.77     10269915.45
      3569248.82     10269568.19
#Sta/Elev= 30
  4362.7  322.99  4631.5  321.27  4691.5  322.27  4711.5  321.53  4741.6  321.15
  4851.6  320.66  4891.6  319.88  4921.6  319.75  4931.6  319.24  4948.3   317.1
  4951.6  316.75  4971.6  316.61  4981.6  316.06  4998.6   312.5  5001.4     312
  5004.6   312.5  5011.7  314.62  5021.7  316.76  5041.7  319.29  5061.7  320.23
  5160.9  321.35  5196.1  321.32  5291.8  322.67  5322.8   322.7  5466.1  325.08
  5517.9  326.27  5586.1  326.83  5643.2  328.26  5676.4  328.49  5702.4  329.12
#Mann= 5 ,-1 , 0
  4362.7     .05       0  4948.3     .16       0  4998.6     .07       0
  5004.6     .16       0  5160.9     .05       0
Bank Sta=4971.6,5021.7
XS Rating Curve= 0 ,0
Exp/Cntr=0.3,0.1

Type RM Length L Ch R = 1 ,77777   ,1715,1715,1715
BEGIN DESCRIPTION:
BOWMAN CREEK 87.0
END DESCRIPTION:
XS GIS Cut Line= 4
      3569943.27       10271070.      3570030.09     10270757.46
      3569818.12     10269761.15      3569466.45     10269490.57
#Sta/Elev= 30
  4052.4  322.25  4174.4  320.55  4578.7  318.93  4681.9  318.06  4699.7  316.73
  4709.9  317.37    4761  315.88  4775.9  316.58  4791.7  319.34  4812.8   319.7
    4870  318.42  4919.6   314.9  4924.7  316.26  4940.5  315.87  4964.1   313.7
  4985.9  313.98  5003.4  310.94  5006.1  310.44  5009.4  310.94  5013.7  314.05
  5018.8  311.21  5026.8  312.91    5037  317.36  5047.3  318.62  5162.4  317.92
  5200.6  316.56    5212  317.78  5244.4   318.3  5484.9   321.3  5839.1  327.59
#Mann= 7 ,-1 , 0
  4052.4     .05       0  4578.7      .1       0  4812.8     .05       0
  4940.5     .16       0  5003.4     .07       0  5009.4     .16       0
  5244.4     .05       0
#XS Ineff= 2 , 0
                         5161.36          317.91
Permanent Ineff=
       F       F
Bank Sta=4985.9,5013.7
XS Rating Curve= 0 ,0
Exp/Cntr=0.3,0.1

Type RM Length L Ch R = 1 ,76062   ,254,254,254
BEGIN DESCRIPTION:
Mapping XS 48139978
END DESCRIPTION:
XS GIS Cut Line= 6
      3571965.81      10270557.8       3571453.7     10270349.48
      3570967.59     10270089.06      3570750.57     10269906.77
      3570021.41     10269273.09      3569491.92      10268656.8
#Sta/Elev= 30
  3280.5  331.38  3519.5  328.13    3587  331.94  3650.6  327.66  3787.9  325.66
  3838.4  325.12  4174.6   319.2  4371.4  318.38  4407.9  316.86  4429.9  312.44
  4457.3  317.14  4761.5  313.27  4765.1  313.33  4819.7  312.76  4854.9  315.22
  4889.5  312.63    4922  311.12  4954.6  312.03  4965.8  308.77  4968.6  308.27
  4971.8  308.77    5016  309.74  5053.3  312.26  5078.9  313.02  5142.5  313.92
  5167.3  312.36  5277.6  316.27  5415.1  316.61    5493   320.7  6446.8  333.49
#Mann= 15 ,-1 , 0
  3280.5     .05       0    3587     .08       0  3787.9     .05       0
  3838.4     .08       0  4174.6     .05       0  4761.5     .16       0
  4765.1     .05       0  4889.5     .16       0    4922     .05       0
  4965.8     .04       0  4971.8     .05       0    5016     .16       0
  5078.9     .05       0  5142.5     .16       0  5277.6     .05       0
Bank Sta=4954.6,5053.3
XS Rating Curve= 0 ,0
Exp/Cntr=0.3,0.1

Type RM Length L Ch R = 1 ,75808   ,604,604,604
BEGIN DESCRIPTION:
BOWMAN CREEK 86.0
END DESCRIPTION:
XS GIS Cut Line= 6
      3572035.27     10270280.03      3571531.82     10270097.74
      3571071.76     10269828.65      3570896.71     10269695.44
      3570321.65     10269205.28      3569892.13     10268591.67
#Sta/Elev= 30
  3430.4  326.61  3627.9  324.24  3784.2  322.86  4383.7  317.79  4617.5  316.04
  4736.9  313.33  4942.3  313.08  4973.5  312.14  4991.3  309.52  4994.1  309.02
  4997.3  309.52  5029.4  311.81  5113.5  311.49  5228.2  312.44  5259.8  314.89
  5364.6  316.44  5384.1  318.51  5418.6  317.87  5434.4  316.22    5570  318.01
  5584.8  320.57  5605.7   319.2  5657.9  322.64  5677.7  322.56    5801  324.75
  5983.9  327.79  6047.6  328.27  6146.9  330.46  6170.9  331.02  6223.4  332.12
#Mann= 20 ,-1 , 0
  3430.4     .08       0  3627.9      .1       0  3784.2     .05       0
  4383.7      .1       0  4617.5     .16       0  4736.9      .1       0
  4942.3     .16       0  4991.3     .07       0  4997.3      .1       0
  5113.5      .1       0  5259.8     .08       0  5364.6      .1       0
  5418.6     .08       0  5657.9      .1       0  5677.7     .08       0
    5801      .1       0  5983.9     .08       0  6047.6      .1       0
  6146.9     .08       0  6170.9      .1       0
Bank Sta=4973.5,5029.4
XS Rating Curve= 0 ,0
Exp/Cntr=0.3,0.1

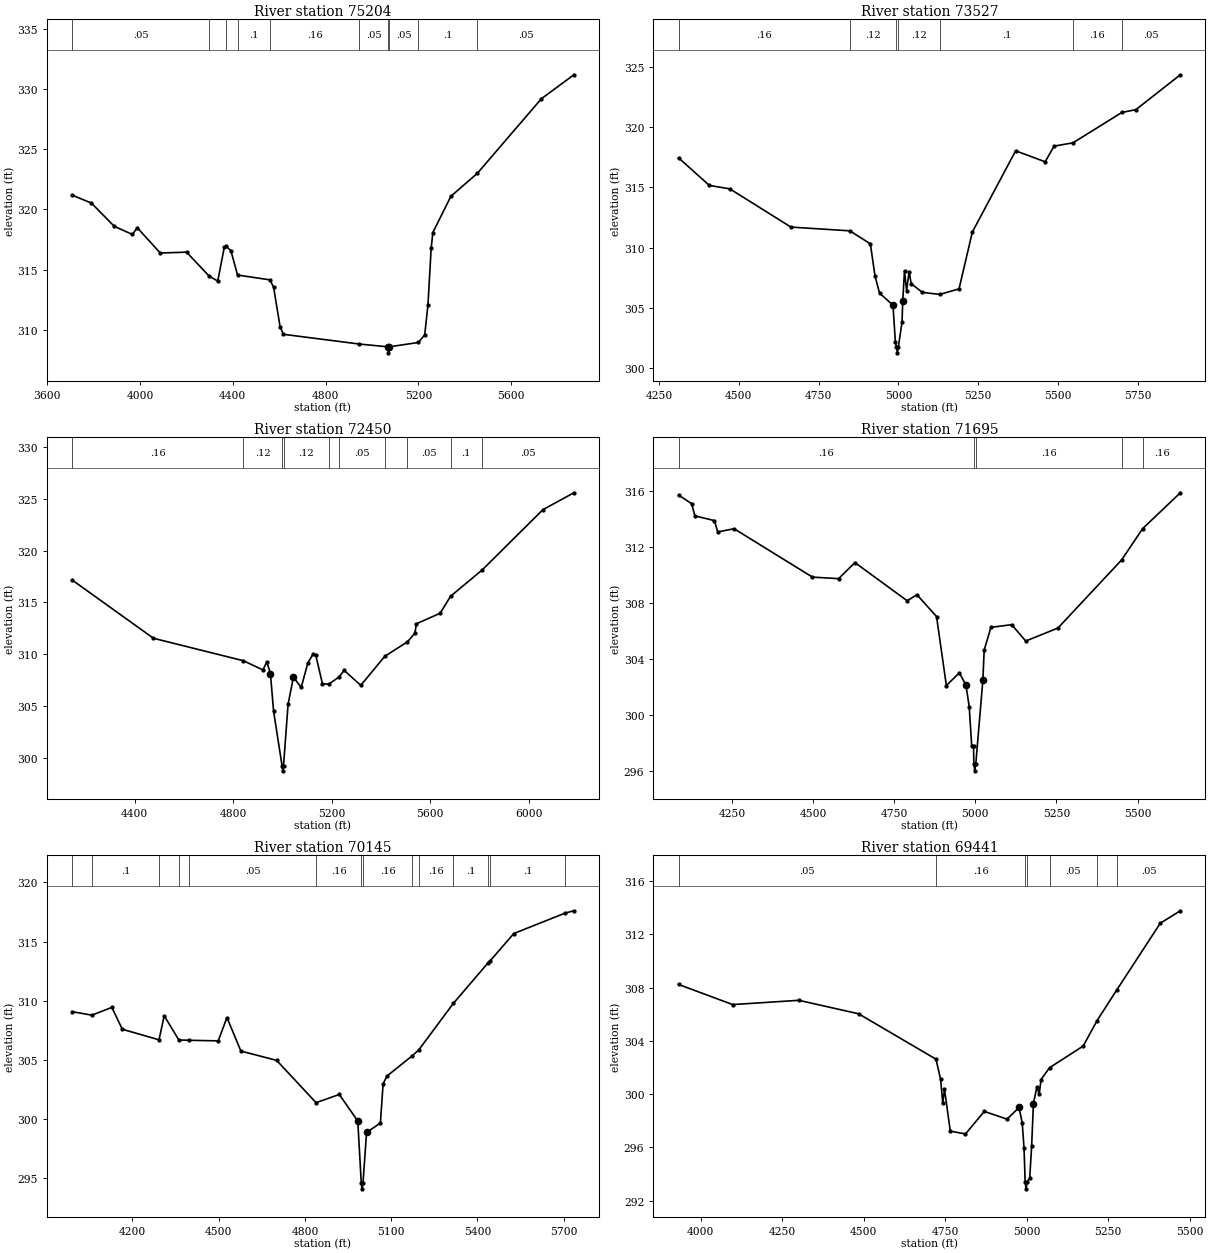
Type RM Length L Ch R = 1 ,75204   ,1677,1677,1677
BEGIN DESCRIPTION:
BOWMAN CREEK 85.0
END DESCRIPTION:
XS GIS Cut Line= 2
      3571948.49     10270002.26      3570472.77     10268422.37
#Sta/Elev= 30
  3707.7  321.19  3790.6  320.53  3889.4   318.6  3967.6  317.92  3988.6  318.48
  4087.7  316.38  4201.1  316.45  4298.9  314.45  4335.4  314.05  4363.7  316.88
  4371.1  316.96  4392.1  316.56  4420.7  314.55  4560.3  314.15  4575.8  313.55
  4604.1  310.24  4618.3  309.63  4945.6  308.82  5068.1  308.59  5070.9  308.09
  5074.1  308.59  5199.5  308.95    5227  309.58  5241.1   312.1  5254.8  316.77
  5262.1  318.08  5339.8  321.09  5453.9     323  5729.2  329.18  5869.6  331.18
#Mann= 10 ,-1 , 0
  3707.7     .05       0  4298.9      .1       0  4371.1     .05       0
  4420.7      .1       0  4560.3     .16       0  4945.6     .05       0
  5068.1    .033       0  5074.1     .05       0  5199.5      .1       0
  5453.9     .05       0
Bank Sta=5068.1,5074.1
XS Rating Curve= 0 ,0
Exp/Cntr=0.3,0.1

Type RM Length L Ch R = 1 ,73527   ,1077,1077,1077
BEGIN DESCRIPTION:
BOWMAN CREEK 82.0
END DESCRIPTION:
XS GIS Cut Line= 2
      3572208.93     10269420.69      3571211.19     10268206.04
#Sta/Elev= 30
  4311.2  317.45  4407.8  315.16  4471.7  314.88  4663.3  311.71  4847.8   311.4
  4912.2  310.32  4926.6  307.66  4940.9  306.24  4982.9  305.24  4990.5  302.18
  4993.9  301.79  4996.7  301.29  4999.9  301.79  5011.3  303.83 5013.53   305.6
  5019.1  308.09  5025.6  306.45  5033.5  308.01    5040  307.02  5075.1   306.3
  5129.3  306.13  5189.9  306.59  5231.6   311.3  5367.2  318.03  5459.7  317.12
  5487.6  318.42  5546.8  318.69    5700  321.21  5743.9  321.44  5883.1  324.33
#Mann= 7 ,-1 , 0
  4311.2     .16       0  4847.8     .12       0  4993.9     .07       0
  4999.9     .12       0  5129.3      .1       0  5546.8     .16       0
    5700     .05       0
Bank Sta=4982.9,5013.53
XS Rating Curve= 0 ,0
Exp/Cntr=0.3,0.1

Type RM Length L Ch R = 1 ,72450   ,755,755,755
BEGIN DESCRIPTION:
BOWMAN CREEK 80.0
END DESCRIPTION:
XS GIS Cut Line= 4
       3572492.1     10269291.69      3572521.41     10268830.38
      3572026.62     10267962.33       3571506.4     10267710.89
#Sta/Elev= 30
  4145.1  317.18  4475.8  311.54  4840.9  309.37  4920.7  308.48  4936.5  309.26
  4951.2  308.13  4963.9  304.52  4998.4  299.22  5001.1  298.72  5004.4  299.22
    5023  305.16  5044.6  307.77  5076.3  306.79  5103.6  309.18  5125.2  310.03
  5135.3  309.93  5162.7  307.13    5188   307.1  5230.3   307.8  5250.5  308.44
  5318.3  306.99  5416.2   309.8  5508.2   311.2  5538.2  312.03  5544.5  312.94
  5640.9  313.96  5683.1   315.6  5810.5  318.12  6058.8  323.98  6184.3  325.61
#Mann= 10 ,-1 , 0
  4145.1     .16       0  4840.9     .12       0  4998.4     .07       0
  5004.4     .12       0    5188     .16       0  5230.3     .05       0
  5416.2     .16       0  5508.2     .05       0  5683.1      .1       0
  5810.5     .05       0
Bank Sta=4951.2,5044.6
XS Rating Curve= 0 ,0
Exp/Cntr=0.3,0.1

Type RM Length L Ch R = 1 ,71695   ,1550,1550,1550
BEGIN DESCRIPTION:
BOWMAN CREEK 78.0
END DESCRIPTION:
XS GIS Cut Line= 3
      3572842.11     10268991.69      3572742.11     10268091.64
       3572342.1     10267591.64
#Sta/Elev= 30
  4085.7   315.7    4126  315.08  4136.1  314.21  4196.4  313.87  4206.5  313.06
  4256.8  313.29  4498.3  309.83  4578.8  309.72  4629.1  310.87  4790.1  308.14
  4820.2  308.57  4880.6  307.01  4910.8  302.08    4951  302.99  4971.2   302.1
  4981.2  300.57  4988.8  297.79  4994.5  297.79  4995.5  296.48  4998.2  295.98
  5001.5  296.48 5023.31  302.48  5027.3  304.61  5048.1  306.24  5112.1  306.43
  5155.4  305.26  5254.6  306.19  5450.8  311.06  5515.6   313.3  5631.6  315.86
#Mann= 5 ,-1 , 0
  4085.7     .16       0  4995.5     .07       0  5001.5     .16       0
  5450.8      .1       0  5515.6     .16       0
Bank Sta=4971.2,5023.31
XS Rating Curve= 0 ,0
Exp/Cntr=0.3,0.1

Type RM Length L Ch R = 1 ,70145   ,704,704,704
BEGIN DESCRIPTION:
BOWMAN CREEK 77.0
END DESCRIPTION:
XS GIS Cut Line= 3
      3573649.28     10268006.55      3572816.55     10266694.96
      3572626.31     10266669.02
#Sta/Elev= 30
    3990  309.09  4059.1  308.79  4128.3  309.45  4164.8   307.6  4292.4  306.71
  4310.5  308.74  4361.3   306.7  4396.8  306.67  4498.5  306.62  4528.8  308.59
  4577.3  305.76  4701.8  304.97  4838.7   301.4  4919.7  302.09  4983.9  299.85
  4996.1  294.62  4998.9  294.12  5002.1  294.62  5014.4  298.88  5062.6  299.68
    5072  302.99  5085.6  303.65  5172.3  305.34  5195.9  305.85  5316.1  309.78
  5435.4  313.16  5443.2  313.35  5526.8  315.69  5705.9  317.42  5735.6  317.61
#Mann= 14 ,-1 , 0
    3990     .05       0  4059.1      .1       0  4292.4     .05       0
  4361.3      .1       0  4396.8     .05       0  4838.7     .16       0
  4996.1     .07       0  5002.1     .16       0  5172.3      .1       0
  5195.9     .16       0  5316.1      .1       0  5435.4     .16       0
  5443.2      .1       0  5705.9     .16       0
Bank Sta=4983.9,5014.4
XS Rating Curve= 0 ,0
Exp/Cntr=0.3,0.1

Type RM Length L Ch R = 1 ,69441   ,715,715,715
BEGIN DESCRIPTION:
BOWMAN CREEK 75.0
END DESCRIPTION:
XS GIS Cut Line= 2
      3574055.16     10267876.62      3573432.87     10266469.27
#Sta/Elev= 30
  3932.1  308.23  4098.2  306.72    4301  307.04  4484.2  306.03  4721.7  302.62
  4735.7  301.11  4742.3  299.33  4747.7  300.36  4765.5  297.22  4812.1  297.01
  4869.7   298.7  4939.6  298.12  4976.3     299  4986.2  297.81  4991.6  295.94
  4995.1  293.39  4997.9  292.89  5001.1  293.39  5009.1  293.73  5014.9  296.07
  5020.4  299.29  5030.9  300.53  5038.2  299.99  5043.7  301.09  5069.8  301.98
  5173.1  303.61  5215.6  305.52  5276.6  307.84  5409.6  312.83  5470.9  313.76
#Mann= 7 ,-1 , 0
  3932.1     .05       0  4721.7     .16       0  4995.1     .07       0
  5001.1     .16       0  5069.8     .05       0  5215.6      .1       0
  5276.6     .05       0
Bank Sta=4976.3,5020.4
XS Rating Curve= 0 ,0
Exp/Cntr=0.3,0.1

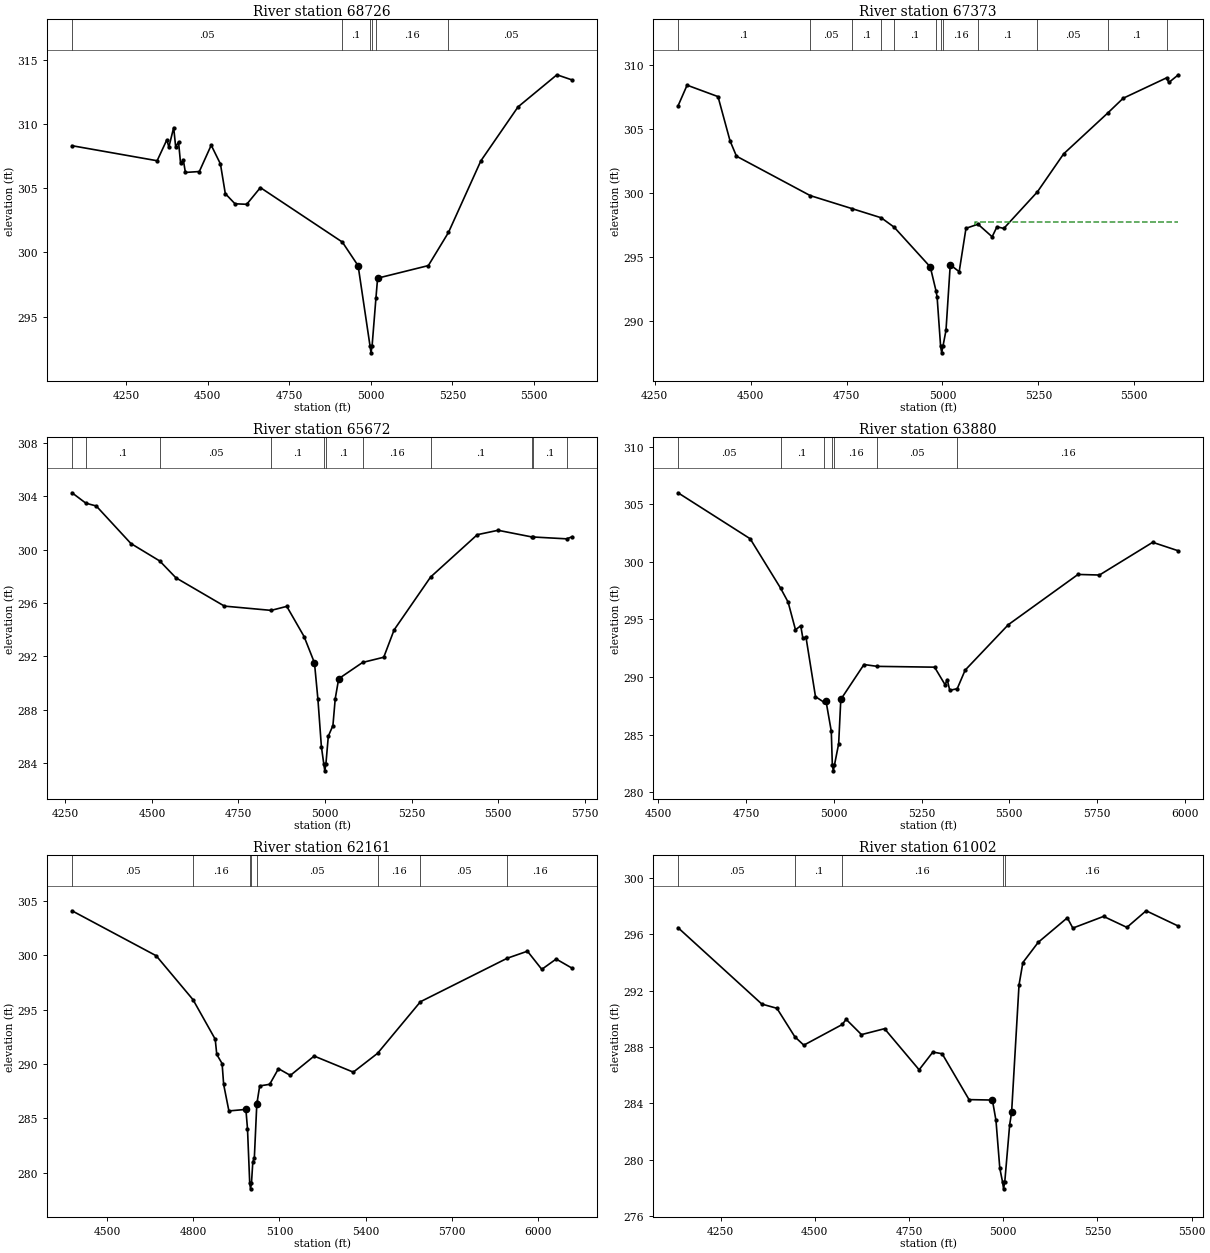
Type RM Length L Ch R = 1 ,68726   ,1353,1353,1353
BEGIN DESCRIPTION:
BOWMAN CREEK 74.0
END DESCRIPTION:
XS GIS Cut Line= 3
      3574474.51     10267762.65      3574144.67     10267285.24
      3573893.15     10266365.89
#Sta/Elev= 30
  4084.3  308.31  4345.2  307.14    4375  308.77  4381.1   308.2  4395.9  309.72
    4402  308.22  4410.8   308.6  4416.9  306.97  4425.7  307.16  4431.8  306.23
  4474.5   306.3  4510.9  308.35  4539.2  306.89  4554.1  304.58  4583.8  303.79
  4619.7  303.75  4661.6  305.05  4912.8  300.81  4961.1  298.97  4997.8  292.69
  5000.6  292.19  5003.8  292.69  5015.8  296.48  5020.8     298  5176.3  298.98
    5238  301.56  5337.2  307.13  5451.1  311.33  5570.3  313.83  5617.7  313.42
#Mann= 6 ,-1 , 0
  4084.3     .05       0  4912.8      .1       0  4997.8     .07       0
  5003.8      .1       0  5015.8     .16       0    5238     .05       0
Bank Sta=4961.1,5020.8
XS Rating Curve= 0 ,0
Exp/Cntr=0.3,0.1

Type RM Length L Ch R = 1 ,67373   ,1701,1701,1701
BEGIN DESCRIPTION:
BOWMAN CREEK 71.0
END DESCRIPTION:
XS GIS Cut Line= 4
      3575021.41     10267293.95      3574970.69     10267072.62
       3574622.1     10266286.98      3574415.45      10266218.1
#Sta/Elev= 30
  4310.6  306.77  4334.3  308.39  4414.9   307.5  4446.3  304.05    4463  302.86
  4655.2  299.79  4764.6  298.77  4840.4  298.06    4874  297.33  4968.3  294.23
  4983.4  292.34  4986.1  291.87  4995.2  288.04    4998  287.54  5001.2  288.04
  5009.2  289.29  5020.3   294.4  5043.6  293.86  5061.3  297.24  5092.7  297.56
  5129.5  296.58  5142.1  297.36  5159.9  297.23  5247.5  300.08  5315.9  303.04
  5431.2  306.23    5471  307.37  5584.1  308.96  5590.1   308.6    5615   309.2
#Mann= 12 ,-1 , 0
  4310.6      .1       0  4655.2     .05       0  4764.6      .1       0
  4840.4     .05       0    4874      .1       0  4983.4     .16       0
  4995.2     .07       0  5001.2     .16       0  5092.7      .1       0
  5247.5     .05       0  5431.2      .1       0  5584.1     .05       0
#XS Ineff= 2 , 0
                         5085.45          297.73
Permanent Ineff=
       F       F
Bank Sta=4968.3,5020.3
XS Rating Curve= 0 ,0
Exp/Cntr=0.3,0.1

Type RM Length L Ch R = 1 ,65672   ,1792,1792,1792
BEGIN DESCRIPTION:
BOWMAN CREEK 69.0
END DESCRIPTION:
XS GIS Cut Line= 2
      3575442.11     10266941.66      3575490.16     10265497.05
#Sta/Elev= 30
  4269.1  304.25  4309.2  303.47  4339.2  303.26  4439.2  300.45  4522.6  299.14
  4569.3  297.88  4709.4  295.76  4844.3  295.44  4889.5  295.74  4939.5  293.48
  4969.5  291.51  4979.5  288.77  4989.5  285.23  4996.5  283.92  4999.3  283.42
  5002.5  283.92  5009.5  286.02  5022.8  286.81  5029.5  288.83  5039.5  290.32
  5108.6  291.54  5169.6  291.93  5199.6  293.98    5305  297.94  5439.8  301.11
  5499.8  301.44  5597.7  300.94  5599.4  300.94  5697.6   300.8  5714.5  300.96
#Mann= 11 ,-1 , 0
  4269.1     .05       0  4309.2      .1       0  4522.6     .05       0
  4844.3      .1       0  4996.5     .07       0  5002.5      .1       0
  5108.6     .16       0    5305      .1       0  5597.7     .16       0
  5599.4      .1       0  5697.6     .16       0
Bank Sta=4969.5,5039.5
XS Rating Curve= 0 ,0
Exp/Cntr=0.3,0.1

Type RM Length L Ch R = 1 ,63880   ,1719,1719,1719
BEGIN DESCRIPTION:
BOWMAN CREEK 68.0
END DESCRIPTION:
XS GIS Cut Line= 3
      3576905.13     10266182.84      3576063.07     10265618.58
      3575667.02     10265506.65
#Sta/Elev= 30
  4556.3     306  4761.8  302.01  4848.3  297.73  4869.9  296.51  4890.9  294.11
  4905.9  294.45  4911.9  293.38  4920.9  293.45  4947.9   288.3  4971.9  287.82
  4977.9  287.91  4992.9   285.3  4995.9  282.36  4998.7  281.86  5001.9  282.36
  5013.9  284.21    5020  288.06    5086  291.09  5123.8  290.93  5287.1  290.86
  5317.1  289.33  5323.1  289.78  5330.3  288.85  5351.6  288.99  5374.1   290.6
  5497.2  294.55  5695.6  298.91  5756.8  298.86  5908.3   301.7  5981.5  300.96
#Mann= 7 ,-1 , 0
  4556.3     .05       0  4848.3      .1       0  4971.9     .16       0
  4995.9     .07       0  5001.9     .16       0  5123.8     .05       0
  5351.6     .16       0
Bank Sta=4977.9,5020
XS Rating Curve= 0 ,0
Exp/Cntr=0.3,0.1

Type RM Length L Ch R = 1 ,62161   ,1159,1159,1159
BEGIN DESCRIPTION:
BOWMAN CREEK 66.0
END DESCRIPTION:
XS GIS Cut Line= 4
      3577373.83     10265705.36      3577295.71     10265410.24
      3576445.02     10265063.02      3575925.61     10265045.71
#Sta/Elev= 30
  4376.9   304.1  4670.4  299.96  4798.6  295.92    4876  292.28  4881.4  290.88
    4900  290.04  4905.4  288.12  4923.7  285.68  4982.9  285.82  4988.5  284.04
  4996.3  279.01  4999.1  278.51  5002.3  279.01    5007  280.97  5012.4  281.38
  5020.9  286.29  5021.9  286.46    5031  287.98  5065.8  288.13  5096.5  289.57
  5137.9  288.95  5220.8  290.73  5357.2  289.25  5441.7  290.98  5591.2  295.73
  5893.4  299.73  5964.1  300.38  6014.1  298.71  6064.2  299.66  6120.7   298.8
#Mann= 8 ,-1 , 0
  4376.9     .05       0  4798.6     .16       0  4996.3     .07       0
  5002.3     .16       0  5021.9     .05       0  5441.7     .16       0
  5591.2     .05       0  5893.4     .16       0
Bank Sta=4982.9,5020.9
XS Rating Curve= 0 ,0
Exp/Cntr=0.3,0.1

Type RM Length L Ch R = 1 ,61002   ,2178,2178,2178
BEGIN DESCRIPTION:
BOWMAN CREEK 64.0
END DESCRIPTION:
XS GIS Cut Line= 2
      3577599.53     10264889.41      3576297.42     10264628.99
#Sta/Elev= 30
    4137  296.48  4359.5  291.05  4399.5  290.75  4447.2  288.72  4470.9  288.13
    4573   289.6  4583.1  289.97  4623.9  288.88  4685.1   289.3  4776.9  286.38
  4813.3  287.64    4838  287.52  4909.4  284.26  4971.3  284.23  4980.8  282.79
    4991  279.38  4998.2  278.42    5001  277.92  5004.2  278.42  5017.2  282.48
  5022.3  283.35    5042  292.41  5052.2     294    5093  295.44  5170.2  297.18
  5184.8  296.45  5266.4  297.28  5328.3   296.5  5379.3  297.68  5464.9  296.59
#Mann= 5 ,-1 , 0
    4137     .05       0  4447.2      .1       0    4573     .16       0
  4998.2     .07       0  5004.2     .16       0
Bank Sta=4971.3,5022.3
XS Rating Curve= 0 ,0
Exp/Cntr=0.3,0.1

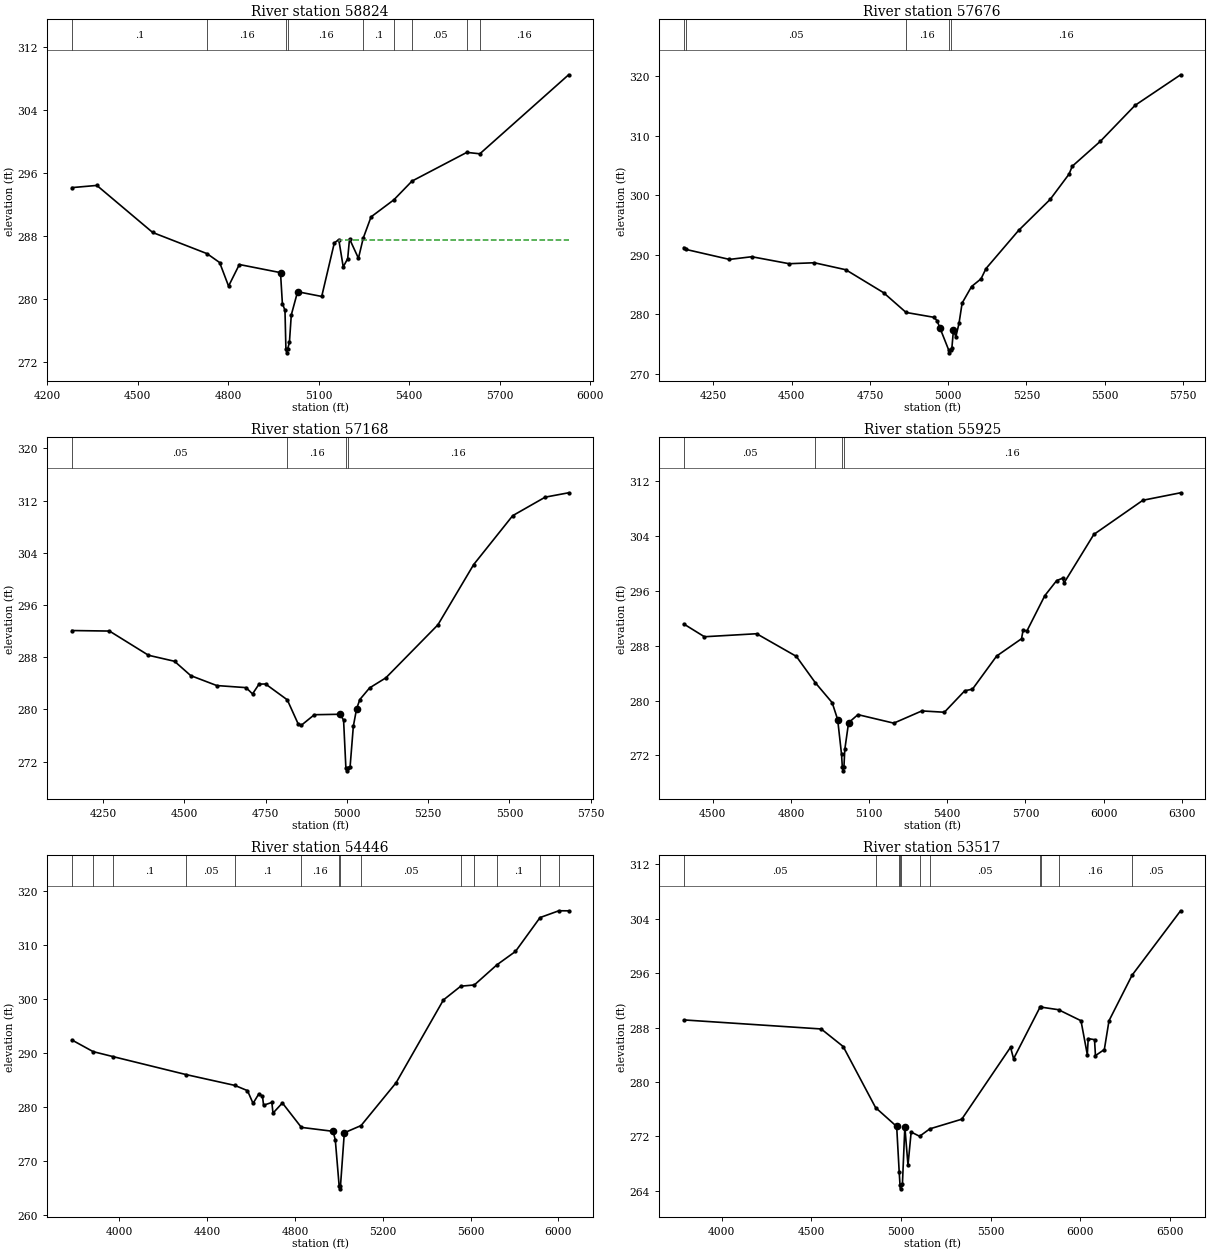
Type RM Length L Ch R = 1 ,58824   ,1148,1148,1148
BEGIN DESCRIPTION:
BOWMAN CREEK 62.0
END DESCRIPTION:
XS GIS Cut Line= 3
      3577807.85     10264290.43      3577087.38     10263274.83
      3577304.27     10262936.47
#Sta/Elev= 30
  4281.3  294.12  4364.3   294.4  4549.5  288.43  4729.5  285.75  4771.4  284.62
    4801  281.63  4836.7  284.37  4973.2  283.34  4979.4  279.42    4988  278.57
  4991.1  273.67  4993.9  273.17  4997.1  273.67  5002.8  274.52  5008.9  277.97
  5029.8  280.92  5109.8  280.32  5151.6  287.11  5166.4  287.53  5181.1  284.07
  5195.9  285.11    5202  287.62  5231.6  285.16  5247.5  287.72  5273.4  290.41
  5348.9  292.57  5409.2  294.95  5590.9  298.59  5634.1  298.41  5928.4  308.43
#Mann= 9 ,-1 , 0
  4281.3      .1       0  4729.5     .16       0  4991.1     .07       0
  4997.1     .16       0  5247.5      .1       0  5348.9     .16       0
  5409.2     .05       0  5590.9      .1       0  5634.1     .16       0
#XS Ineff= 2 , 0
                          5167.5          287.52
Permanent Ineff=
       F       F
Bank Sta=4973.2,5029.8
XS Rating Curve= 0 ,0
Exp/Cntr=0.3,0.1

Type RM Length L Ch R = 1 ,57676   ,508,508,508
BEGIN DESCRIPTION:
BOWMAN CREEK 61.0
END DESCRIPTION:
XS GIS Cut Line= 2
      3578076.96     10264116.82       3577929.4     10262536.99
#Sta/Elev= 30
  4155.5  291.22  4161.2  290.92  4301.3  289.23  4372.8  289.68  4492.1  288.51
  4572.5  288.67  4672.9   287.5  4793.4  283.66  4865.5  280.34  4954.1  279.53
  4964.2  278.99  4974.2  277.67  5001.4  274.07  5004.1  273.57  5007.4  274.07
  5011.8  274.39  5016.8   277.4  5024.4  276.25  5034.5  278.49  5044.5  281.91
  5074.7  284.69  5104.8  285.97  5120.8   287.7  5224.7  294.08  5325.7  299.29
    5386  303.53  5396.1  304.84  5486.4  309.05  5596.9  315.06  5742.2  320.18
#Mann= 5 ,-1 , 0
  4155.5     .16       0  4161.2     .05       0  4865.5     .16       0
  5001.4     .07       0  5007.4     .16       0
Bank Sta=4974.2,5016.8
XS Rating Curve= 0 ,0
Exp/Cntr=0.3,0.1

Type RM Length L Ch R = 1 ,57168   ,1243,1243,1243
BEGIN DESCRIPTION:
BOWMAN CREEK 59.0
END DESCRIPTION:
XS GIS Cut Line= 2
      3578458.91      10264047.4      3578502.31     10262519.61
#Sta/Elev= 30
  4153.7   292.1  4269.5  292.02  4389.6  288.31  4469.6  287.39  4519.6  285.19
  4599.6  283.67  4689.7  283.35  4709.7  282.39  4729.7  283.89  4749.7  283.91
  4816.6  281.48  4849.7  277.83  4859.7  277.58  4899.8   279.2  4979.8  279.27
  4989.8  278.34  4996.8   271.1  4999.5   270.6  5002.8   271.1  5009.8  271.22
  5019.8  277.44  5029.8   280.1  5039.8  281.53  5069.8  283.31  5119.8  284.85
  5279.9  292.97    5390  302.21    5510   309.7    5610  312.54  5682.1  313.21
#Mann= 4 ,-1 , 0
  4153.7     .05       0  4816.6     .16       0  4996.8     .07       0
  5002.8     .16       0
Bank Sta=4979.8,5029.8
XS Rating Curve= 0 ,0
Exp/Cntr=0.3,0.1

Type RM Length L Ch R = 1 ,55925   ,1479,1479,1479
BEGIN DESCRIPTION:
BOWMAN CREEK 57.0
END DESCRIPTION:
XS GIS Cut Line= 3
       3579842.1     10263741.64      3579101.27     10262658.51
      3578563.08     10262406.77
#Sta/Elev= 30
  4388.8  291.15    4468  289.29  4668.4  289.73  4820.8  286.43  4893.6  282.59
  4958.2  279.69  4979.3  277.23  4994.2  272.15  4997.3  270.25    5000  269.75
  5003.3  270.25  5006.7  272.87  5021.2  276.76  5057.1  277.94  5194.6   276.7
  5302.3  278.48  5388.9  278.29  5467.1  281.42  5496.6  281.65  5589.4  286.48
  5684.9     289    5691  290.27  5705.5  290.13  5774.1  295.27  5819.8  297.48
  5842.6  297.82  5848.1  297.14  5962.3   304.2  6150.6  309.18  6295.2  310.27
#Mann= 4 ,-1 , 0
  4388.8     .05       0  4893.6     .16       0  4997.3     .07       0
  5003.3     .16       0
Bank Sta=4979.3,5021.2
XS Rating Curve= 0 ,0
Exp/Cntr=0.3,0.1

Type RM Length L Ch R = 1 ,54446   ,929,929,929
BEGIN DESCRIPTION:
BOWMAN CREEK 55.0
END DESCRIPTION:
XS GIS Cut Line= 2
      3580442.11     10263641.65      3579934.85     10261435.62
#Sta/Elev= 30
  3783.1  292.44  3880.4  290.27  3972.8  289.33  4303.6  286.02  4526.1  284.01
  4583.5  283.04  4608.9  280.68  4634.8  282.42  4651.7  282.05  4656.8  280.34
  4694.6  280.85  4699.7  278.87  4742.5  280.76    4829  276.23  4973.4   275.5
  4983.6  273.92  5001.2  265.34  5003.9  264.84  5007.2  265.34  5024.7  275.23
  5101.1  276.57  5260.7  284.51  5476.2  299.85  5555.2   302.4  5617.1  302.63
  5720.2  306.37  5804.5  308.84  5916.5  315.12  6002.1  316.38  6046.7  316.37
#Mann= 14 ,-1 , 0
  3783.1      .1       0  3880.4     .05       0  3972.8      .1       0
  4303.6     .05       0  4526.1      .1       0    4829     .16       0
  5001.2     .07       0  5007.2     .16       0  5101.1     .05       0
  5555.2      .1       0  5617.1     .05       0  5720.2      .1       0
  5916.5     .16       0  6002.1      .1       0
Bank Sta=4973.4,5024.7
XS Rating Curve= 0 ,0
Exp/Cntr=0.3,0.1

Type RM Length L Ch R = 1 ,53517   ,1772,1772,1772
BEGIN DESCRIPTION:
BOWMAN CREEK 53.0
END DESCRIPTION:
XS GIS Cut Line= 3
      3580846.07       10263405.      3581096.08     10262683.69
      3580585.64      10260740.1
#Sta/Elev= 30
  3787.5  289.14  4554.5  287.81  4677.1  285.23  4858.2  276.24  4975.8  273.47
  4989.9  266.77  4994.6   264.8  4997.4   264.3  5000.6   264.8  5007.9  265.01
  5021.4   273.4    5039  267.78  5056.6  272.65  5103.7  272.03  5160.8  273.12
  5339.1  274.54  5611.3  285.12  5628.3  283.43  5776.6  291.05  5779.8  291.03
  5879.2  290.64  6004.6  289.02  6039.8  284.04  6044.9  286.39  6080.1  286.24
  6085.3  283.89  6134.9  284.79  6160.9  289.02  6289.8  295.72  6560.4  305.19
#Mann= 11 ,-1 , 0
  3787.5     .05       0  4858.2     .16       0  4989.9     .12       0
  4994.6     .07       0  5000.6     .12       0  5103.7     .16       0
  5160.8     .05       0  5776.6     .16       0  5779.8     .05       0
  5879.2     .16       0  6289.8     .05       0
Bank Sta=4975.8,5021.4
XS Rating Curve= 0 ,0
Exp/Cntr=0.3,0.1