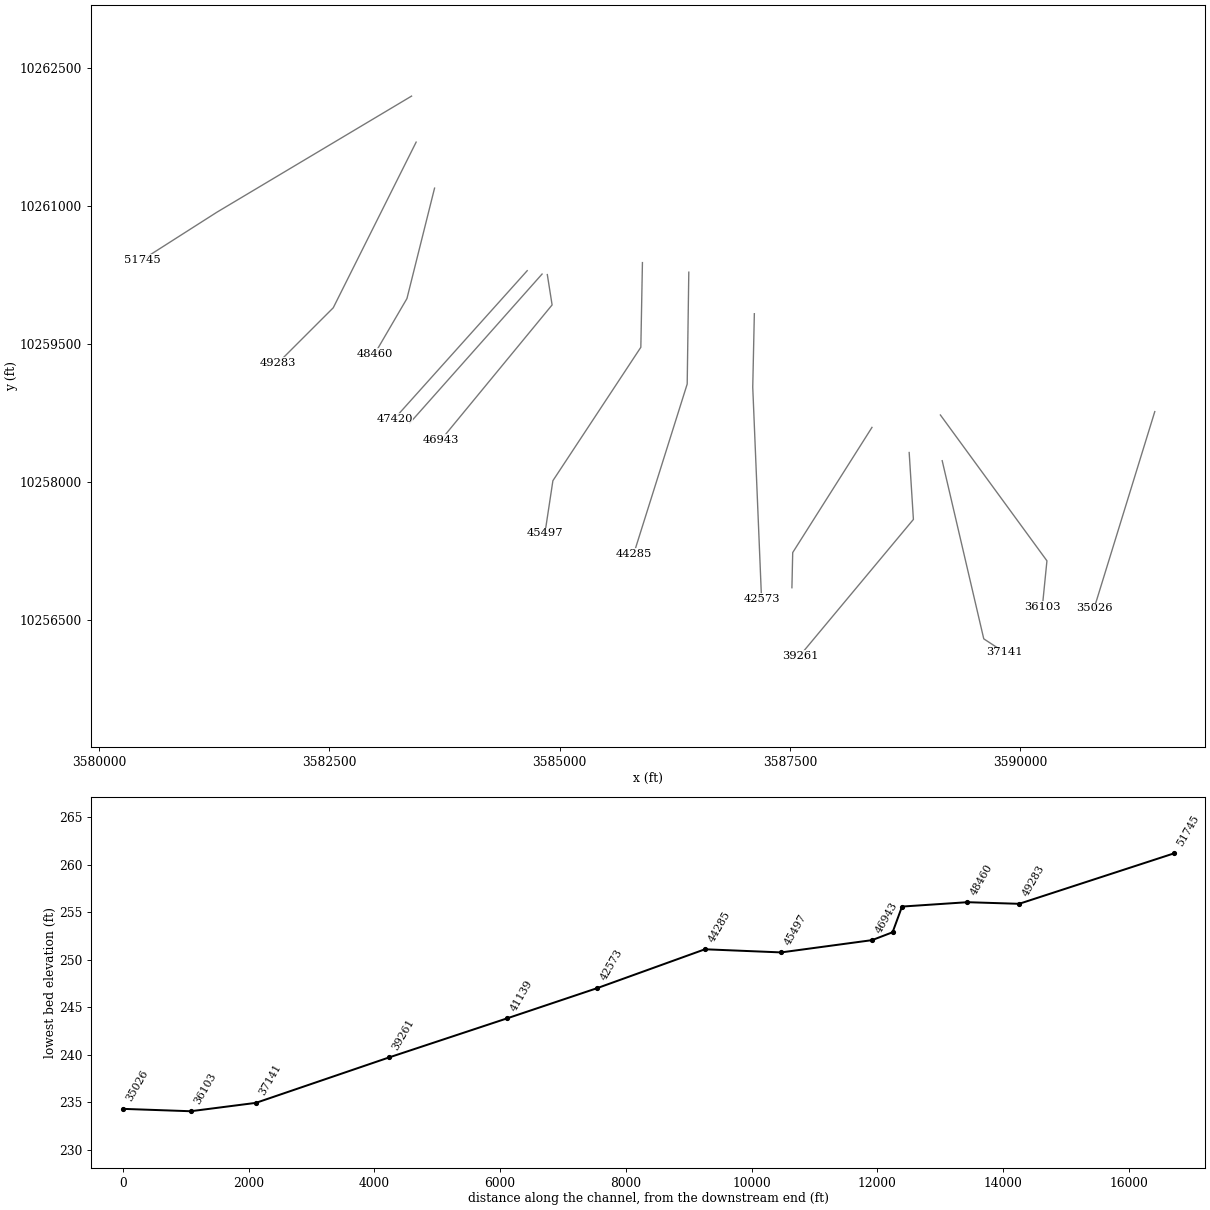
HEC-RAS study BOWMAN CREEK.prj: BOWMAN CREEK Base Level Engineering

--- BOWMAN CREEK.g01 (geometry) --- (continued)

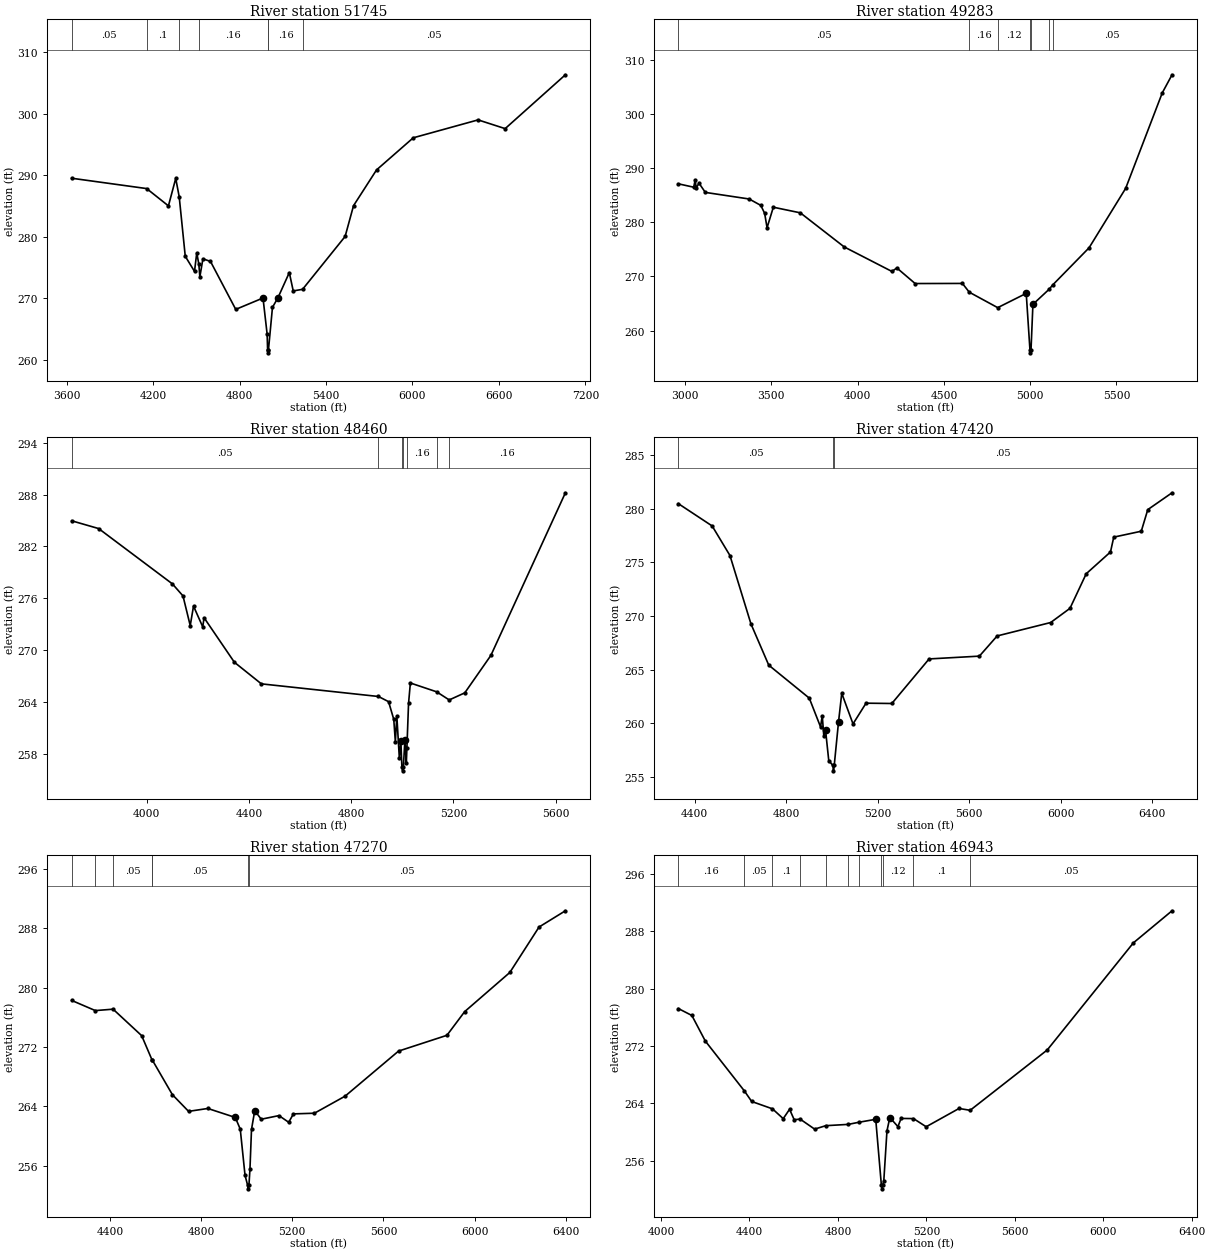
Type RM Length L Ch R = 1 ,51745   ,2462,2462,2462
BEGIN DESCRIPTION:
BOWMAN CREEK 50.0
END DESCRIPTION:
XS GIS Cut Line= 3
      3583392.14     10262191.66      3581280.09     10260931.08
      3580465.61      10260411.2
#Sta/Elev= 30
  3635.1  289.54  4155.4  287.86  4306.5  285.05  4357.2  289.51  4381.3  286.53
  4423.3  276.86  4487.5   274.4  4503.1  277.42  4517.7  275.54  4524.5  273.51
  4545.9  276.45  4598.4  276.02  4773.6  268.23  4962.8  270.08  4991.5  264.19
  4994.7  261.67  4997.4  261.17  5000.7  261.67  5028.5  268.57  5065.5  270.07
  5145.3  274.21  5172.5  271.23  5237.3  271.49  5532.6  280.08  5590.9  285.08
  5750.5  290.89  6005.4  296.11  6455.2  299.02    6643   297.6    7061  306.35
#Mann= 7 ,-1 , 0
  3635.1     .05       0  4155.4      .1       0  4381.3     .05       0
  4517.7     .16       0  4994.7     .07       0  5000.7     .16       0
  5237.3     .05       0
#XS Ineff= 2 , 0
                         5145.45          274.14
Permanent Ineff=
       F       F
Bank Sta=4962.8,5065.5
XS Rating Curve= 0 ,0
Exp/Cntr=0.3,0.1

Type RM Length L Ch R = 1 ,49283   ,823,823,823
BEGIN DESCRIPTION:
BOWMAN CREEK 48.0
END DESCRIPTION:
XS GIS Cut Line= 3
      3583442.09     10261691.61      3582542.11     10259891.64
      3581942.14     10259291.68
#Sta/Elev= 30
  2961.1  287.14  3050.5  286.51  3058.9  287.89  3064.5  286.36  3081.2  287.25
  3117.6  285.55  3371.9  284.33    3439  283.15  3461.4  281.68  3475.4  279.01
  3511.7  282.81  3668.2  281.77  3922.6  275.46  4199.3  270.92  4227.2  271.58
  4333.4  268.69  4607.4  268.71    4647  267.09  4811.8  264.23  4977.1  266.87
  4998.8  256.37  5001.6  255.87  5004.8  256.37  5015.9  264.84  5109.8  267.63
  5130.2  268.42  5341.2   275.3  5553.3   286.3  5765.5  303.97    5822  307.31
#Mann= 7 ,-1 , 0
  2961.1     .05       0    4647     .16       0  4811.8     .12       0
  4998.8     .07       0  5004.8     .12       0  5109.8     .16       0
  5130.2     .05       0
Bank Sta=4977.1,5015.9
XS Rating Curve= 0 ,0
Exp/Cntr=0.3,0.1

Type RM Length L Ch R = 1 ,48460   ,1040,1040,1040
BEGIN DESCRIPTION:
BOWMAN CREEK 46.0
END DESCRIPTION:
XS GIS Cut Line= 3
       3583642.1     10261191.62      3583342.11     10259991.64
      3582992.12     10259391.66
#Sta/Elev= 30
  3706.6  284.96  3812.2  284.06  4100.8  277.66  4142.1  276.27  4170.4  272.84
  4183.3  275.09  4219.4  272.69  4224.5  273.75  4343.1   268.6  4448.7   266.1
  4906.7  264.64  4946.4  264.04  4966.7  261.99  4972.9   259.4  4978.6  262.41
  4988.6  257.47  4994.4  259.54  4998.4  256.54  5001.1  256.04  5004.4  256.54
  5010.1  259.55  5015.9  256.96    5018  258.64  5024.5  263.83  5031.6   266.2
  5134.4  265.18  5183.6  264.24  5244.5  265.06  5346.6  269.39  5638.1   288.2
#Mann= 7 ,-1 , 0
  3706.6     .05       0  4906.7     .16       0  4998.4     .07       0
  5004.4     .16       0    5018     .16       0  5134.4     .05       0
  5183.6     .16       0
Bank Sta=4994.4,5010.1
XS Rating Curve= 0 ,0
Exp/Cntr=0.3,0.1

Type RM Length L Ch R = 1 ,47420   ,150,150,150
BEGIN DESCRIPTION:
BOWMAN CREEK 45.0
END DESCRIPTION:
XS GIS Cut Line= 2
      3584648.16     10260294.38      3583207.03     10258686.77
#Sta/Elev= 30
  4328.1  280.46  4476.1  278.38  4553.9  275.63  4645.8  269.26  4723.6  265.42
  4900.8  262.35  4950.1  259.67  4957.6  260.71  4964.3  258.85  4971.8  259.39
    4986  256.54  5003.9  256.08  5006.7  255.58  5009.9  256.08  5028.6  260.11
  5042.8   262.8  5092.1  259.95    5149  261.88  5261.8  261.85  5424.8     266
  5644.6  266.26  5722.4  268.14  5956.4  269.39  6040.8  270.71  6111.8  273.93
    6218  275.96  6232.2  277.34  6352.6  277.89    6381   279.9  6487.1  281.47
#Mann= 3 ,-1 , 0
  4328.1     .05       0  5003.9     .03       0  5009.9     .05       0
Bank Sta=4971.8,5028.6
XS Rating Curve= 0 ,0
Exp/Cntr=0.3,0.1

Type RM Length L Ch R = 1 ,47270   ,327,327,327
BEGIN DESCRIPTION:
BOWMAN CREEK 44.0
END DESCRIPTION:
XS GIS Cut Line= 2
      3584809.58     10260257.88      3583372.13     10258638.14
#Sta/Elev= 30
  4232.3  278.27  4336.1   276.9    4414  277.09  4539.4  273.52  4585.2  270.22
    4586  270.24  4674.1  265.57  4745.1  263.32  4829.6  263.71    4950   262.5
  4971.8  260.92  4992.7  254.71  5003.9  253.38  5006.6  252.88  5009.9  253.38
  5014.4  255.59  5021.1  260.89  5035.3  263.41  5063.8  262.26  5141.5  262.75
  5184.2  261.85  5205.1  262.98  5297.1  263.07  5431.7  265.37  5665.9  271.44
  5878.3  273.57  5956.1  276.76  6154.3  282.04  6282.3  288.16  6397.9  290.35
#Mann= 7 ,-1 , 0
  4232.3     .05       0  4336.1      .1       0    4414     .05       0
  4585.2      .1       0    4586     .05       0  5003.9     .04       0
  5009.9     .05       0
Bank Sta=4950,5035.3
XS Rating Curve= 0 ,0
Exp/Cntr=0.3,0.1

Type RM Length L Ch R = 1 ,46943   ,1446,1446,1446
BEGIN DESCRIPTION:
BOWMAN CREEK 43.0
END DESCRIPTION:
XS GIS Cut Line= 3
      3584866.46     10260252.24      3584918.54      10259922.4
      3583712.46       10258456.
#Sta/Elev= 30
  4078.4  277.23  4139.7  276.26  4200.5  272.69  4376.7  265.74  4410.2  264.25
  4504.3  263.22  4552.8  261.85  4581.5  263.16  4602.3  261.71  4629.7  261.78
  4694.8  260.39  4745.4  260.87  4846.7  261.05  4893.7  261.34  4971.1  261.76
  4996.7  252.55  4999.5  252.05  5002.7  252.55  5007.6  253.15  5021.9  260.14
  5034.9  262.01  5071.5  260.74  5085.8  261.88  5141.9  261.86  5199.2  260.72
  5347.7  263.27  5398.2  263.02  5746.6  271.44  6136.2   286.4    6311  290.88
#Mann= 11 ,-1 , 0
  4078.4     .16       0  4376.7     .05       0  4504.3      .1       0
  4629.7     .05       0  4745.4      .1       0  4846.7     .16       0
  4893.7     .12       0  4996.7     .07       0  5002.7     .12       0
  5141.9      .1       0  5398.2     .05       0
Bank Sta=4971.1,5034.9
XS Rating Curve= 0 ,0
Exp/Cntr=0.3,0.1

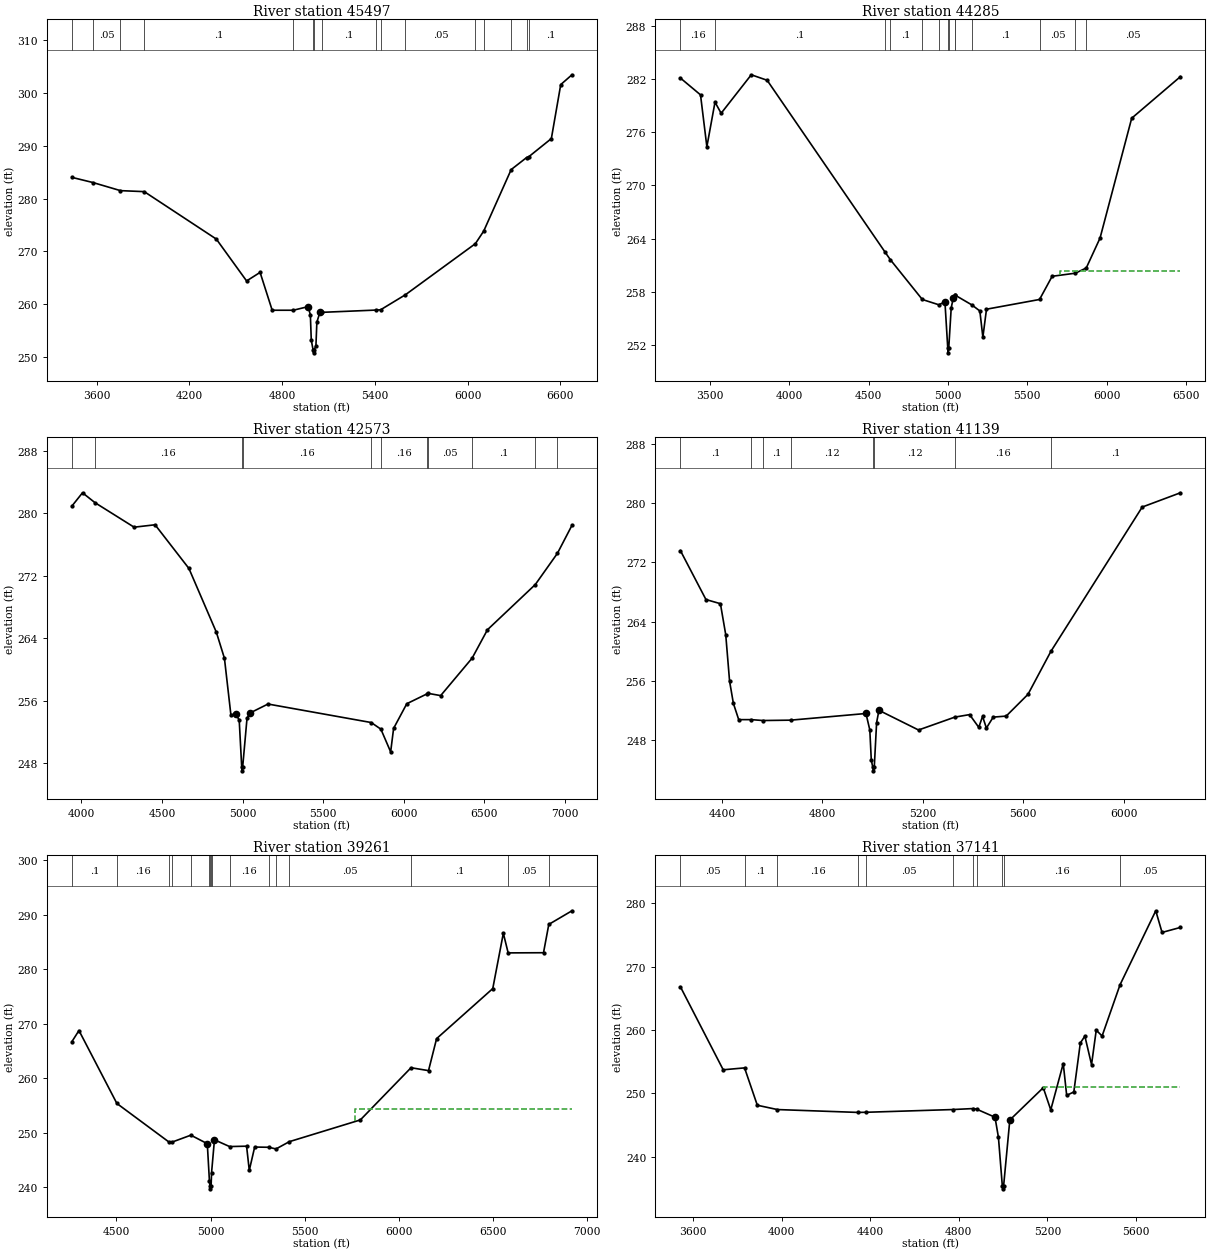
Type RM Length L Ch R = 1 ,45497   ,1212,1212,1212
BEGIN DESCRIPTION:
BOWMAN CREEK 41.0
END DESCRIPTION:
XS GIS Cut Line= 4
      3585899.45     10260382.43      3585882.09     10259462.33
      3584927.22     10258012.67      3584840.42     10257439.75
#Sta/Elev= 30
  3439.9     284  3574.9  283.03  3753.6  281.49  3907.6   281.3  4374.1  272.31
  4569.9  264.38  4657.2     266  4735.5  258.83  4871.9  258.83  4967.4  259.51
  4982.5  257.99  4988.5  253.16  5000.6  251.26  5003.3  250.76  5006.6  251.26
  5018.6  252.09  5024.6  256.57  5045.7  258.55  5054.8  258.43  5405.2  258.86
  5436.8  258.91    5598  261.77  6050.4  271.44  6104.4  273.83  6282.1  285.48
    6382  287.76  6395.4   287.9  6542.1  291.35  6602.8  301.58  6675.5  303.44
#Mann= 16 ,-1 , 0
  3439.9      .1       0  3574.9     .05       0  3753.6     .16       0
  3907.6      .1       0  4871.9     .12       0  5000.6     .07       0
  5006.6     .12       0  5054.8      .1       0  5405.2     .05       0
  5436.8      .1       0    5598     .05       0  6050.4      .1       0
  6104.4     .16       0  6282.1      .1       0    6382     .05       0
  6395.4      .1       0
Bank Sta=4967.4,5045.7
XS Rating Curve= 0 ,0
Exp/Cntr=0.3,0.1

Type RM Length L Ch R = 1 ,44285   ,1712,1712,1712
BEGIN DESCRIPTION:
BOWMAN CREEK 39.0
END DESCRIPTION:
XS GIS Cut Line= 3
      3586402.92     10260278.31      3586385.56     10259063.02
      3585804.38     10257215.39
#Sta/Elev= 30
  3313.7  282.14  3440.4  280.24  3480.4  274.38  3531.7  279.42  3570.4  278.16
  3760.4  282.51  3860.4  281.89  4605.1  262.44    4637  261.62  4838.7  257.12
    4943  256.52  4981.3  256.86  4999.3  251.59    5002  251.09  5005.3  251.59
  5020.9  256.16  5033.7  257.28  5043.8  257.62  5047.3  257.59  5151.6   256.5
  5201.5  255.82  5220.5  252.86  5243.4  256.02  5577.8  257.12  5657.3  259.74
  5803.8  260.09  5872.4  260.68  5959.3  264.06  6158.8   277.6    6466   282.3
#Mann= 14 ,-1 , 0
  3313.7     .16       0  3531.7      .1       0  4605.1     .16       0
    4637      .1       0  4838.7     .16       0    4943     .12       0
  4999.3     .07       0  5005.3     .12       0  5043.8     .16       0
  5047.3     .12       0  5151.6      .1       0  5577.8     .05       0
  5803.8      .1       0  5872.4     .05       0
#XS Ineff= 2 , 0
                         5706.53          260.29
Permanent Ineff=
       F       F
Bank Sta=4981.3,5033.7
XS Rating Curve= 0 ,0
Exp/Cntr=0.3,0.1

Type RM Length L Ch R = 1 ,42573   ,1434,1434,1434
BEGIN DESCRIPTION:
BOWMAN CREEK 37.0
END DESCRIPTION:
XS GIS Cut Line= 3
      3587114.72      10259826.9      3587097.36      10259028.3
      3587192.85     10256727.97
#Sta/Elev= 30
    3942  280.95  4007.3  282.64  4084.9  281.37  4327.4  278.23  4457.4  278.54
  4667.4  272.94  4837.5  264.77  4887.6  261.43  4927.6  254.19  4957.6  254.29
  4979.2  253.52  4994.7  247.51  4997.4  247.01  5000.7  247.51  5027.7  253.76
  5047.7  254.44  5157.8  255.57  5797.9   253.2  5857.9  252.35  5918.5  249.44
  5936.8  252.45  6018.6  255.61  6144.7  256.88  6147.6  256.95  6228.7  256.65
  6424.1  261.46    6519  265.09  6815.6  270.88  6952.8  274.88  7043.1  278.47
#Mann= 11 ,-1 , 0
    3942      .1       0  4084.9     .16       0  4994.7     .07       0
  5000.7     .16       0  5797.9     .12       0  5857.9     .16       0
  6144.7      .1       0  6147.6     .05       0  6424.1      .1       0
  6815.6     .05       0  6952.8      .1       0
Bank Sta=4957.6,5047.7
XS Rating Curve= 0 ,0
Exp/Cntr=0.3,0.1

Type RM Length L Ch R = 1 ,41139   ,1878,1878,1878
BEGIN DESCRIPTION:
BOWMAN CREEK 34.0
END DESCRIPTION:
XS GIS Cut Line= 3
      3588392.08      10258591.6      3587531.39     10257231.42
      3587522.71     10256849.44
#Sta/Elev= 30
  4234.5  273.59  4336.2  266.98  4393.8  266.42    4415  262.23  4430.3  255.95
  4445.5  252.94  4466.7  250.75  4516.8  250.75  4563.5  250.63  4673.9  250.68
  4973.6  251.58  4988.9  249.36  4994.8  245.29  5000.7  244.33  5003.4  243.83
  5006.7  244.33    5016  250.35  5025.3  252.01    5183  249.35  5327.5  251.09
  5386.4  251.43  5422.9  249.71  5438.1  251.19  5453.3  249.61  5480.5  251.09
  5532.2  251.23    5619  254.17    5710  259.96    6074  279.48  6226.2  281.41
#Mann= 8 ,-1 , 0
  4234.5      .1       0  4516.8     .12       0  4563.5      .1       0
  4673.9     .12       0  5000.7     .07       0  5006.7     .12       0
  5327.5     .16       0    5710      .1       0
Bank Sta=4973.6,5025.3
XS Rating Curve= 0 ,0
Exp/Cntr=0.3,0.1

Type RM Length L Ch R = 1 ,39261   ,2120,2120,2120
BEGIN DESCRIPTION:
BOWMAN CREEK 32.0
END DESCRIPTION:
XS GIS Cut Line= 3
      3588796.11     10258318.63      3588842.11     10257591.64
      3587609.52     10256111.63
#Sta/Elev= 30
  4264.2  266.76  4301.3  268.78  4502.6  255.39  4779.6   248.3  4797.1  248.32
  4895.3  249.57  4982.6  248.01  4993.8  241.24  4996.8  240.22  4999.6  239.72
  5002.8  240.22  5005.2  242.65  5020.6  248.72    5101  247.48  5191.2  247.55
  5205.5  243.11  5234.1  247.39  5309.6  247.35  5347.2  247.04  5418.2  248.38
  5795.2  252.37  6064.2  261.95  6157.1  261.42    6200  267.29  6498.2  276.48
  6554.3  286.63  6579.9  283.03  6767.6  283.06  6795.7  288.26  6918.7  290.76
#Mann= 16 ,-1 , 0
  4264.2      .1       0  4502.6     .16       0  4779.6     .05       0
  4797.1     .16       0  4895.3     .05       0  4993.8     .16       0
  4996.8     .07       0  5002.8     .16       0  5005.2     .05       0
    5101     .16       0  5309.6      .1       0  5347.2     .16       0
  5418.2     .05       0  6064.2      .1       0  6579.9     .05       0
  6795.7      .1       0
#XS Ineff= 2 , 0
                         5769.32          254.36
Permanent Ineff=
       F       F
Bank Sta=4982.6,5020.6
XS Rating Curve= 0 ,0
Exp/Cntr=0.3,0.1

Type RM Length L Ch R = 1 ,37141   ,1038,1038,1038
BEGIN DESCRIPTION:
BOWMAN CREEK 30.0
END DESCRIPTION:
XS GIS Cut Line= 3
      3589154.66     10258229.65      3589606.04     10256293.92
      3589831.48     10256146.52
#Sta/Elev= 30
  3543.7  266.84  3736.8  253.74  3833.2  254.04  3890.8  248.14  3981.4  247.46
  4343.4  247.01  4381.2  247.03    4772  247.46  4866.4  247.62    4881  247.52
  4963.7  246.25  4979.2  243.08  4996.7  235.44  4999.5  234.94  5002.7  235.44
  5030.6  245.81  5181.6  250.91  5215.4  247.41  5271.8  254.72  5287.3   249.7
  5319.5  250.24  5348.9  257.97  5369.4  259.06  5399.5  254.56  5420.7  259.99
  5447.2  259.08  5528.2  267.17  5689.4  278.85  5717.8  275.43  5800.7  276.22
#Mann= 11 ,-1 , 0
  3543.7     .05       0  3833.2      .1       0  3981.4     .16       0
  4343.4      .1       0  4381.2     .05       0    4772     .16       0
  4866.4     .05       0    4881     .16       0  4996.7     .07       0
  5002.7     .16       0  5528.2     .05       0
#XS Ineff= 2 , 0
                         5183.24          251.03
Permanent Ineff=
       F       F
Bank Sta=4963.7,5030.6
XS Rating Curve= 0 ,0
Exp/Cntr=0.3,0.1

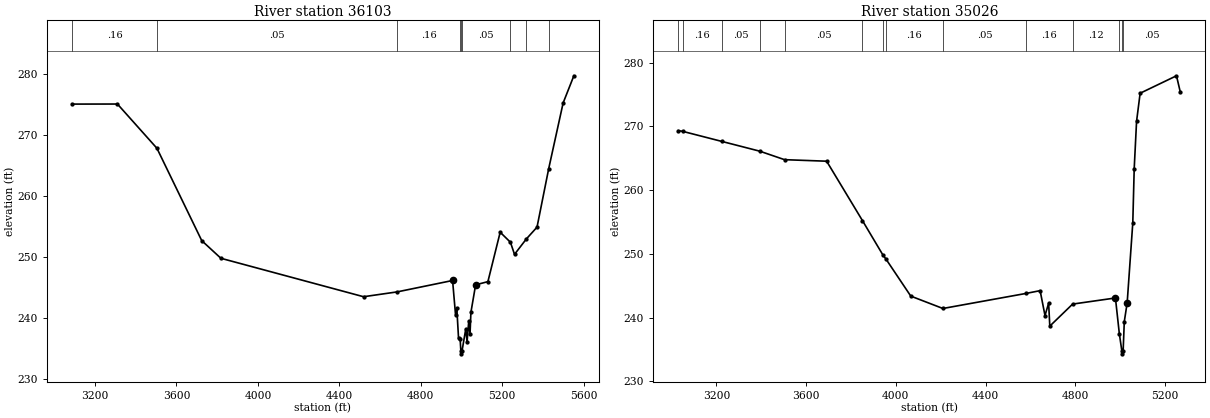
Type RM Length L Ch R = 1 ,36103   ,1077,1077,1077
BEGIN DESCRIPTION:
BOWMAN CREEK 28.0
END DESCRIPTION:
XS GIS Cut Line= 3
      3589135.07     10258726.46      3590292.11     10257141.64
      3590242.11     10256641.67
#Sta/Elev= 30
  3086.9  274.99  3310.2     275  3504.2  267.75  3724.3  252.61  3818.4  249.72
  4518.9  243.42  4683.5  244.21  4956.1  246.08  4970.7   240.4  4976.9  241.51
  4985.4  236.59  4993.2   236.5  4996.6  234.56  4999.4  234.06  5002.6  234.56
  5020.9  238.16  5027.1  235.99  5035.6  239.49  5041.8  237.28    5046  240.84
  5069.2  245.37  5129.5  245.89  5189.8  253.99  5240.1  252.35  5260.2  250.36
  5318.1  252.88  5370.7  254.82  5428.2  264.43  5498.9  275.17  5551.6  279.63
#Mann= 9 ,-1 , 0
  3086.9     .16       0  3504.2     .05       0  4683.5     .16       0
  4993.2     .05       0  4996.6     .04       0  5002.6     .05       0
  5240.1     .16       0  5318.1     .05       0  5428.2     .16       0
Bank Sta=4956.1,5069.2
XS Rating Curve= 0 ,0
Exp/Cntr=0.3,0.1

Type RM Length L Ch R = 1 ,35026   ,2085,2085,2085
BEGIN DESCRIPTION:
BOWMAN CREEK 26.0
END DESCRIPTION:
XS GIS Cut Line= 2
      3591463.22     10258762.94      3590804.41     10256625.25
#Sta/Elev= 30
  3030.9  269.34  3049.5  269.24    3225  267.65  3393.8  266.12  3503.9  264.79
  3691.5  264.55  3851.2  255.22  3941.6  249.87  3955.3  249.22  4066.6  243.37
  4209.7  241.43  4579.7  243.79    4643  244.23  4664.7  240.32  4680.9  242.26
  4686.1  238.66  4787.8  242.12  4978.6  243.08  4995.9   237.5    5007  234.81
  5009.7  234.31    5013  234.81  5018.1  239.37  5030.9  242.31    5056  254.89
  5062.3   263.4  5072.8  270.81  5088.7  275.22  5250.7  277.96  5267.8  275.39
#Mann= 14 ,-1 , 0
  3030.9     .05       0  3049.5     .16       0    3225     .05       0
  3393.8      .1       0  3503.9     .05       0  3851.2     .16       0
  3941.6     .05       0  3955.3     .16       0  4209.7     .05       0
  4579.7     .16       0  4787.8     .12       0  4995.9     .05       0
    5007     .04       0    5013     .05       0
Bank Sta=4978.6,5030.9
XS Rating Curve= 0 ,0
Exp/Cntr=0.3,0.1