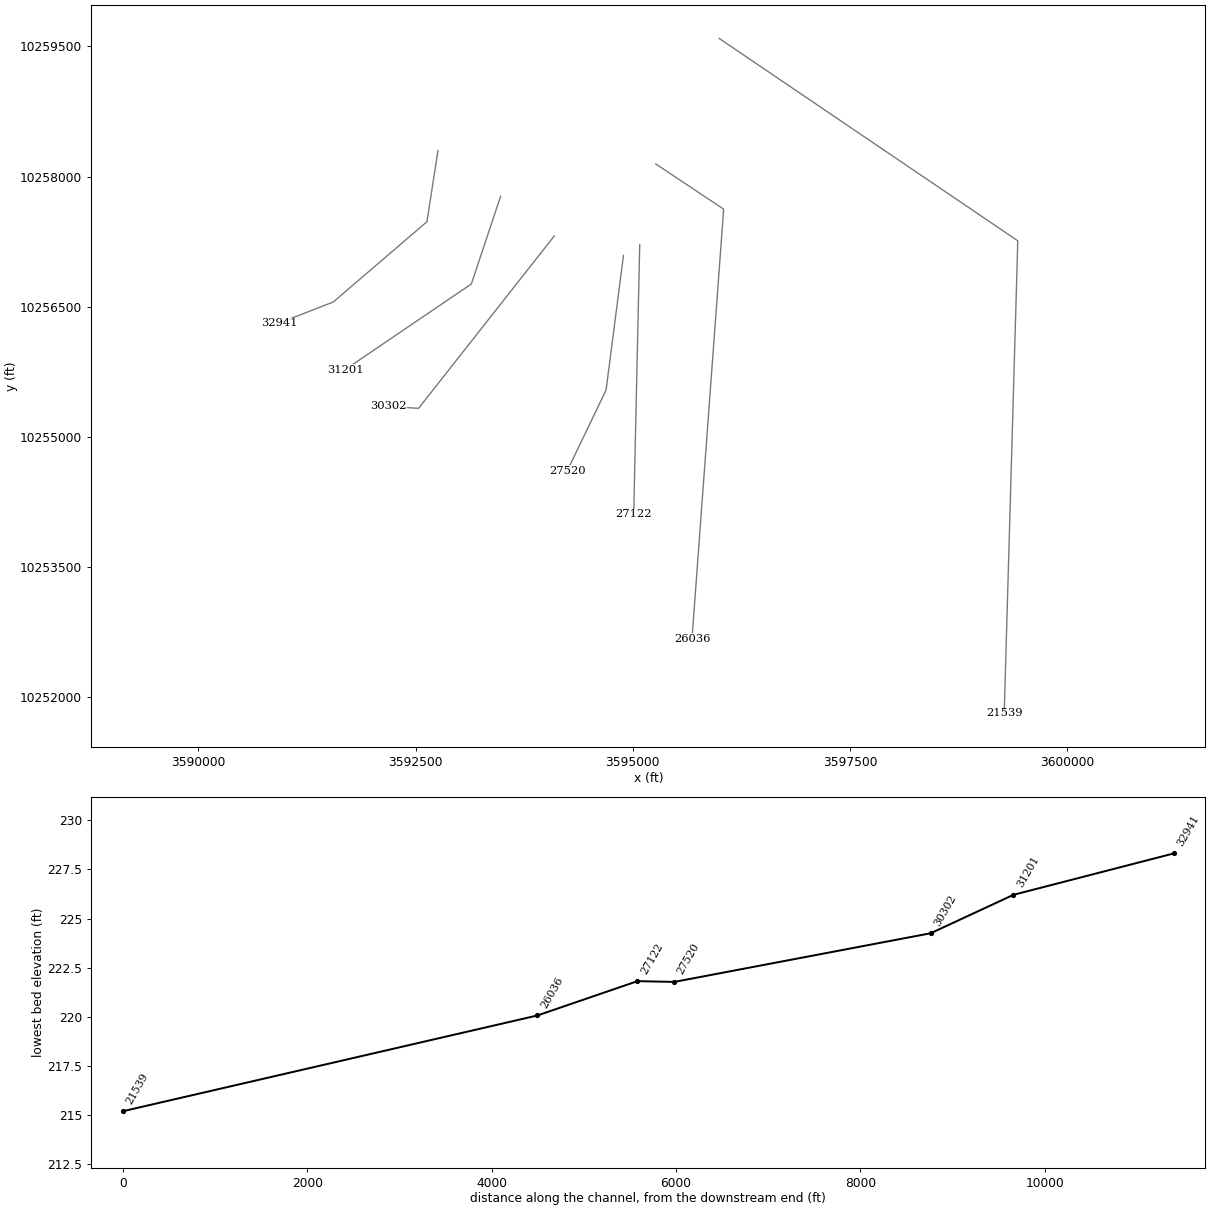
HEC-RAS study BOWMAN CREEK.prj: BOWMAN CREEK Base Level Engineering

--- BOWMAN CREEK.g01 (geometry) --- (continued)

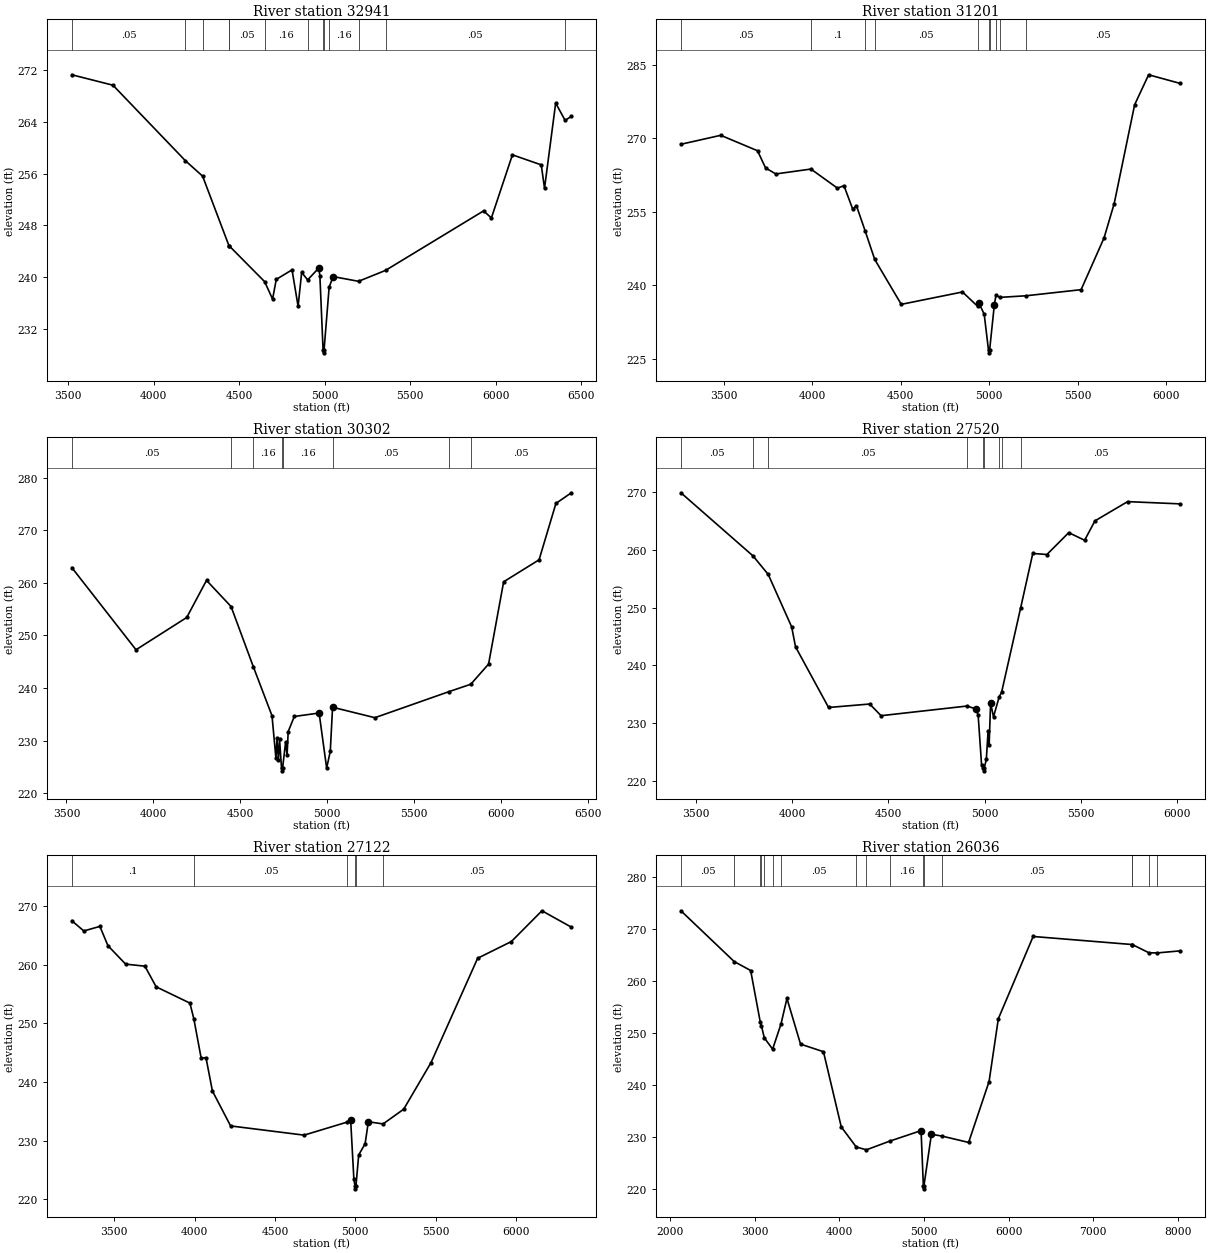
Type RM Length L Ch R = 1 ,32941   ,1740,1740,1740
BEGIN DESCRIPTION:
BOWMAN CREEK 25.0
END DESCRIPTION:
XS GIS Cut Line= 4
      3592757.09     10258299.17      3592630.25     10257479.79
      3591550.49     10256554.34      3590926.26     10256311.59
#Sta/Elev= 30
  3521.4  271.28  3761.8  269.67    4186  257.99  4286.1  255.62  4439.9  244.89
  4440.8  244.87  4648.8  239.32  4695.3  236.62  4716.9  239.67  4809.1  241.14
  4844.5  235.51  4865.4  240.74  4900.4  239.59  4965.3  241.42  4971.9  240.24
  4990.5  228.82  4993.2  228.32  4996.5  228.82  5026.2   238.5  5049.8   240.1
  5197.8  239.37    5356  241.06  5929.1  250.25  5974.8  249.16  6097.8  258.91
  6266.4  257.36  6285.5  253.74  6350.7  266.91  6405.8  264.24  6442.4  264.85
#Mann= 13 ,-1 , 0
  3521.4     .05       0    4186     .16       0  4286.1     .05       0
  4439.9     .16       0  4440.8     .05       0  4648.8     .16       0
  4900.4     .05       0  4990.5     .03       0  4996.5     .05       0
  5026.2     .16       0  5197.8     .12       0    5356     .05       0
  6405.8      .1       0
Bank Sta=4965.3,5049.8
XS Rating Curve= 0 ,0
Exp/Cntr=0.3,0.1

Type RM Length L Ch R = 1 ,31201   ,899,899,899
BEGIN DESCRIPTION:
BOWMAN CREEK 20.0
END DESCRIPTION:
XS GIS Cut Line= 3
      3593477.58     10257771.82       3593141.2     10256762.67
      3591688.21     10255775.94
#Sta/Elev= 30
  3259.6   268.8  3484.4  270.63    3692  267.48  3737.4  263.97  3795.4  262.74
  3993.5  263.74  4143.2  259.84  4180.1  260.34  4229.5  255.55  4250.6  256.25
  4300.5  251.02  4353.6  245.29  4503.6  236.11  4849.2  238.64  4934.8  235.71
    4942  236.39  4971.9  234.08  4996.2  226.71  4998.9  226.21  5002.2  226.71
  5028.8  235.94  5038.1  237.96  5061.6  237.54  5207.5  237.86  5518.9  239.11
  5648.6  249.69  5705.5  256.66  5821.1  276.87  5900.1  282.99  6079.7  281.21
#Mann= 10 ,-1 , 0
  3259.6     .05       0  3993.5      .1       0  4300.5     .12       0
  4353.6     .05       0  4934.8     .16       0  4996.2     .07       0
  5002.2     .16       0  5038.1     .05       0  5061.6     .16       0
  5207.5     .05       0
Bank Sta=4942,5028.8
XS Rating Curve= 0 ,0
Exp/Cntr=0.3,0.1

Type RM Length L Ch R = 1 ,30302   ,2782,2782,2782
BEGIN DESCRIPTION:
BOWMAN CREEK 19.0
END DESCRIPTION:
XS GIS Cut Line= 3
      3594096.06     10257316.06      3592533.56     10255330.38
      3592186.76     10255352.06
#Sta/Elev= 30
  3531.1  262.88  3900.4  247.26  4192.2   253.4  4306.1  260.45  4447.3  255.48
  4576.3  243.96  4682.9  234.72  4705.5  226.63  4711.8   230.4  4719.9  226.24
  4726.3  230.29  4737.7  224.75  4740.5  224.25  4743.7  224.75  4761.5  229.78
  4769.6  227.21    4776  231.71  4811.2  234.58    4954  235.24  4997.3  224.77
  5018.2  227.97  5031.4  236.34  5274.8  234.35  5701.8  239.31  5826.7  240.71
    5929  244.54  6015.7  260.18  6219.6  264.36  6316.6  275.08  6405.3   277.1
#Mann= 8 ,-1 , 0
  3531.1     .05       0  4447.3      .1       0  4576.3     .16       0
  4737.7     .07       0  4743.7     .16       0  5031.4     .05       0
  5701.8     .16       0  5826.7     .05       0
Bank Sta=4954,5031.4
XS Rating Curve= 0 ,0
Exp/Cntr=0.3,0.1

Type RM Length L Ch R = 1 ,27520   ,398,398,398
BEGIN DESCRIPTION:
BOWMAN CREEK 17.0
END DESCRIPTION:
XS GIS Cut Line= 3
      3594892.11     10257091.66      3594692.11     10255541.64
      3594246.46     10254613.45
#Sta/Elev= 30
  3423.8  269.83  3797.9  258.92  3876.8  255.72  3998.5  246.66  4018.7   243.2
  4190.1  232.72  4403.8  233.32  4462.4   231.3  4908.9  232.97  4956.4  232.45
  4966.5  231.34  4984.1  222.84  4992.2  222.27    4995  221.77  4998.2  222.27
  5008.9  223.75  5017.9  228.64  5023.4  226.19    5031  233.47  5046.1  231.11
  5075.8  234.58    5088  235.33  5186.8  249.91  5249.9  259.34  5323.3  259.16
  5436.6  262.94  5519.1  261.62  5572.4  264.97    5742   268.3  6016.3  267.91
#Mann= 9 ,-1 , 0
  3423.8     .05       0  3797.9      .1       0  3876.8     .05       0
  4908.9     .16       0  4992.2     .07       0  4998.2     .16       0
  5075.8     .05       0    5088     .16       0  5186.8     .05       0
Bank Sta=4956.4,5031
XS Rating Curve= 0 ,0
Exp/Cntr=0.3,0.1

Type RM Length L Ch R = 1 ,27122   ,1086,1086,1086
BEGIN DESCRIPTION:
BOWMAN CREEK 16.0
END DESCRIPTION:
XS GIS Cut Line= 2
      3595079.13     10257216.26      3595009.69     10254108.64
#Sta/Elev= 30
    3236  267.49  3310.6  265.75  3410.7  266.53  3460.7  263.24  3570.7   260.1
  3690.7  259.75  3760.8  256.23  3970.8  253.46  3995.2  250.78  4040.8  244.08
  4070.8  244.16  4110.8  238.48    4224  232.53    4681  230.96  4949.1  233.18
  4971.1  233.52  4991.1  223.46  4998.1  222.31  5000.8  221.81  5004.1  222.31
  5021.1  227.58  5061.1   229.5  5081.1  233.24  5172.9  232.87  5301.1  235.38
  5471.2  243.32  5761.3   261.1  5971.3  263.95  6161.4  269.19  6344.4   266.4
#Mann= 6 ,-1 , 0
    3236      .1       0  3995.2     .05       0  4949.1     .16       0
  4998.1     .07       0  5004.1     .16       0  5172.9     .05       0
Bank Sta=4971.1,5081.1
XS Rating Curve= 0 ,0
Exp/Cntr=0.3,0.1

Type RM Length L Ch R = 1 ,26036   ,4497,4497,4497
BEGIN DESCRIPTION:
BOWMAN CREEK 11.0
END DESCRIPTION:
XS GIS Cut Line= 3
      3595264.06     10258145.03      3596045.28     10257624.22
      3595680.71     10252676.45
#Sta/Elev= 30
  2129.7  273.51  2758.9  263.75  2953.4  262.03    3067  252.11  3080.4  251.42
  3114.1   249.1  3212.9  246.91  3311.7  251.74    3382  256.66  3542.5  247.88
  3813.2  246.42  4023.8  231.96  4200.8   228.1  4320.8  227.56    4596  229.23
  4966.3  231.25  4993.4  220.56  4996.2  220.06  4999.4  220.56  5088.3  230.55
  5210.5  230.21  5527.8  228.98  5769.5  240.69  5878.8  252.75  6289.9  268.57
  7460.9  267.02  7462.4  267.01  7658.5  265.43  7757.3  265.41  8029.8  265.81
#Mann= 17 ,-1 , 0
  2129.7     .05       0  2758.9      .1       0    3067     .05       0
  3080.4      .1       0  3114.1     .05       0  3212.9      .1       0
  3311.7     .05       0  4200.8     .16       0  4320.8     .05       0
    4596     .16       0  4993.4     .07       0  4999.4     .16       0
  5210.5     .05       0  7460.9      .1       0  7462.4     .05       0
  7658.5      .1       0  7757.3     .16       0
Bank Sta=4966.3,5088.3
XS Rating Curve= 0 ,0
Exp/Cntr=0.3,0.1

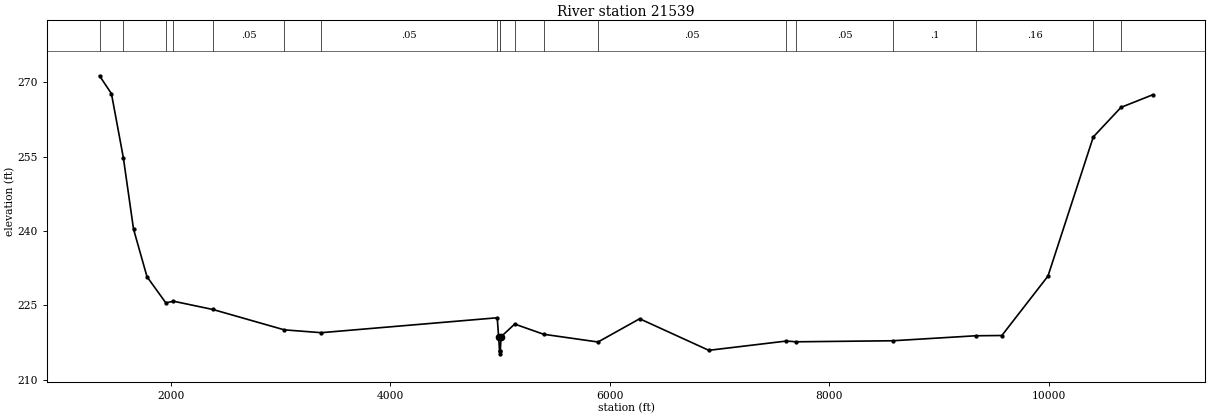
Type RM Length L Ch R = 1 ,21539   ,0,0,0
BEGIN DESCRIPTION:
BOWMAN CREEK 1.0
END DESCRIPTION:
XS GIS Cut Line= 3
      3595992.13     10259591.63       3599430.7     10257259.63
      3599274.45     10251816.93
#Sta/Elev= 30
  1349.7   271.3  1458.4  267.69  1566.9  254.76  1659.6  240.37  1782.4  230.75
  1953.9  225.47  2023.8   225.8  2383.3  224.13  3034.1  220.02  3370.6  219.45
  4974.8  222.46 4987.26  218.61  4995.9  215.68  4998.7  215.18  5001.9  215.68
  5010.3  218.65  5133.8  221.19  5397.9  219.13  5893.3  217.57  6272.8  222.26
    6903  215.89  7609.6  217.76  7699.6  217.61  8580.2  217.82  9337.4  218.83
  9574.1  218.88  9994.3  230.87 10407.5  258.96 10659.8  264.92 10949.4  267.47
#Mann= 19 ,-1 , 0
  1349.7     .05       0  1566.9     .16       0  1953.9     .05       0
  2023.8     .16       0  2383.3     .05       0  3034.1     .16       0
  3370.6     .05       0  4974.8     .16       0  4995.9     .07       0
  5001.9     .16       0  5133.8     .05       0  5397.9     .16       0
  5893.3     .05       0  7609.6      .1       0  7699.6     .05       0
  8580.2      .1       0  9337.4     .16       0 10407.5      .1       0
 10659.8     .05       0
Bank Sta=4987.26,5010.3
XS Rating Curve= 0 ,0
Exp/Cntr=0.3,0.1

Chan Stop Cuts=-1
Use User Specified Reach Order=0
Composite Channel Slope=5