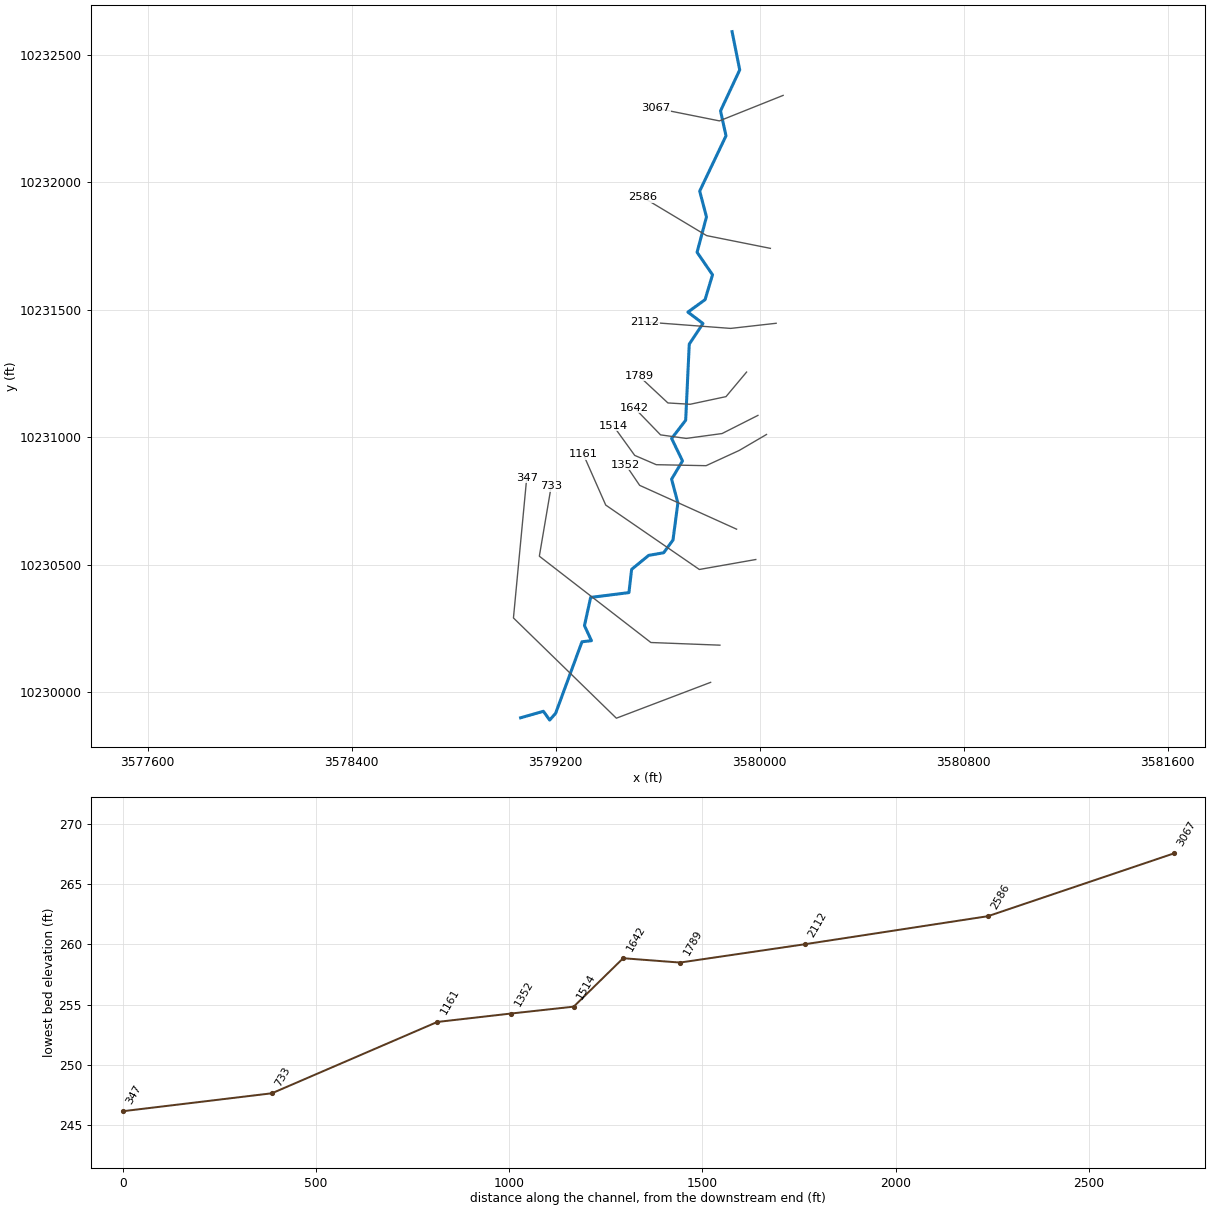
--- BRUSHYCREEKTRIB1.prj (project) ---

Proj Title=BRUSHY CREEK TRIB 10 1
Current Plan=p01
Default Exp/Contr=0.3,0.1
English Units
Geom File=g01
Flow File=f01
Plan File=p01
Y Axis Title=Elevation
X Axis Title(PF)=Main Channel Distance
X Axis Title(XS)=Station
BEGIN DESCRIPTION:
UNT05308 IN WICK
END DESCRIPTION:
DSS Export Rating Curves= 0
DSS Export Rating Curve Sorted= 0
DSS Export Volume Flow Curves= 0
DXF Filename=UNT05308 IN WICK.
DXF OffsetX= 0
DXF OffsetY= 0
DXF ScaleX= 1
DXF ScaleY= 10

--- BRUSHYCREEKTRIB1.p01 (plan) ---

Plan Title=Multiple Run
Short Identifier=Multiple
Geom File=g01
Flow File=f01
Subcritical Flow
K Sum by GR= 0
Std Step Tol= 0.01
Critical Tol= 0.01
Num of Std Step Trials= 20
Max Error Tol= 0.3
Flow Tol Ratio= 0.001
Split Flow NTrial= 30
Split Flow Tol= 0.02
Split Flow Ratio= 0.02
Log Output Level= 0
Friction Slope Method= 1
Unsteady Friction Slope Method= 2
Unsteady Bridges Friction Slope Method= 1
Parabolic Critical Depth
Global Vel Dist=  1 , 1 , 1
Global Log Level= 0
CheckData=True
Encroach Param= -1, 0, 0, 0
BEGIN DESCRIPTION:
Multiple Run
END DESCRIPTION:

--- BRUSHYCREEKTRIB1.f01 (steady flow) ---

Flow Title=Multiple
Program Version=4.10
Number of Profiles= 7
Profile Names=10-year,25-year,50-year,1pct_min,100-year,1pct_plu,500-year
River Rch & RM=UNT05308 IN WICK,Reach-1         ,3067
     230     294     343     295     399     539     538
River Rch & RM=RUSHYCRTR101,Reach-1         ,3067
     230     294     343     295     399     539     538
River Rch & RM=BRUSHYCRTR101,Reach-1         ,3067
     230     294     343     295     399     539     538
Boundary for River Rch & Prof#=BRUSHYCRTR101,Reach-1         , 1
Up Type= 0
Dn Type= 3
Dn Slope=0.005
Boundary for River Rch & Prof#=BRUSHYCRTR101,Reach-1         , 2
Up Type= 0
Dn Type= 3
Dn Slope=0.005
Boundary for River Rch & Prof#=BRUSHYCRTR101,Reach-1         , 3
Up Type= 0
Dn Type= 3
Dn Slope=0.005
Boundary for River Rch & Prof#=BRUSHYCRTR101,Reach-1         , 4
Up Type= 0
Dn Type= 3
Dn Slope=0.005
Boundary for River Rch & Prof#=BRUSHYCRTR101,Reach-1         , 5
Up Type= 0
Dn Type= 3
Dn Slope=0.005
Boundary for River Rch & Prof#=BRUSHYCRTR101,Reach-1         , 6
Up Type= 0
Dn Type= 3
Dn Slope=0.005
Boundary for River Rch & Prof#=BRUSHYCRTR101,Reach-1         , 7
Up Type= 0
Dn Type= 3
Dn Slope=0.005
DSS Import GetInterval= 0
DSS Import GetPeak= 0
DSS Import FillOption= 0

--- BRUSHYCREEKTRIB1.g01 (geometry) ---

Geom Title=Existing Conditions
Program Version=4.10

River Reach=BRUSHYCRTR101   ,Reach-1
Reach XY= 30
       3579891.8     10232591.65      3579921.88     10232441.85
      3579846.54     10232280.81      3579868.03     10232183.11
      3579764.78     10231966.18      3579791.42     10231865.25
      3579754.57     10231726.25      3579815.18     10231637.95
      3579785.83     10231540.35      3579718.61      10231491.6
      3579777.71     10231446.94      3579723.91     10231365.95
      3579709.86     10231067.42      3579654.73      10230995.9
      3579697.38     10230907.96      3579654.61      10230836.2
      3579679.26     10230743.21      3579660.07     10230597.47
      3579623.55     10230547.77      3579564.53      10230537.3
      3579497.88     10230482.51      3579487.28     10230391.46
      3579337.14     10230372.45      3579312.84     10230261.86
      3579340.27     10230202.83      3579303.08     10230198.52
      3579199.81     10229918.03      3579176.37     10229891.47
      3579151.89     10229925.84      3579062.52     10229900.42

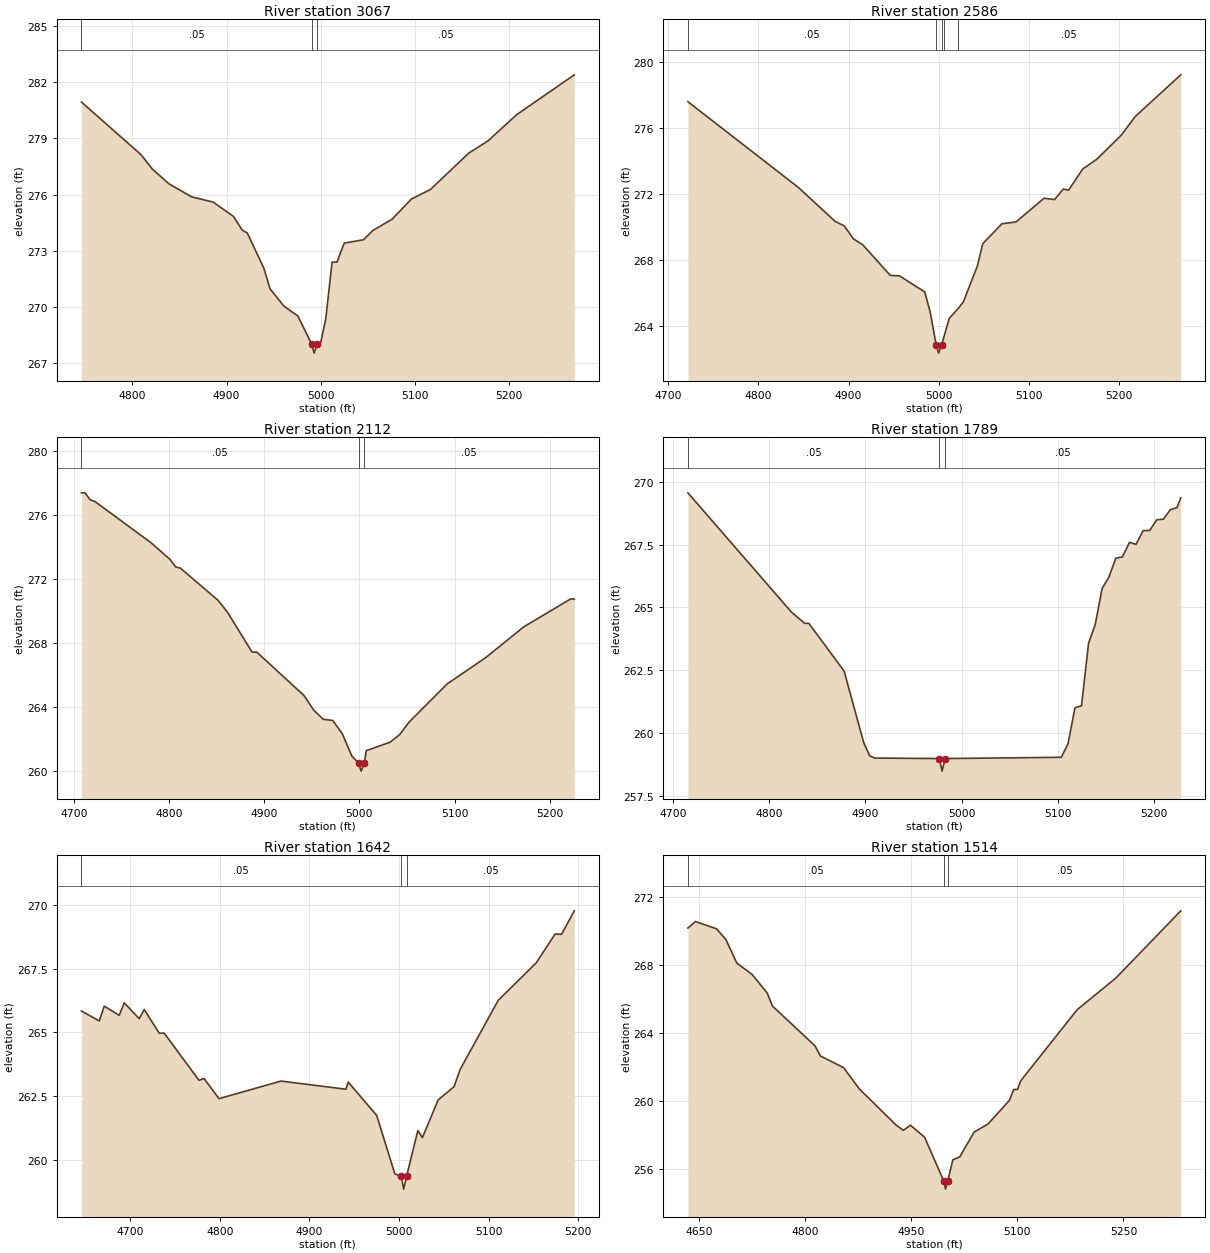
Type RM Length L Ch R = 1 ,3067    ,481,481,481
BEGIN DESCRIPTION:
UNT05308 IN WICK 6.0
END DESCRIPTION:
XS GIS Cut Line= 3
      3580092.12     10232341.65      3579842.11     10232241.64
      3579592.12     10232291.64
#Sta/Elev= 30
  4745.7  280.93    4809  278.13  4821.1  277.36  4838.6  276.58  4862.8  275.88
  4885.7   275.6  4907.3  274.84  4916.7  274.11  4922.1  273.95  4939.6  272.09
  4946.3  270.98  4961.1  270.05  4975.9  269.53  4990.4  268.05  4993.2  267.55
  4996.4  268.05  5000.2  268.11  5005.5  269.36  5012.3   272.4  5017.5   272.4
  5025.2  273.41  5045.6  273.59  5055.8  274.09  5076.2  274.69  5096.6  275.76
  5116.9  276.27  5157.7  278.21  5178.1  278.86  5208.7  280.26  5269.9  282.38
#Mann= 3 ,-1 , 0
  4745.7     .05       0  4990.4     .03       0  4996.4     .05       0
Bank Sta=4990.4,4996.4
XS Rating Curve= 0 ,0
Exp/Cntr=0.3,0.1

Type RM Length L Ch R = 1 ,2586    ,474,474,474
BEGIN DESCRIPTION:
UNT05308 IN WICK 5.0
END DESCRIPTION:
XS GIS Cut Line= 3
      3580042.11     10231741.64      3579792.11     10231791.64
      3579542.11     10231941.64
#Sta/Elev= 30
  4721.9   277.6  4844.3   272.4  4885.1  270.34  4895.3  270.06  4905.5  269.27
  4915.7  268.92  4946.3  267.06  4956.5  267.03  4984.6  266.05  4990.5  264.84
  4997.2  262.84  4999.9  262.34  5003.2  262.84  5005.7  263.31  5011.8  264.46
  5021.2  265.02  5027.4  265.46  5042.9  267.63  5048.8  268.98  5070.1  270.19
  5085.7   270.3  5116.8  271.74  5128.5  271.66  5138.2   272.3    5144  272.23
  5159.6  273.51  5175.1   274.1  5202.3  275.56  5217.9   276.7  5268.4  279.23
#Mann= 5 ,-1 , 0
  4721.9     .05       0  4997.2     .03       0  5003.2     .05       0
  5005.7      .1       0  5021.2     .05       0
Bank Sta=4997.2,5003.2
XS Rating Curve= 0 ,0
Exp/Cntr=0.3,0.1

Type RM Length L Ch R = 1 ,2112    ,323,323,323
BEGIN DESCRIPTION:
UNT05308 IN WICK 4.0
END DESCRIPTION:
XS GIS Cut Line= 3
      3580064.74     10231447.81      3579886.23     10231427.67
      3579549.13     10231453.03
#Sta/Elev= 30
    4708  277.41  4711.8  277.41  4717.1  276.98  4722.1  276.87  4781.1  274.29
  4801.2  273.24  4806.9  272.78    4812   272.7  4851.5  270.69  4861.6  269.93
  4887.2  267.45  4892.2  267.45  4941.9  264.73    4952  263.82    4962  263.25
    4972  263.18    4982  262.35  4992.1  260.95  4999.1  260.51  5001.8  260.01
  5005.1  260.51  5007.2  261.29  5032.2  261.82  5042.2  262.29  5052.2  263.08
  5092.3  265.47  5132.5   267.1  5172.6  269.03  5221.7  270.77  5225.7  270.77
#Mann= 3 ,-1 , 0
    4708     .05       0  4999.1     .03       0  5005.1     .05       0
Bank Sta=4999.1,5005.1
XS Rating Curve= 0 ,0
Exp/Cntr=0.3,0.1

Type RM Length L Ch R = 1 ,1789    ,147,147,147
BEGIN DESCRIPTION:
Mapping XS 9bbaeb5c
END DESCRIPTION:
XS GIS Cut Line= 5
      3579948.72     10231256.41      3579867.99     10231160.06
      3579727.37     10231130.11      3579640.13     10231135.32
      3579526.34     10231241.35
#Sta/Elev= 30
  4715.5  269.56  4823.3  264.81  4836.9  264.37  4841.2  264.37  4877.9  262.47
  4898.3  259.62  4904.5   259.1  4909.6  259.01    4977  258.99  4979.7  258.49
    4983  258.99  5103.7  259.04  5110.7  259.58  5117.9  261.01  5124.7  261.09
  5132.1  263.59  5138.9  264.31  5146.2  265.76  5153.1   266.2  5160.4  266.96
  5167.2  267.01  5174.6  267.59  5181.4  267.51  5188.8  268.06  5195.6  268.06
  5202.9  268.49  5209.8  268.51  5217.1  268.89  5223.9  268.97  5227.9  269.36
#Mann= 3 ,-1 , 0
  4715.5     .05       0    4977     .03       0    4983     .05       0
Bank Sta=4977,4983
XS Rating Curve= 0 ,0
Exp/Cntr=0.3,0.1

Type RM Length L Ch R = 1 ,1642    ,128,128,128
BEGIN DESCRIPTION:
Mapping XS b9ca2c3a
END DESCRIPTION:
XS GIS Cut Line= 5
      3579993.26     10231086.48       3579852.6     10231015.28
      3579711.98     10230996.18      3579611.28     10231010.07
      3579507.57     10231117.18
#Sta/Elev= 30
  4645.5  265.84  4665.4  265.45    4671  266.03  4687.7  265.67  4693.3  266.16
    4710  265.54  4715.6   265.9  4732.3  264.97  4737.9  264.97  4776.8  263.12
  4782.4  263.19  4799.1   262.4  4868.3  263.09  4940.8  262.77  4943.4  263.05
  4975.2  261.74  4995.4  259.45  5002.5  259.35  5005.3  258.85  5008.5  259.35
  5021.1  261.15  5026.2  260.87  5043.8  262.35  5061.5  262.87  5068.4  263.55
  5110.9  266.26  5153.3  267.73  5174.4  268.86  5181.6  268.85  5195.8  269.77
#Mann= 3 ,-1 , 0
  4645.5     .05       0  5002.5     .03       0  5008.5     .05       0
Bank Sta=5002.5,5008.5
XS Rating Curve= 0 ,0
Exp/Cntr=0.3,0.1

Type RM Length L Ch R = 1 ,1514    ,162,162,162
BEGIN DESCRIPTION:
Mapping XS c587fd13
END DESCRIPTION:
XS GIS Cut Line= 6
      3580026.88     10231011.64      3579920.08     10230949.12
      3579789.87     10230889.23      3579594.56     10230893.13
      3579509.92     10230929.59      3579426.25     10231045.45
#Sta/Elev= 30
  4633.7  270.15  4644.3  270.53    4674  270.11  4687.3  269.49    4703  268.09
  4724.5  267.43  4745.9  266.34  4753.4  265.57  4813.5  263.24  4821.3  262.64
    4854  261.96  4876.3  260.71  4928.6  258.58  4938.6  258.28  4948.6  258.58
  4968.6  257.88  4995.6  255.33  4998.3  254.83  5001.6  255.33  5008.6  256.55
  5018.6  256.73  5038.6  258.17  5058.6  258.66  5088.6  260.03  5094.9  260.68
  5100.2  260.68  5104.6  261.18  5184.6  265.36  5239.2  267.21  5331.2  271.16
#Mann= 3 ,-1 , 0
  4633.7     .05       0  4995.6     .03       0  5001.6     .05       0
Bank Sta=4995.6,5001.6
XS Rating Curve= 0 ,0
Exp/Cntr=0.3,0.1

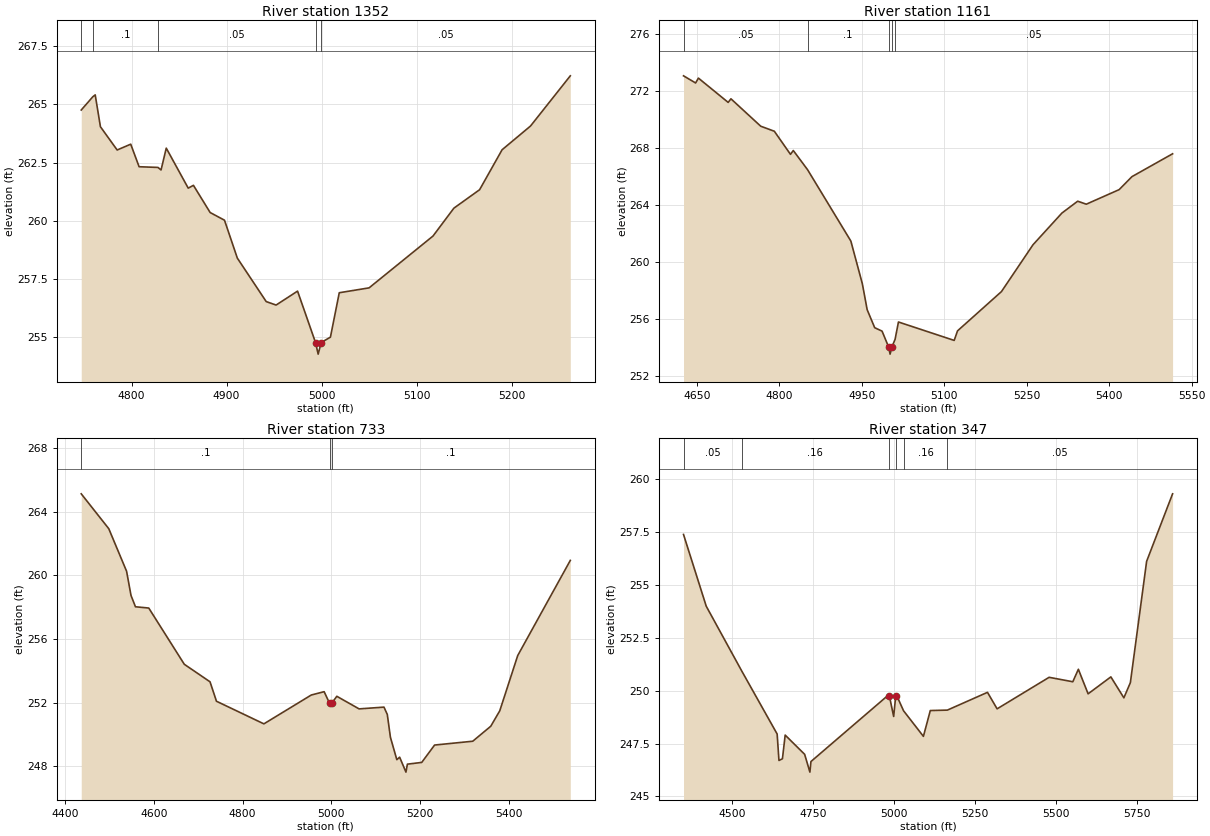
Type RM Length L Ch R = 1 ,1352    ,191,191,191
BEGIN DESCRIPTION:
Mapping XS 3effba3e
END DESCRIPTION:
XS GIS Cut Line= 3
      3579909.56     10230640.19      3579529.36     10230812.06
      3579474.64     10230892.83
#Sta/Elev= 30
  4747.1  264.76  4759.3  265.33  4761.8  265.41  4767.3  264.04  4784.9  263.04
  4799.2  263.29    4808  262.32  4827.9  262.29  4831.1  262.18  4836.6  263.12
  4859.7   261.4  4865.2  261.52  4882.8  260.35  4897.9  260.02  4911.4  258.39
  4941.8  256.52  4952.2  256.37  4974.8  256.97  4993.7  254.76  4996.5  254.26
  4999.7  254.76  5009.4  254.99  5018.7   256.9  5050.1  257.11  5117.4  259.34
  5139.4  260.54  5166.4  261.33  5190.1  263.05    5220  264.07  5261.9  266.23
#Mann= 5 ,-1 , 0
  4747.1     .05       0  4759.3      .1       0  4827.9     .05       0
  4993.7     .03       0  4999.7     .05       0
Bank Sta=4993.7,4999.7
XS Rating Curve= 0 ,0
Exp/Cntr=0.3,0.1

Type RM Length L Ch R = 1 ,1161    ,428,428,428
BEGIN DESCRIPTION:
Mapping XS 420c3e65
END DESCRIPTION:
XS GIS Cut Line= 4
      3579984.84     10230521.16      3579763.48     10230482.09
      3579396.29      10230734.7      3579307.74     10230935.25
#Sta/Elev= 30
  4625.6  273.05  4647.6  272.55  4652.7  272.89  4706.8  271.19  4711.9  271.44
  4766.1  269.52  4790.8  269.17  4820.2  267.55  4825.3  267.82  4851.2  266.48
    4930  261.48  4950.9  258.49  4959.7  256.67  4973.4  255.41  4986.8  255.17
  4998.7  254.06  5001.4  253.56  5004.7  254.06  5010.5   254.6  5016.6  255.81
    5118  254.52  5124.1  255.19    5204  257.94  5261.4  261.22    5314  263.44
  5342.7  264.27  5358.3  264.06  5418.1  265.08  5441.4  265.99  5515.3  267.59
#Mann= 5 ,-1 , 0
  4625.6     .05       0  4851.2      .1       0  4998.7     .07       0
  5004.7      .1       0  5010.5     .05       0
Bank Sta=4998.7,5004.7
XS Rating Curve= 0 ,0
Exp/Cntr=0.3,0.1

Type RM Length L Ch R = 1 ,733     ,386,386,386
BEGIN DESCRIPTION:
Mapping XS 94538e73
END DESCRIPTION:
XS GIS Cut Line= 4
      3579844.21     10230185.22      3579573.38     10230195.64
      3579135.88     10230534.18      3579182.45     10230808.43
#Sta/Elev= 30
  4436.5  265.11  4498.6  262.92  4538.7  260.25  4548.7  258.73  4558.7  258.02
  4588.7  257.94  4668.8  254.41  4726.8  253.31  4741.3  252.09  4848.2  250.67
    4955  252.48    4984  252.69 4996.25  251.96 5000.94  251.96  5012.6   252.4
  5062.8  251.61  5118.9  251.72  5126.4  251.26  5133.4  249.83  5147.9  248.42
  5154.2  248.58  5168.4  247.64  5171.7  248.14    5204  248.25    5233  249.34
    5319  249.58  5359.6  250.52  5379.9  251.49  5420.4  254.96  5538.9  260.93
#Mann= 3 , 0 , 0
  4436.5      .1       0 4996.25     .03       0 5000.94      .1       0
#Block Obstruct= 2 , 0
         4938.19  252.01 5028.83          252.05
Bank Sta=4996.25,5000.94
XS Rating Curve= 0 ,0
Exp/Cntr=0.3,0.1

Type RM Length L Ch R = 1 ,347     ,0,0,0
BEGIN DESCRIPTION:
UNT05308 IN WICK 1.0
END DESCRIPTION:
XS GIS Cut Line= 4
      3579807.75     10230039.39      3579437.96     10229898.76
      3579034.31     10230291.99       3579086.4     10230841.47
#Sta/Elev= 30
  4349.6  257.38  4419.8  253.99  4529.1  250.94  4638.9  247.95  4644.5   246.7
  4655.2  246.78  4663.7   247.9  4723.9  246.99  4740.1  246.15  4743.3  246.65
  4984.8  249.82 4985.34  249.77  4998.9  248.78 5005.35  249.76  5005.9  249.85
  5029.4  249.05  5090.8  247.84  5112.1  249.06  5164.8  249.08  5288.8  249.92
  5318.5  249.14  5479.2  250.63  5552.4  250.42  5569.6  251.01  5599.7  249.85
    5670  250.65  5710.2  249.66  5730.3  250.38  5780.5  256.11  5860.7   259.3
#Mann= 6 ,-1 , 0
  4349.6     .05       0  4529.1     .16       0  4984.8     .07       0
  5005.9     .12       0  5029.4     .16       0  5164.8     .05       0
#Block Obstruct= 2 , 0
         4967.72  249.35 5024.77          249.34
Bank Sta=4985.34,5005.35
XS Rating Curve= 0 ,0
Exp/Cntr=0.3,0.1

Chan Stop Cuts=-1
Use User Specified Reach Order=0
Composite Channel Slope=5