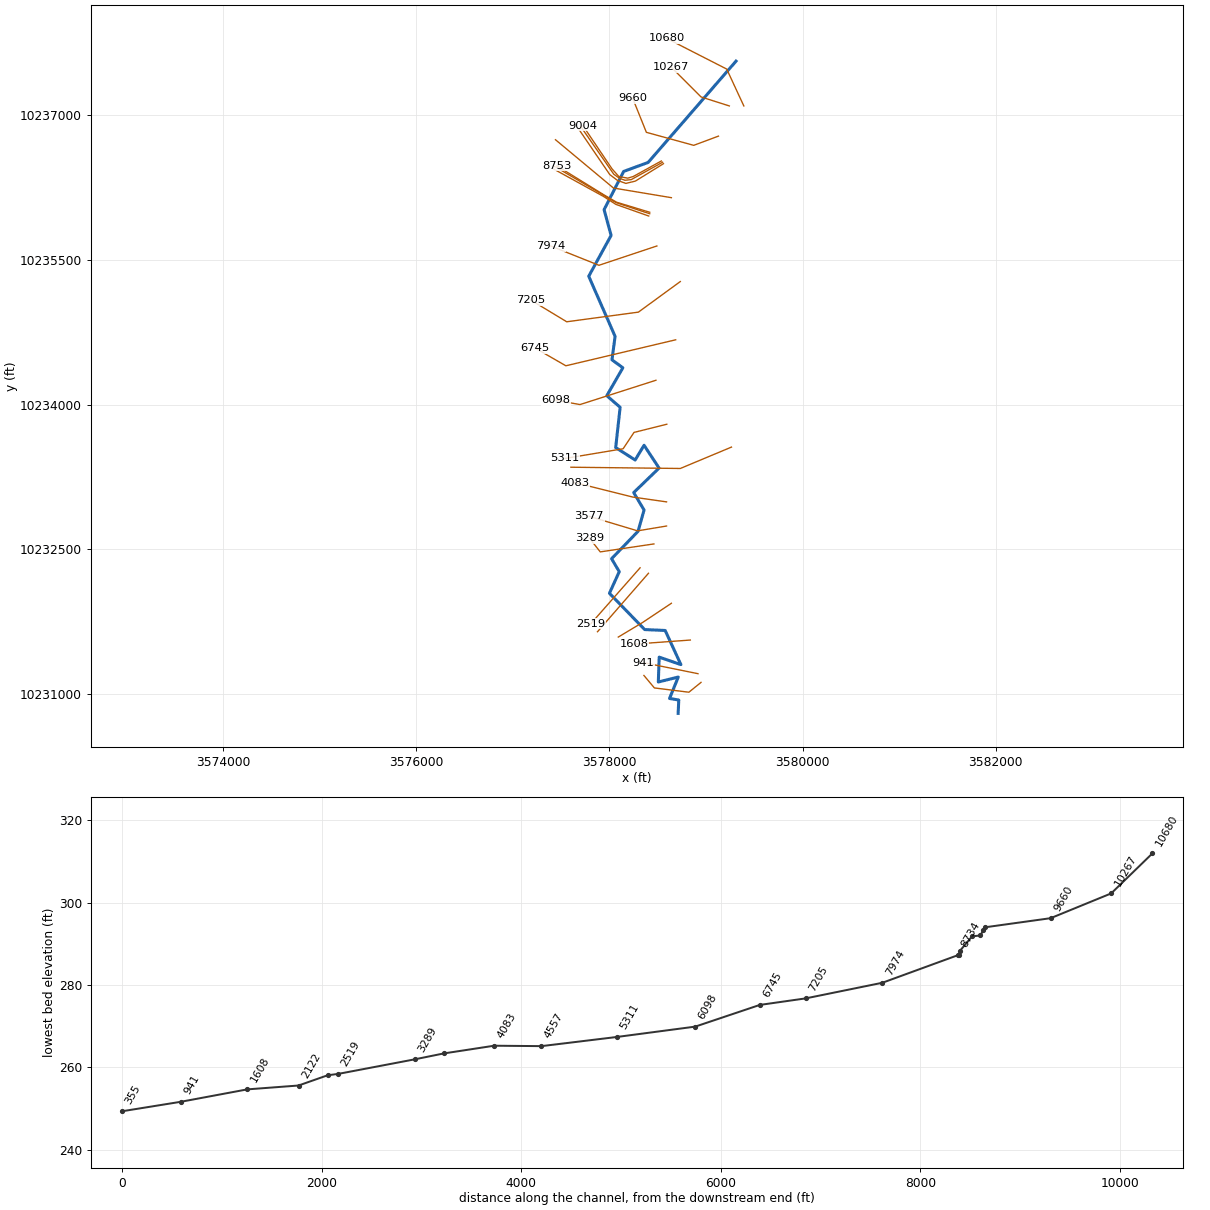
--- BRUSHYCREEKTRIB10.prj (project) ---

Proj Title=BRUSHY CREEK TRIB 10 2
Current Plan=p01
Default Exp/Contr=0.3,0.1
English Units
Geom File=g01
Flow File=f01
Plan File=p01
Y Axis Title=Elevation
X Axis Title(PF)=Main Channel Distance
X Axis Title(XS)=Station
BEGIN DESCRIPTION:
UNT05307 IN WICK
END DESCRIPTION:
DSS Export Rating Curves= 0
DSS Export Rating Curve Sorted= 0
DSS Export Volume Flow Curves= 0
DXF Filename=UNT05307 IN WICK.
DXF OffsetX= 0
DXF OffsetY= 0
DXF ScaleX= 1
DXF ScaleY= 10

--- BRUSHYCREEKTRIB10.p01 (plan) ---

Plan Title=Multiple Run
Short Identifier=Multiple
Geom File=g01
Flow File=f01
Subcritical Flow
K Sum by GR= 0
Std Step Tol= 0.01
Critical Tol= 0.01
Num of Std Step Trials= 20
Max Error Tol= 0.3
Flow Tol Ratio= 0.001
Split Flow NTrial= 30
Split Flow Tol= 0.02
Split Flow Ratio= 0.02
Log Output Level= 0
Friction Slope Method= 1
Unsteady Friction Slope Method= 2
Unsteady Bridges Friction Slope Method= 1
Parabolic Critical Depth
Global Vel Dist=  1 , 1 , 1
Global Log Level= 0
CheckData=True
Encroach Param= -1, 0, 0, 0
BEGIN DESCRIPTION:
Multiple Run
END DESCRIPTION:

--- BRUSHYCREEKTRIB10.f01 (steady flow) ---

Flow Title=Multiple
Program Version=4.10
Number of Profiles= 7
Profile Names=10-year,25-year,50-year,1pct_min,100-year,1pct_plu,500-year
River Rch & RM=UNT05307 IN WICK,Reach-1         ,10680
     372     487     578     504     681     921     947
River Rch & RM=BRUSHYCRTR102,Reach-1         ,10680
     372     487     578     504     681     921     947
Boundary for River Rch & Prof#=BRUSHYCRTR102,Reach-1         , 1
Up Type= 0
Dn Type= 3
Dn Slope=0.005
Boundary for River Rch & Prof#=BRUSHYCRTR102,Reach-1         , 2
Up Type= 0
Dn Type= 3
Dn Slope=0.005
Boundary for River Rch & Prof#=BRUSHYCRTR102,Reach-1         , 3
Up Type= 0
Dn Type= 3
Dn Slope=0.005
Boundary for River Rch & Prof#=BRUSHYCRTR102,Reach-1         , 4
Up Type= 0
Dn Type= 3
Dn Slope=0.005
Boundary for River Rch & Prof#=BRUSHYCRTR102,Reach-1         , 5
Up Type= 0
Dn Type= 3
Dn Slope=0.005
Boundary for River Rch & Prof#=BRUSHYCRTR102,Reach-1         , 6
Up Type= 0
Dn Type= 3
Dn Slope=0.005
Boundary for River Rch & Prof#=BRUSHYCRTR102,Reach-1         , 7
Up Type= 0
Dn Type= 3
Dn Slope=0.005
DSS Import GetInterval= 0
DSS Import GetPeak= 0
DSS Import FillOption= 0

--- BRUSHYCREEKTRIB10.g01 (geometry) ---

Geom Title=Existing Conditions
Program Version=4.10

River Reach=BRUSHYCRTR102   ,Reach-1
Reach XY= 30
      3579311.75     10237555.78      3578401.48     10236506.61
      3578147.58      10236413.3       3577945.3     10236017.89
        3578018.     10235750.96      3577786.36     10235328.08
      3578059.16     10234705.46       3578026.8     10234462.45
      3578139.74     10234380.29      3577973.33     10234091.16
      3578111.42      10233971.1      3578065.36     10233554.01
       3578266.9      10233425.4      3578359.23     10233577.81
      3578514.58     10233341.75      3578251.71     10233087.69
      3578359.35     10232907.13      3578296.53      10232686.6
      3578022.85     10232403.09      3578102.28     10232268.98
      3578000.71     10232045.02       3578365.6     10231669.44
      3578577.72     10231660.11       3578740.7      10231306.6
      3578515.91     10231383.84      3578506.81     10231126.61
      3578713.36     10231177.93      3578623.06     10230955.91
      3578718.63     10230940.02      3578712.11     10230801.64

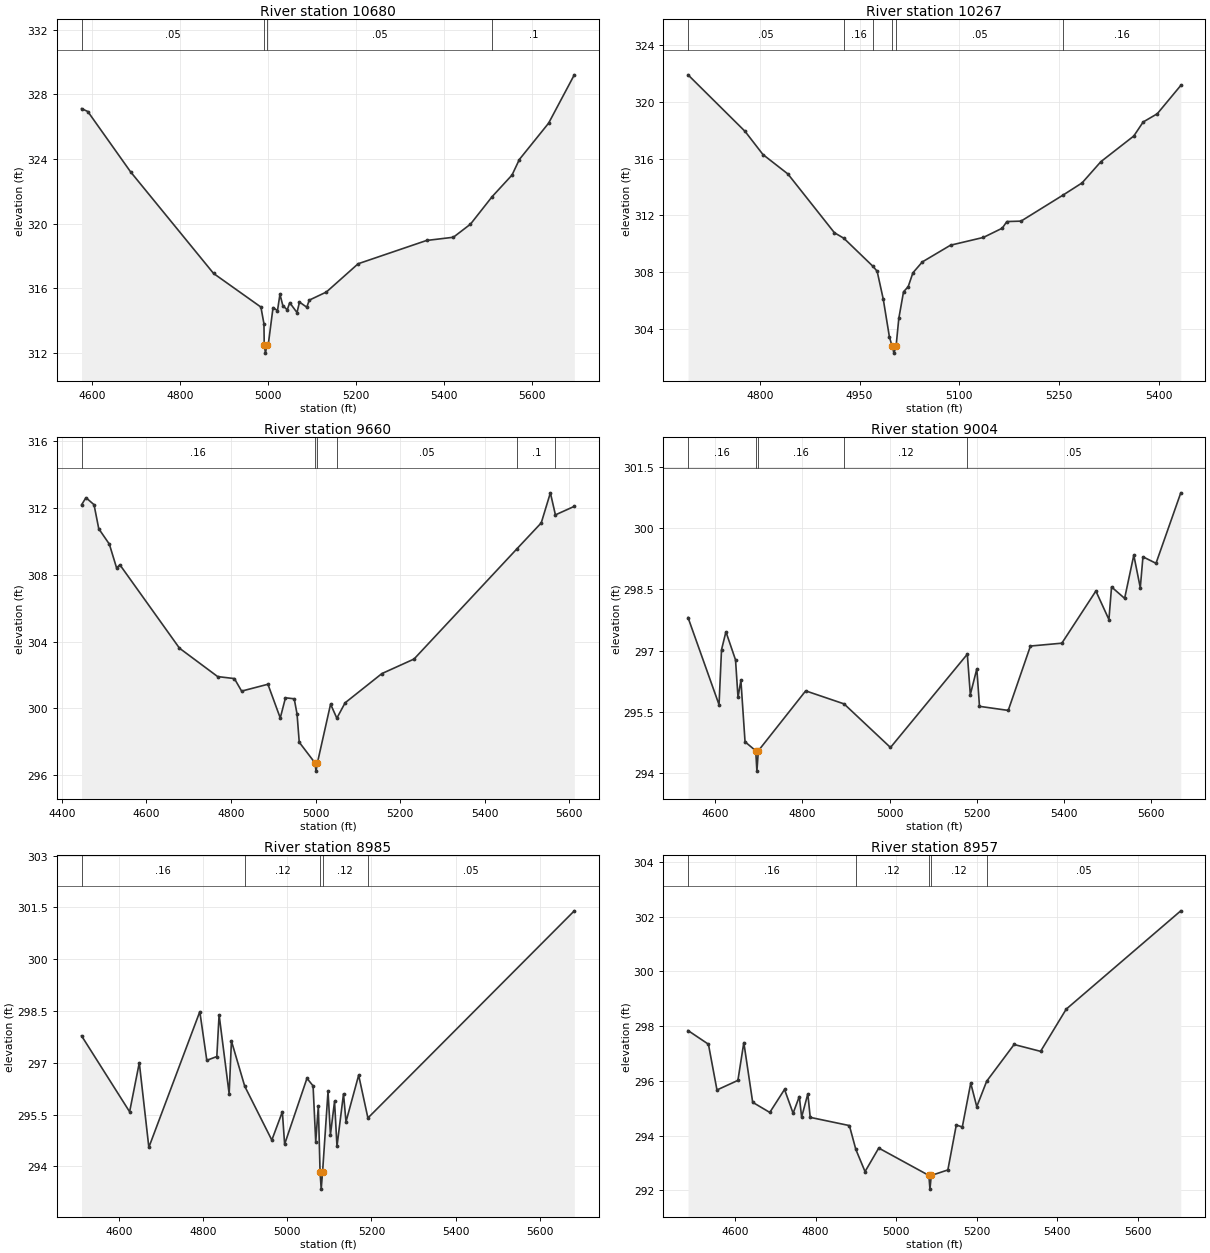
Type RM Length L Ch R = 1 ,10680   ,413,413,413
BEGIN DESCRIPTION:
UNT05307 IN WICK 19.0
END DESCRIPTION:
XS GIS Cut Line= 3
      3579392.11     10237091.63      3579215.18     10237473.32
      3578592.09     10237791.65
#Sta/Elev= 30
    4576  327.12  4590.2  326.94  4687.4  323.21  4876.2  316.92  4983.8  314.84
  4990.7  313.81  4991.4  312.49  4994.2  311.99  4997.4  312.49  5000.4  312.49
  5011.4  314.81  5021.5  314.62  5027.1  315.63  5033.8  314.92  5043.7  314.67
  5049.3  315.11  5065.9   314.5  5071.5  315.15  5088.1  314.83  5093.8  315.27
  5132.6  315.77  5204.9  317.52  5360.4  318.96  5421.4  319.16  5460.3  319.97
  5509.8  321.68  5554.8  323.01  5571.4  323.97    5638  326.22  5696.4  329.21
#Mann= 4 ,-1 , 0
    4576     .05       0  4991.4     .04       0  4997.4     .05       0
  5509.8      .1       0
Bank Sta=4991.4,4997.4
XS Rating Curve= 0 ,0
Exp/Cntr=0.3,0.1

Type RM Length L Ch R = 1 ,10267   ,607,607,607
BEGIN DESCRIPTION:
UNT05307 IN WICK 18.0
END DESCRIPTION:
XS GIS Cut Line= 3
      3579242.08     10237091.65      3578949.34     10237184.69
      3578642.08     10237491.67
#Sta/Elev= 30
  4691.9  321.92  4777.7  317.93  4804.7  316.29  4842.2  314.92  4912.2  310.77
  4926.4  310.38  4970.4  308.39  4976.5  308.05  4985.7  306.08    4995   303.4
    4999  302.77  5001.8  302.27    5005  302.77  5009.1  304.72  5016.2   306.6
  5023.2  306.96  5030.3  307.94  5044.5  308.71  5086.9  309.89  5136.4  310.44
  5164.7  311.09  5171.7  311.56    5193  311.59  5256.6  313.44  5284.9  314.29
  5313.2  315.79  5362.7   317.6  5376.8  318.59    5398  319.17  5433.4  321.17
#Mann= 6 ,-1 , 0
  4691.9     .05       0  4926.4     .16       0  4970.4     .05       0
    4999     .03       0    5005     .05       0  5256.6     .16       0
Bank Sta=4999,5005
XS Rating Curve= 0 ,0
Exp/Cntr=0.3,0.1

Type RM Length L Ch R = 1 ,9660    ,656,656,656
BEGIN DESCRIPTION:
UNT05307 IN WICK 17.0
END DESCRIPTION:
XS GIS Cut Line= 4
      3579129.73     10236779.19      3578873.67     10236683.71
      3578383.22     10236818.26      3578239.99     10237174.16
#Sta/Elev= 30
  4446.5  312.19  4456.9  312.62    4476   312.2  4487.2  310.76  4512.2  309.84
  4529.3  308.42  4537.2   308.6  4678.1  303.61  4768.4  301.91    4808  301.79
  4825.1  301.04  4887.3  301.45  4916.5  299.43  4928.8  300.64  4949.5  300.58
  4956.2  299.67  4961.4  297.98  4998.4  296.75  5001.1  296.25  5004.4  296.75
  5035.5  300.26  5050.3  299.42  5069.9  300.34  5156.9  302.09  5232.9  302.96
  5476.7  309.57  5533.8  311.11  5555.4  312.91  5567.3  311.59    5612   312.1
#Mann= 6 ,-1 , 0
  4446.5     .16       0  4998.4     .07       0  5004.4     .16       0
  5050.3     .05       0  5476.7      .1       0  5567.3     .16       0
Bank Sta=4998.4,5004.4
XS Rating Curve= 0 ,0
Exp/Cntr=0.3,0.1

Type RM Length L Ch R = 1 ,9004    ,19,19,19
BEGIN DESCRIPTION:
Mapping XS abc97417
END DESCRIPTION:
XS GIS Cut Line= 6
      3578538.17     10236521.66       3578247.4     10236361.08
      3578190.98     10236343.72      3578097.66     10236361.08
      3578028.22     10236439.21      3577726.81      10236885.9
#Sta/Elev= 30
  4537.8  297.81  4608.9  295.67  4614.6  297.02  4624.7  297.46  4646.7  296.77
  4652.4  295.85    4659  296.27  4668.5  294.76    4693  294.54  4695.7  294.04
    4699  294.54  4807.5  296.01  4895.5  295.69  5001.9  294.62    5178  296.91
  5184.9  295.92  5199.8  296.55  5205.9  295.63  5271.8  295.53  5322.7  297.11
  5394.7  297.18  5472.7  298.46  5502.6  297.76  5508.6  298.56  5538.6  298.28
  5559.6  299.34  5574.5  298.54  5580.6   299.3  5610.5  299.14  5667.3  300.87
#Mann= 5 ,-1 , 0
  4537.8     .16       0    4693     .07       0    4699     .16       0
  4895.5     .12       0    5178     .05       0
Bank Sta=4693,4699
XS Rating Curve= 0 ,0
Exp/Cntr=0.3,0.1

Type RM Length L Ch R = 1 ,8985    ,28,28,28
BEGIN DESCRIPTION:
Mapping XS 740bc139
END DESCRIPTION:
XS GIS Cut Line= 6
      3578551.24     10236508.66       3578225.7     10236328.53
       3578160.6     10236322.02        3578102.     10236343.72
      3578045.58     10236384.96      3577703.81     10236878.17
#Sta/Elev= 30
  4511.2  297.78  4625.4  295.58  4648.4     297  4671.1  294.55  4792.2  298.48
  4808.8  297.07  4832.6  297.18    4838  298.39  4861.9   296.1  4867.3  297.63
  4898.9  296.32  4963.3  294.76  4988.3  295.58  4993.7  294.64  5046.8  296.55
  5061.3  296.33  5067.6  294.71  5073.8  295.75  5077.9  293.84  5080.6  293.34
  5083.9  293.84  5096.8  296.17  5102.6  294.92  5112.3  295.88  5118.1  294.58
  5133.6   296.1  5139.5  295.29  5169.6  296.64  5191.6   295.4    5682   301.4
#Mann= 5 ,-1 , 0
  4511.2     .16       0  4898.9     .12       0  5077.9     .07       0
  5083.9     .12       0  5191.6     .05       0
Bank Sta=5077.9,5083.9
XS Rating Curve= 0 ,0
Exp/Cntr=0.3,0.1

Type RM Length L Ch R = 1 ,8957    ,84,84,84
BEGIN DESCRIPTION:
Mapping XS e00e999b
END DESCRIPTION:
XS GIS Cut Line= 6
      3578559.93     10236493.48      3578269.11     10236313.34
      3578171.45     10236289.47      3578084.64     10236319.85
      3578004.35     10236380.61      3577672.36     10236866.66
#Sta/Elev= 30
    4483  297.84  4533.7  297.34  4554.9  295.67  4606.9  296.02  4621.6   297.4
  4643.6  295.22  4686.1  294.85  4722.7  295.69    4744  294.82  4759.4  295.43
  4765.2  294.68  4780.6  295.53  4786.5  294.67  4883.8  294.37  4899.8   293.5
  4922.7  292.69  4956.7  293.55  5081.2  292.55  5083.9  292.05  5087.2  292.55
  5128.4  292.75  5149.3  294.39  5164.3  294.32  5185.2  295.92  5200.2  295.06
  5224.8  295.99  5292.9  297.33  5358.7  297.08  5422.3  298.62  5706.9  302.21
#Mann= 5 ,-1 , 0
    4483     .16       0  4899.8     .12       0  5081.2     .07       0
  5087.2     .12       0  5224.8     .05       0
Bank Sta=5081.2,5087.2
XS Rating Curve= 0 ,0
Exp/Cntr=0.3,0.1

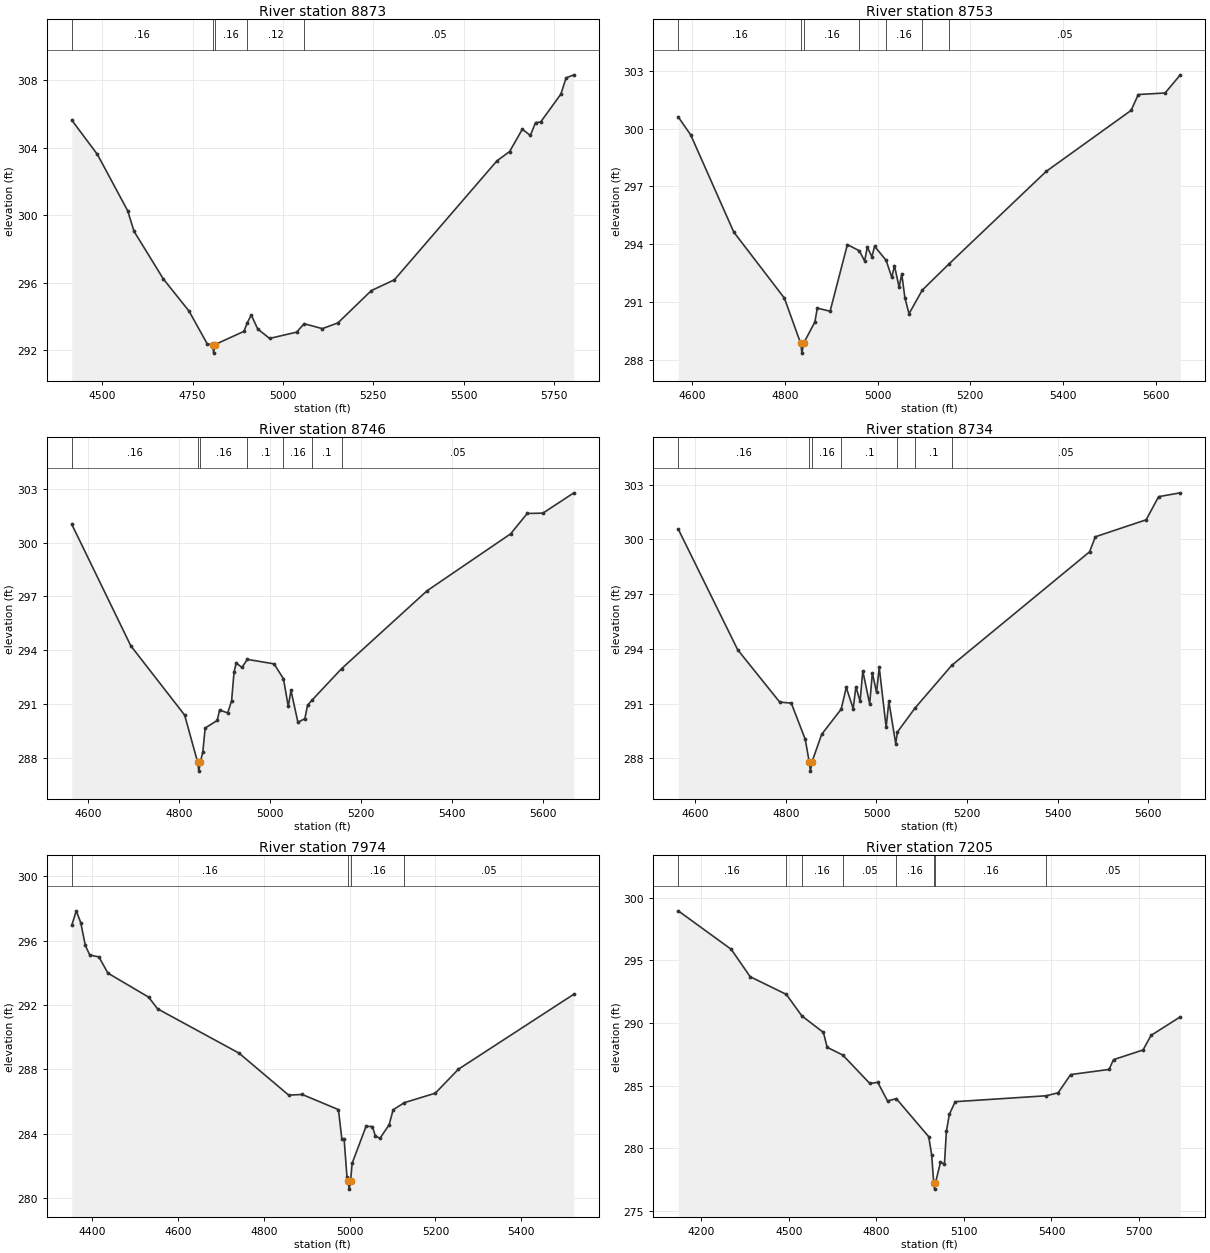
Type RM Length L Ch R = 1 ,8873    ,120,120,120
BEGIN DESCRIPTION:
UNT05307 IN WICK 15.0
END DESCRIPTION:
XS GIS Cut Line= 3
      3578642.09     10236141.64      3578042.11     10236241.64
      3577442.09     10236741.65
#Sta/Elev= 30
  4415.6  305.63  4486.5   303.6  4570.2  300.27  4587.9  299.05    4669  296.23
    4740  294.33  4790.7  292.38  4805.4  292.34  4808.2  291.84  4811.4  292.34
  4892.1  293.13  4901.5  293.65  4912.3   294.1  4930.1  293.27    4963  292.71
  5037.5  293.08  5058.7  293.58  5109.1  293.29  5152.1  293.63  5244.5  295.54
  5308.3  296.18  5592.1  303.22  5627.2  303.77  5662.3  305.09  5684.5  304.72
  5698.8  305.48  5713.1  305.52  5769.1  307.17  5783.4  308.13  5804.9  308.31
#Mann= 5 ,-1 , 0
  4415.6     .16       0  4805.4     .07       0  4811.4     .16       0
  4901.5     .12       0  5058.7     .05       0
Bank Sta=4805.4,4811.4
XS Rating Curve= 0 ,0
Exp/Cntr=0.3,0.1

Type RM Length L Ch R = 1 ,8753    ,7,7,7
BEGIN DESCRIPTION:
Mapping XS a2bbc56f
END DESCRIPTION:
XS GIS Cut Line= 4
      3578417.89     10235990.72      3578074.12      10236094.9
       3577936.1     10236175.63      3577455.69     10236471.66
#Sta/Elev= 30
  4569.7   300.6  4596.6  299.67  4689.5  294.64  4798.7  291.22    4834  288.87
  4836.7  288.37    4840  288.87  4864.5  289.98  4869.8   290.7  4897.4  290.54
  4934.7  293.99  4960.5  293.67  4971.9  293.14  4977.7  293.86  4987.6  293.36
  4993.4   293.9  5018.2  293.18  5030.6  292.29  5036.3   292.9  5046.3  291.78
    5052  292.47  5058.7  291.25  5067.7  290.41  5096.2  291.63  5153.6  292.98
  5363.7  297.78    5547  300.94  5562.4  301.76  5620.3  301.84  5653.1  302.78
#Mann= 7 ,-1 , 0
  4569.7     .16       0    4834     .07       0    4840     .16       0
  4960.5      .1       0  5018.2     .16       0  5096.2      .1       0
  5153.6     .05       0
Bank Sta=4834,4840
XS Rating Curve= 0 ,0
Exp/Cntr=0.3,0.1

Type RM Length L Ch R = 1 ,8746    ,12,12,12
BEGIN DESCRIPTION:
Mapping XS 076fd593
END DESCRIPTION:
XS GIS Cut Line= 5
      3578417.91     10235975.09      3578071.51     10236089.69
      3577988.18     10236136.56      3577917.87     10236180.84
      3577433.47      10236464.7
#Sta/Elev= 30
  4563.7  301.02  4693.5  294.26  4812.1   290.4  4840.7  287.78  4843.4  287.28
  4846.7  287.78  4852.1  288.35  4857.3  289.68  4883.8   290.1    4889  290.68
  4906.9  290.52  4915.5   291.2  4920.8  292.79  4925.6   293.3  4938.2  293.05
  4950.1   293.5  5008.9  293.25  5029.6  292.42  5040.2  290.88  5046.1  291.78
  5061.4     290  5076.7   290.2  5082.6  290.95  5092.8  291.24  5157.4  292.98
  5345.7  297.32  5529.7  300.49    5566  301.62  5600.7  301.64  5668.7  302.77
#Mann= 7 ,-1 , 0
  4563.7     .16       0  4840.7     .07       0  4846.7     .16       0
  4950.1      .1       0  5029.6     .16       0  5092.8      .1       0
  5157.4     .05       0
Bank Sta=4840.7,4846.7
XS Rating Curve= 0 ,0
Exp/Cntr=0.3,0.1

Type RM Length L Ch R = 1 ,8734    ,760,760,760
BEGIN DESCRIPTION:
Mapping XS 080f3b18
END DESCRIPTION:
XS GIS Cut Line= 4
      3578407.46     10235951.67      3578068.91     10236071.46
       3577938.7     10236154.79      3577417.89     10236441.24
#Sta/Elev= 30
  4562.5  300.57  4693.7  293.95  4786.4  291.08    4812  291.02  4842.9  289.03
  4851.6  287.79  4854.3  287.29  4857.6  287.79  4879.1  289.31  4922.1  290.69
  4933.4  291.88  4948.6  290.72  4954.6  291.92  4963.9  291.12  4969.8  292.79
    4985  290.97  4990.9  292.67  5000.2  291.62  5006.1  292.98  5021.4  289.69
  5027.3  291.12  5042.5   288.8  5046.3  289.44  5085.4  290.76    5166  293.09
  5470.2  299.32  5483.2  300.15  5595.2  301.08  5622.7  302.35  5670.6  302.56
#Mann= 7 ,-1 , 0
  4562.5     .16       0  4851.6     .07       0  4857.6     .16       0
  4922.1      .1       0  5046.3     .16       0  5085.4      .1       0
    5166     .05       0
Bank Sta=4851.6,4857.6
XS Rating Curve= 0 ,0
Exp/Cntr=0.3,0.1

Type RM Length L Ch R = 1 ,7974    ,769,769,769
BEGIN DESCRIPTION:
UNT05307 IN WICK 13.0
END DESCRIPTION:
XS GIS Cut Line= 3
      3578492.06     10235641.63      3577892.11     10235441.64
      3577392.13     10235641.63
#Sta/Elev= 30
  4351.9  296.95  4362.4  297.85  4372.9  297.11  4383.5   295.7    4394   295.1
  4415.1  294.99  4436.2  293.98    4531  292.49  4552.1  291.76  4741.9  289.01
  4857.8   286.4  4889.4  286.44  4973.8   285.5  4981.7  283.69    4987  283.69
  4993.7  281.32  4996.1  281.06  4998.9  280.56  5002.1  281.06  5005.8  282.17
  5038.2  284.46    5053  284.45  5059.7  283.88  5070.5  283.71    5092  284.56
  5101.4  285.49  5127.3  285.93  5199.7  286.52  5253.6  288.01  5522.8  292.67
#Mann= 4 ,-1 , 0
  4351.9     .16       0  4996.1     .07       0  5002.1     .16       0
  5127.3     .05       0
Bank Sta=4996.1,5002.1
XS Rating Curve= 0 ,0
Exp/Cntr=0.3,0.1

Type RM Length L Ch R = 1 ,7205    ,460,460,460
BEGIN DESCRIPTION:
UNT05307 IN WICK 12.0
END DESCRIPTION:
XS GIS Cut Line= 4
      3578734.61     10235273.31      3578300.57     10234956.46
      3577558.38     10234856.63       3577186.1     10235081.74
#Sta/Elev= 30
  4120.4  298.94  4302.2  295.87    4367  293.69    4491  292.28  4544.4  290.56
  4618.1  289.25  4631.1  288.06  4684.3  287.45  4777.3  285.18  4804.5  285.27
  4837.9  283.79  4868.1  283.97  4979.1  280.94  4989.2   279.5  4996.3  277.26
    4999  276.76  5002.3  277.26  5019.5   278.9  5033.1  278.77  5039.7  281.36
  5049.7  282.71  5069.9  283.73  5381.8   284.2  5422.9  284.44  5465.6  285.89
  5597.5   286.3  5612.7  287.08  5713.9  287.85  5741.2  289.01  5841.7  290.49
#Mann= 8 ,-1 , 0
  4120.4     .16       0    4491      .1       0  4544.4     .16       0
  4684.3     .05       0  4868.1     .16       0  4996.3     .07       0
  5002.3     .16       0  5381.8     .05       0
Bank Sta=4996.3,5002.3
XS Rating Curve= 0 ,0
Exp/Cntr=0.3,0.1

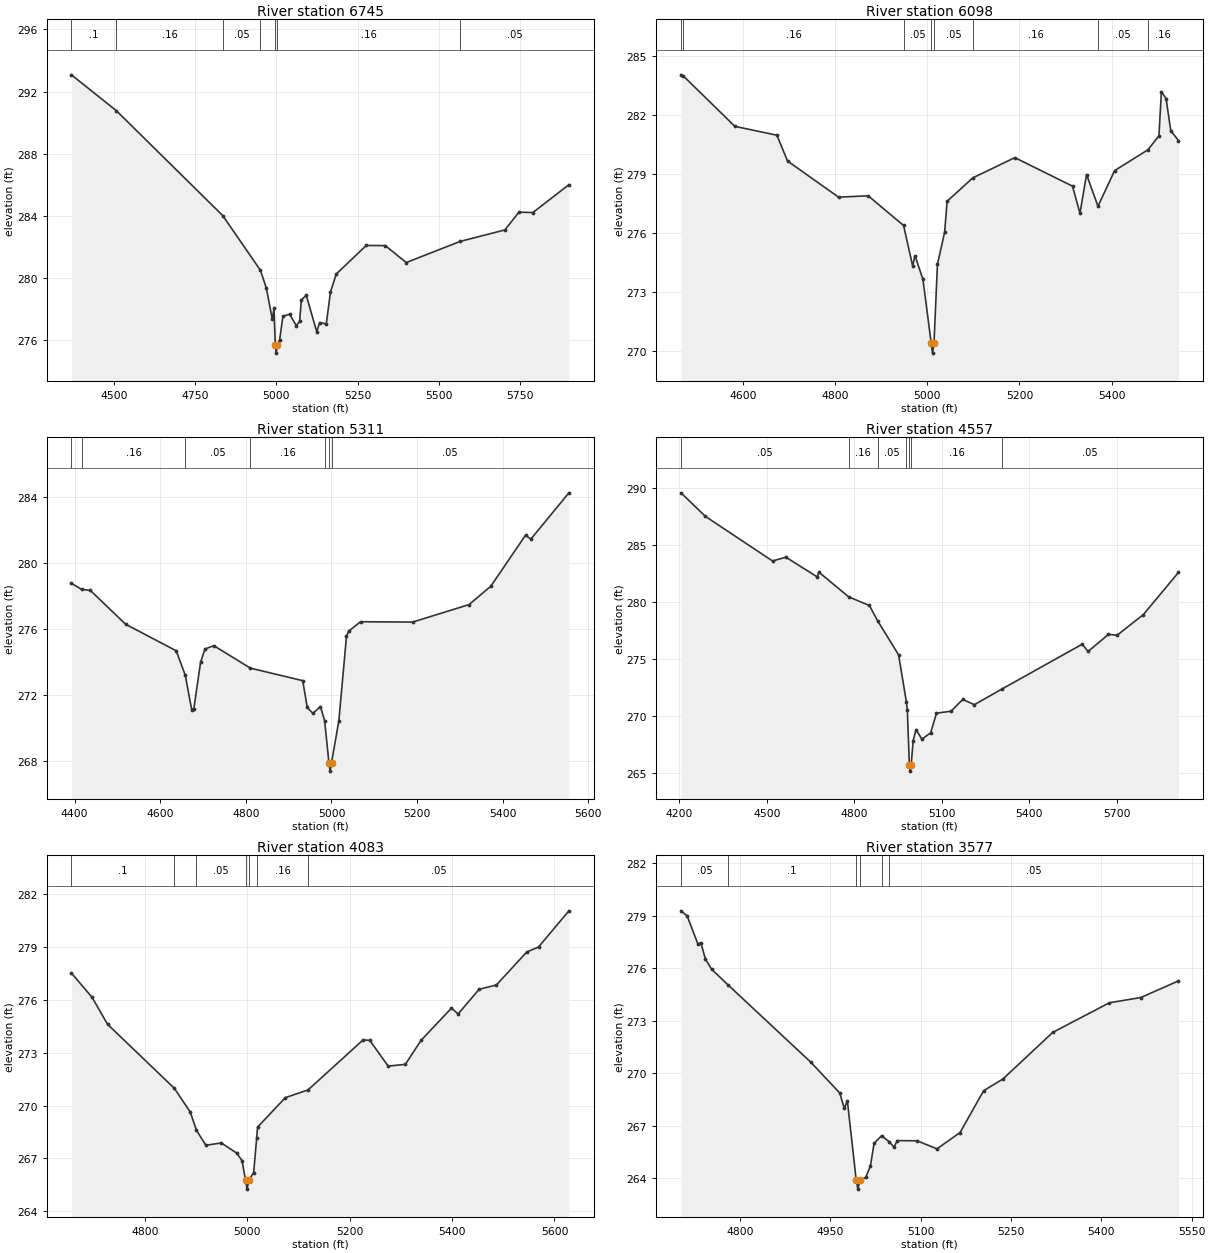
Type RM Length L Ch R = 1 ,6745    ,647,647,647
BEGIN DESCRIPTION:
UNT05307 IN WICK 11.0
END DESCRIPTION:
XS GIS Cut Line= 3
      3578686.88     10234670.01       3577549.7     10234400.91
      3577232.88     10234583.19
#Sta/Elev= 30
  4367.8  293.08  4506.5  290.77  4834.5  284.02  4950.7   280.5  4968.7  279.37
  4987.3  277.35  4992.4  278.05  4996.6  275.67  4999.3  275.17  5002.6  275.67
  5009.8  276.02  5020.1  277.54  5040.7  277.67  5061.2  276.94  5071.5  277.22
  5076.9   278.6    5092  278.89  5124.3  276.54  5133.1  277.13  5153.7  277.05
  5166.6   279.1  5184.5  280.26    5277   282.1  5335.6  282.09  5400.3     281
  5566.7  282.36  5704.6   283.1  5747.7  284.24  5790.9  284.22  5901.9  286.01
#Mann= 7 ,-1 , 0
  4367.8      .1       0  4506.5     .16       0  4834.5     .05       0
  4950.7     .16       0  4996.6     .07       0  5002.6     .16       0
  5566.7     .05       0
Bank Sta=4996.6,5002.6
XS Rating Curve= 0 ,0
Exp/Cntr=0.3,0.1

Type RM Length L Ch R = 1 ,6098    ,787,787,787
BEGIN DESCRIPTION:
Mapping XS 79a97156
END DESCRIPTION:
XS GIS Cut Line= 3
      3578482.32     10234251.07      3577695.88     10233999.35
      3577445.62     10234044.22
#Sta/Elev= 30
  4465.3  284.05    4470     284  4582.3  281.43  4673.5  280.98  4696.5  279.67
  4807.3  277.83  4871.6   277.9  4948.5  276.39  4968.1  274.34  4973.3  274.85
  4990.5  273.65  5008.5   270.4  5011.3   269.9  5014.5   270.4    5022  274.41
  5037.6  276.05    5043  277.62  5098.7  278.81    5190  279.84  5315.2  278.39
  5331.4  277.01  5345.7  278.98  5370.5  277.37  5406.6  279.18    5479  280.24
  5502.8  280.95  5508.2  283.19  5518.4  282.84  5528.5  281.21  5545.3  280.71
#Mann= 8 ,-1 , 0
  4465.3     .05       0    4470     .16       0  4948.5     .05       0
  5008.5     .04       0  5014.5     .05       0  5098.7     .16       0
  5370.5     .05       0    5479     .16       0
Bank Sta=5008.5,5014.5
XS Rating Curve= 0 ,0
Exp/Cntr=0.3,0.1

Type RM Length L Ch R = 1 ,5311    ,754,754,754
BEGIN DESCRIPTION:
UNT05307 IN WICK 9.0
END DESCRIPTION:
XS GIS Cut Line= 4
      3578594.93     10233795.81      3578255.01       10233711.
      3578142.11     10233541.64      3577542.06     10233441.63
#Sta/Elev= 30
  4392.5  278.76  4416.1  278.39  4436.6  278.33  4519.1  276.28  4637.3  274.67
  4658.6  273.18  4673.4  271.11  4678.5  271.17  4694.3  273.98  4704.6  274.78
  4725.2  274.98  4810.5  273.62  4932.9  272.86  4943.4  271.24  4956.5  270.88
  4974.3  271.29  4984.1  270.43  4994.1  267.88  4996.8  267.38  5000.1  267.88
  5017.3  270.44  5035.1  275.55  5040.2  275.86    5068  276.43  5189.7  276.41
  5321.5  277.47  5372.2  278.58  5453.3  281.67  5465.9  281.44  5554.7  284.24
#Mann= 7 ,-1 , 0
  4392.5      .1       0  4416.1     .16       0  4658.6     .05       0
  4810.5     .16       0  4984.1     .05       0  4994.1     .03       0
  5000.1     .05       0
Bank Sta=4994.1,5000.1
XS Rating Curve= 0 ,0
Exp/Cntr=0.3,0.1

Type RM Length L Ch R = 1 ,4557    ,474,474,474
BEGIN DESCRIPTION:
UNT05307 IN WICK 8.0
END DESCRIPTION:
XS GIS Cut Line= 3
      3579264.14      10233558.9       3578734.6     10233337.54
      3577601.82     10233350.56
#Sta/Elev= 30
  4205.7  289.54  4289.3  287.48  4519.7  283.57  4565.6   283.9  4673.4  282.17
  4678.8  282.59  4781.4  280.42  4852.1  279.67  4880.2  278.33  4952.2  275.35
    4979  271.21  4982.2  270.53  4989.2  265.66  4991.9  265.16  4995.2  265.66
  5002.2  267.84  5012.2   268.8  5032.2  267.96  5062.2  268.52  5082.2  270.24
  5132.2  270.41  5172.2  271.44  5212.2  270.98  5305.9  272.34  5582.2  276.28
  5602.2  275.64  5672.2  277.14  5702.2  277.07  5792.2  278.88  5912.5  282.57
#Mann= 7 ,-1 , 0
  4205.7     .05       0  4781.4     .16       0  4880.2     .05       0
    4979     .16       0  4989.2     .07       0  4995.2     .16       0
  5305.9     .05       0
Bank Sta=4989.2,4995.2
XS Rating Curve= 0 ,0
Exp/Cntr=0.3,0.1

Type RM Length L Ch R = 1 ,4083    ,506,506,506
BEGIN DESCRIPTION:
UNT05307 IN WICK 7.0
END DESCRIPTION:
XS GIS Cut Line= 3
      3578592.06     10232991.65      3578242.11     10233041.64
      3577642.08     10233191.65
#Sta/Elev= 30
  4656.2  277.52  4696.6  276.14  4726.9  274.61  4857.3  270.98  4888.5  269.63
  4900.5   268.6  4918.8  267.75  4949.1  267.88  4979.4   267.3  4989.5  266.87
  4996.6  265.76  4999.4  265.26  5002.6  265.76  5012.3   266.2  5018.2  268.18
    5020  268.78  5074.1  270.45  5118.6  270.89  5226.2  273.73  5239.1   273.7
  5275.1  272.24  5308.6  272.34  5339.6  273.71  5398.8  275.53  5411.7   275.2
  5452.9   276.6  5486.4  276.84  5545.7  278.71  5568.9     279  5628.2  281.05
#Mann= 7 ,-1 , 0
  4656.2      .1       0  4857.3     .16       0  4900.5     .05       0
  4996.6     .03       0  5002.6     .05       0  5018.2     .16       0
  5118.6     .05       0
Bank Sta=4996.6,5002.6
XS Rating Curve= 0 ,0
Exp/Cntr=0.3,0.1

Type RM Length L Ch R = 1 ,3577    ,288,288,288
BEGIN DESCRIPTION:
UNT05307 IN WICK 6.0
END DESCRIPTION:
XS GIS Cut Line= 3
      3578592.15     10232741.65      3578292.11     10232691.64
      3577792.11     10232841.64
#Sta/Elev= 30
    4702  279.27  4712.2  278.98  4729.9  277.39    4735  277.44  4742.6  276.51
  4752.7  275.94  4779.8  275.05  4917.5  270.63  4965.6  268.87  4973.2  267.99
  4978.3  268.42    4993  263.88  4995.8  263.38    4999  263.88  5008.8  264.05
  5016.6  264.71  5022.7     266  5035.2  266.43  5048.2  266.07  5055.8  265.78
    5061  266.15  5094.1  266.14  5127.1  265.68  5165.4  266.61  5204.6     269
  5236.7  269.67  5319.4  272.33  5413.4  274.02  5465.6  274.32  5528.2  275.27
#Mann= 6 ,-1 , 0
    4702     .05       0  4779.8      .1       0    4993     .07       0
    4999      .1       0  5035.2     .12       0  5048.2     .05       0
Bank Sta=4993,4999
XS Rating Curve= 0 ,0
Exp/Cntr=0.3,0.1

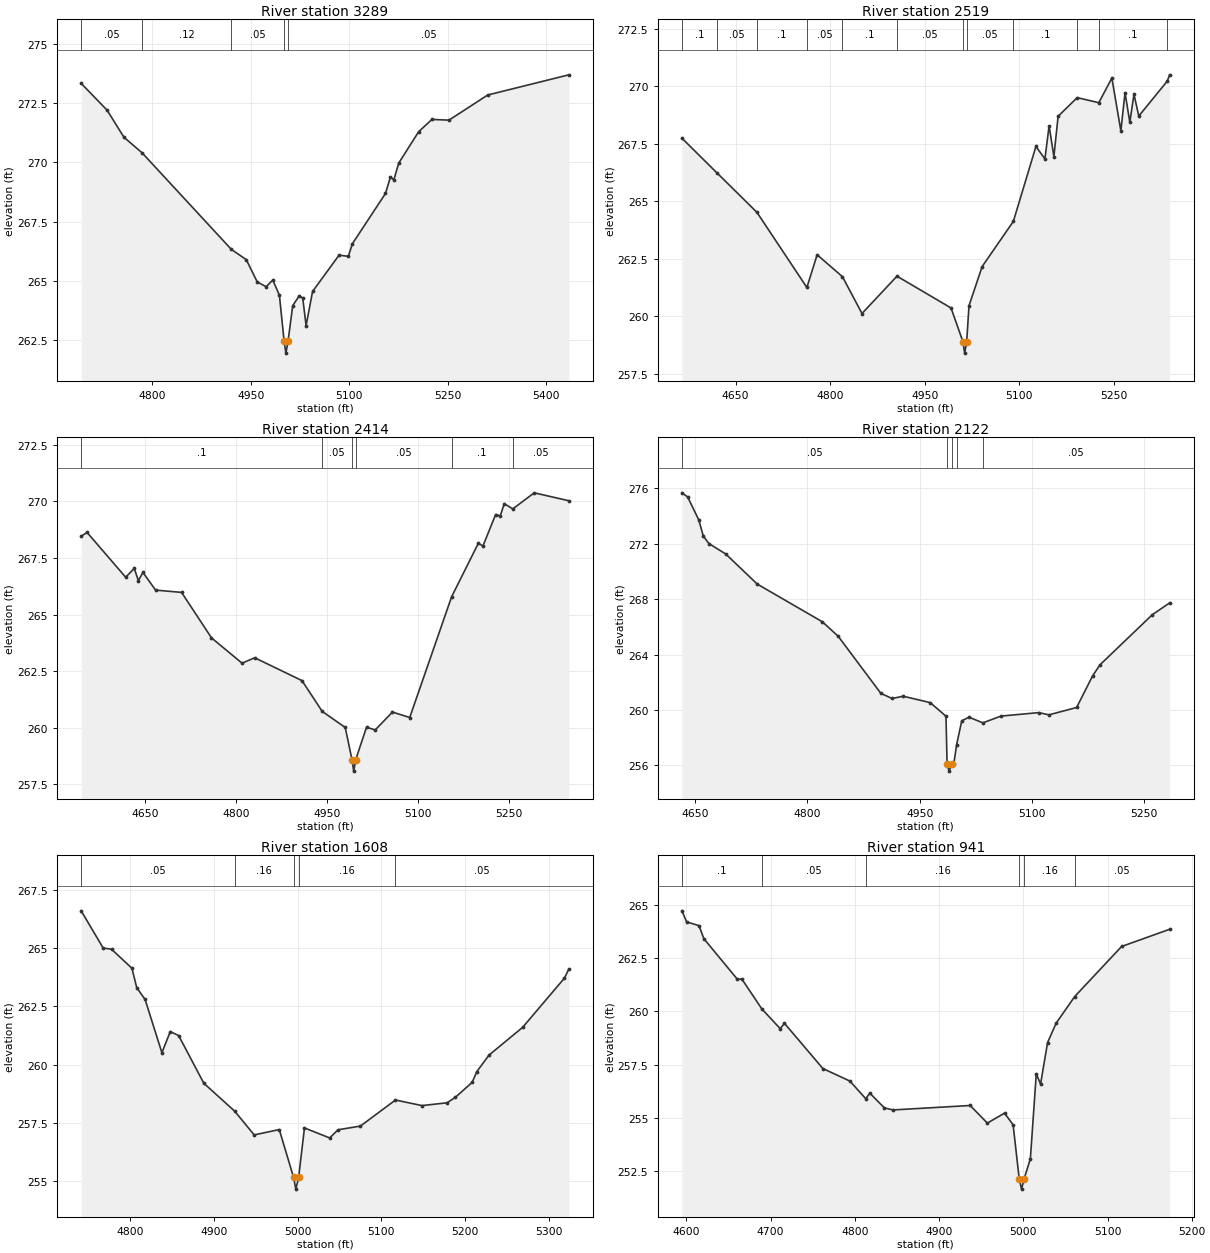
Type RM Length L Ch R = 1 ,3289    ,770,770,770
BEGIN DESCRIPTION:
UNT05307 IN WICK 5.0
END DESCRIPTION:
XS GIS Cut Line= 3
      3578461.18     10232556.29      3577905.61     10232473.82
      3577792.95     10232616.82
#Sta/Elev= 30
  4691.3  273.33  4730.8   272.2  4756.5  271.06  4784.3   270.4  4920.4  266.33
  4943.1   265.9  4959.8  264.96  4973.4  264.76  4983.5  265.04  4993.6   264.4
  5000.8  262.46  5003.5  261.96  5006.8  262.46  5013.9  263.96    5024  264.38
  5029.2  264.28  5034.3  263.12  5044.2  264.56  5084.6  266.09  5098.7  266.04
  5104.9  266.57  5155.4  268.69    5163  269.39  5168.1  269.26  5175.6  269.97
  5205.9  271.29  5226.2  271.81  5252.2  271.78  5311.3  272.84    5435  273.69
#Mann= 5 ,-1 , 0
  4691.3     .05       0  4784.3     .12       0  4920.4     .05       0
  5000.8     .03       0  5006.8     .05       0
Bank Sta=5000.8,5006.8
XS Rating Curve= 0 ,0
Exp/Cntr=0.3,0.1

Type RM Length L Ch R = 1 ,2519    ,105,105,105
BEGIN DESCRIPTION:
Mapping XS 7288126c
END DESCRIPTION:
XS GIS Cut Line= 2
      3578317.91     10232308.87      3577806.46     10231728.06
#Sta/Elev= 30
  4564.7  267.74  4620.1  266.24  4683.8  264.52    4763  261.26  4779.3  262.68
  4819.4  261.73  4850.5  260.13    4906  261.75  4991.8  260.37  5010.6  258.91
  5013.4  258.41  5016.6  258.91  5020.3  260.47  5041.2  262.17  5090.7  264.13
  5126.5  267.38  5140.8  266.84  5147.4  268.28    5155  266.94  5161.7  268.69
    5192   269.5  5226.3  269.28    5247  270.35  5261.3  268.06  5267.9  269.72
  5275.5  268.43  5282.1  269.65  5289.7   268.7    5335  270.22  5338.6  270.49
#Mann= 12 ,-1 , 0
  4564.7      .1       0  4620.1     .05       0  4683.8      .1       0
    4763     .05       0  4819.4      .1       0    4906     .05       0
  5010.6     .03       0  5016.6     .05       0  5090.7      .1       0
    5192     .05       0  5226.3      .1       0    5335     .05       0
Bank Sta=5010.6,5016.6
XS Rating Curve= 0 ,0
Exp/Cntr=0.3,0.1

Type RM Length L Ch R = 1 ,2414    ,292,292,292
BEGIN DESCRIPTION:
Mapping XS 4c25cb87
END DESCRIPTION:
XS GIS Cut Line= 2
      3578404.74     10232252.47      3577876.92     10231646.78
#Sta/Elev= 30
  4545.3  268.46    4555  268.63  4618.6  266.65  4632.8  267.04  4639.5   266.5
  4647.1  266.86  4667.9  266.08  4710.7  265.98    4760  263.97  4810.4  262.85
  4831.2  263.09  4909.1  262.08  4942.4  260.72  4980.3  260.01  4991.5  258.58
  4994.3  258.08  4997.5  258.58  5015.4  260.02  5029.7   259.9  5058.1  260.69
  5086.6  260.45  5155.5  265.78  5199.6  268.15  5207.2  268.03  5228.1  269.42
  5235.7  269.36  5242.3   269.9  5256.4  269.67  5291.7  270.38  5348.7  270.03
#Mann= 6 ,-1 , 0
  4545.3      .1       0  4942.4     .05       0  4991.5     .03       0
  4997.5     .05       0  5155.5      .1       0  5256.4     .05       0
Bank Sta=4991.5,4997.5
XS Rating Curve= 0 ,0
Exp/Cntr=0.3,0.1

Type RM Length L Ch R = 1 ,2122    ,514,514,514
BEGIN DESCRIPTION:
UNT05307 IN WICK 3.0
END DESCRIPTION:
XS GIS Cut Line= 3
      3578642.14     10231941.67      3578342.11     10231741.64
      3578092.15     10231591.67
#Sta/Elev= 30
  4632.1  275.66  4639.7  275.37  4654.7   273.7  4660.7  272.54  4668.2     272
  4690.7  271.25  4732.8  269.08  4819.9  266.36    4841  265.32  4898.1   261.2
  4913.1  260.83  4928.1  260.99  4964.2  260.53  4985.2  259.55  4986.7  256.09
  4989.4  255.59  4992.7  256.09  4995.6  256.09  4999.5  257.51  5006.3  259.22
    5016  259.48  5034.5  259.07  5058.8  259.56  5109.3  259.81  5122.9  259.65
  5159.9  260.18  5181.2  262.45    5191  263.25  5260.9  266.86  5284.2  267.72
#Mann= 5 ,-1 , 0
  4632.1     .05       0  4986.7     .07       0  4992.7     .05       0
  4999.5     .16       0  5034.5     .05       0
Bank Sta=4986.7,4992.7
XS Rating Curve= 0 ,0
Exp/Cntr=0.3,0.1

Type RM Length L Ch R = 1 ,1608    ,667,667,667
BEGIN DESCRIPTION:
Mapping XS 2aca96fa
END DESCRIPTION:
XS GIS Cut Line= 2
      3578838.32     10231560.99      3578256.95     10231518.69
#Sta/Elev= 30
  4741.3  266.61  4767.6  265.01  4777.6  264.96    4802  264.14  4807.7  263.31
  4817.7   262.8  4837.8  260.51  4847.8  261.42  4857.8  261.25  4887.9   259.2
  4924.8     258  4948.1  256.98  4978.1  257.21  4995.2  255.15  4997.9  254.65
  5001.2  255.15  5008.2  257.28  5038.3  256.85  5048.3   257.2  5075.1  257.36
    5117  258.48  5148.6  258.24  5178.7  258.36  5188.7   258.6  5208.7  259.24
  5214.2   259.7  5228.8  260.41  5268.9   261.6    5319  263.72  5324.2  264.11
#Mann= 5 ,-1 , 0
  4741.3     .05       0  4924.8     .16       0  4995.2     .07       0
  5001.2     .16       0    5117     .05       0
Bank Sta=4995.2,5001.2
XS Rating Curve= 0 ,0
Exp/Cntr=0.3,0.1

Type RM Length L Ch R = 1 ,941     ,586,586,586
BEGIN DESCRIPTION:
Mapping XS 3fb09cba
END DESCRIPTION:
XS GIS Cut Line= 2
      3578917.61     10231212.68      3578350.05     10231327.71
#Sta/Elev= 30
  4594.6  264.74  4600.2  264.22    4615  264.04  4620.6  263.43  4660.6  261.51
  4665.7  261.53  4689.5  260.12  4711.3  259.19  4716.4  259.44    4762  257.31
  4794.1  256.72  4812.9  255.89  4817.8  256.15  4834.9  255.46  4845.1  255.36
  4936.9  255.57  4957.3  254.74  4977.7  255.21  4987.9  254.66  4995.1  252.13
  4997.9  251.63  5001.1  252.13  5008.4  253.06  5015.4  257.06  5020.5  256.58
  5028.8  258.53    5039  259.45    5061   260.7  5116.7  263.06  5173.7  263.87
#Mann= 6 ,-1 , 0
  4594.6      .1       0  4689.5     .05       0  4812.9     .16       0
  4995.1     .07       0  5001.1     .16       0    5061     .05       0
Bank Sta=4995.1,5001.1
XS Rating Curve= 0 ,0
Exp/Cntr=0.3,0.1

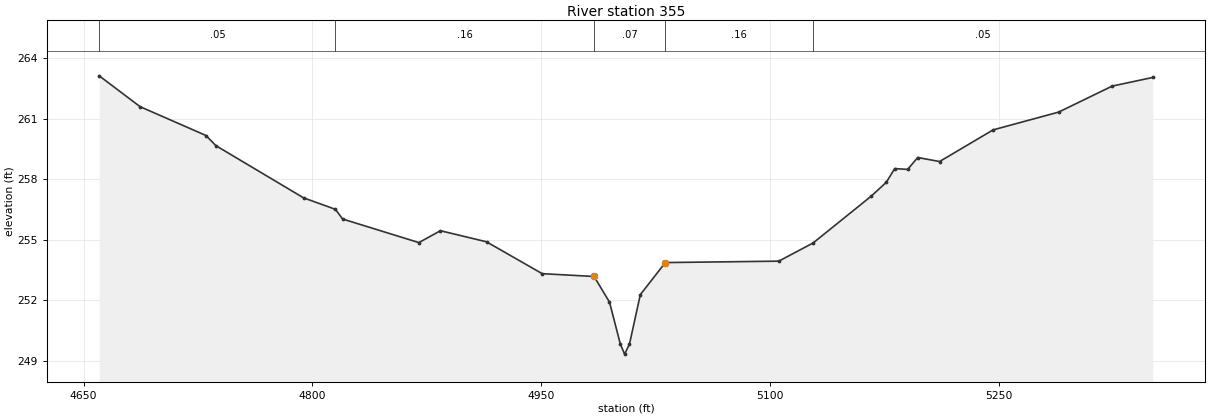
Type RM Length L Ch R = 1 ,355     ,0,0,0
BEGIN DESCRIPTION:
UNT05307 IN WICK 1.0
END DESCRIPTION:
XS GIS Cut Line= 4
      3578949.06     10231122.65      3578823.17     10231020.63
      3578466.18     10231065.12       3578357.7     10231194.21
#Sta/Elev= 30
  4660.3  263.14  4687.1  261.61  4730.3  260.18  4736.7  259.68  4794.2  257.09
  4815.1  256.52  4819.8  256.04  4869.8  254.87  4883.9  255.46  4914.1  254.91
  4950.6  253.33  4984.6  253.19  4994.7  251.92  5001.8  249.84  5004.6  249.34
  5007.8  249.84  5014.9  252.29  5031.3  253.88  5105.6  253.95  5128.1  254.85
    5166  257.16  5176.1  257.86  5181.6  258.54  5190.1   258.5  5196.7  259.09
    5211  258.89  5246.1  260.46    5289  261.34  5324.1  262.63  5350.7  263.06
#Mann= 5 ,-1 , 0
  4660.3     .05       0  4815.1     .16       0  4984.6     .07       0
  5031.3     .16       0  5128.1     .05       0
Bank Sta=4984.6,5031.3
XS Rating Curve= 0 ,0
Exp/Cntr=0.3,0.1

Chan Stop Cuts=-1
Use User Specified Reach Order=0
Composite Channel Slope=5