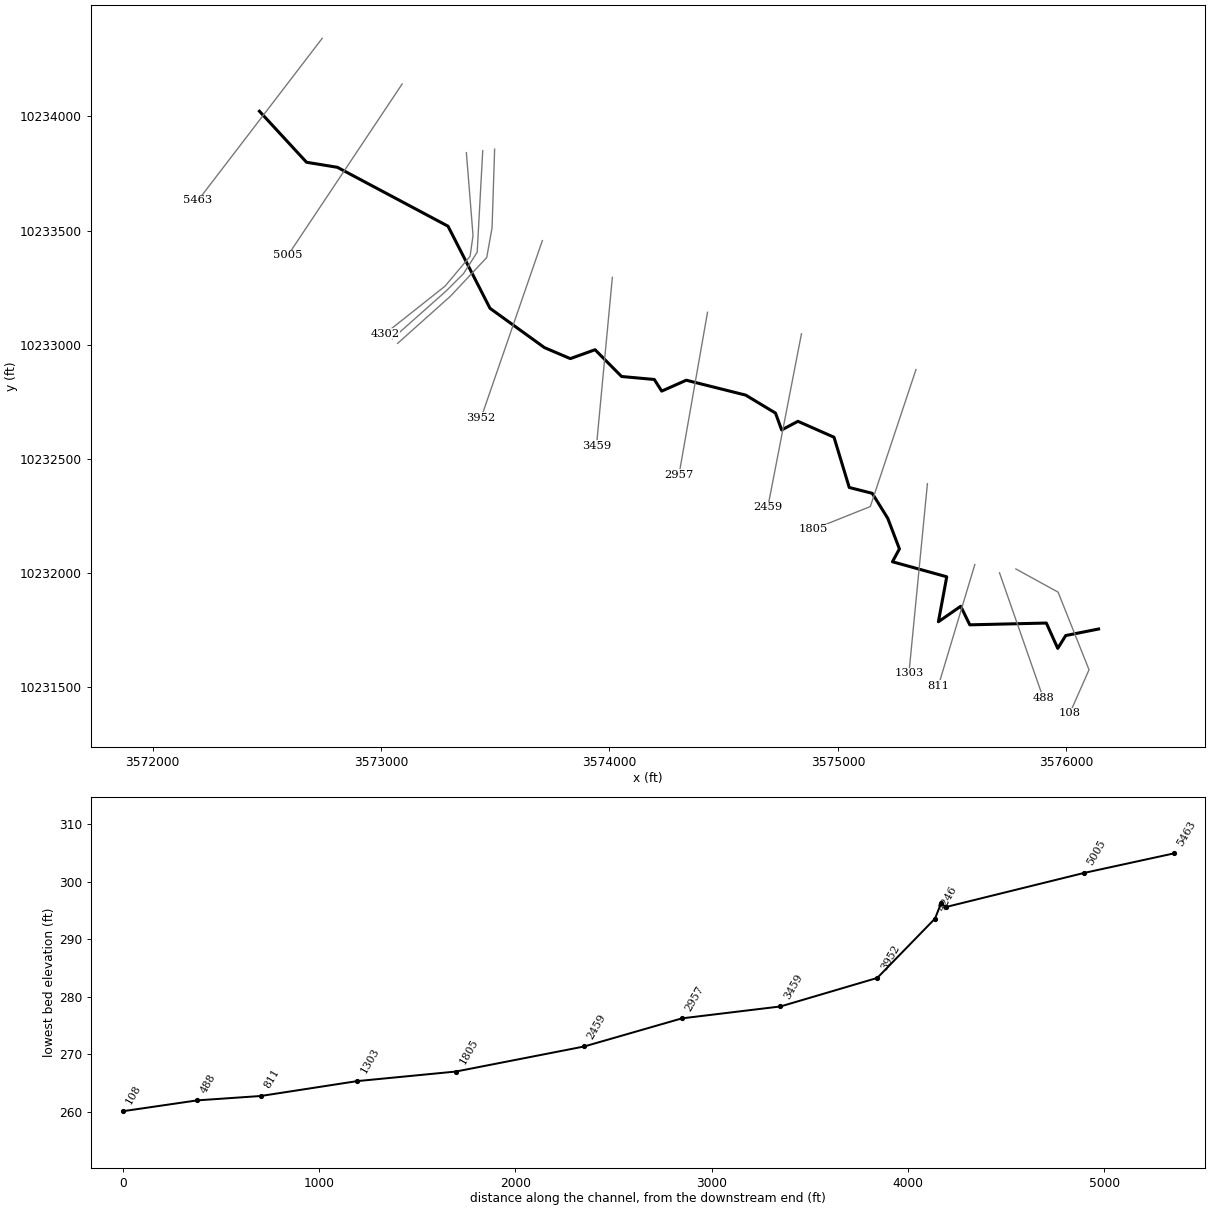
--- BRUSHYCREEKTRIB1.prj (project) ---

Proj Title=BRUSHY CREEK TRIB 10 3
Current Plan=p01
Default Exp/Contr=0.3,0.1
English Units
Geom File=g01
Flow File=f01
Plan File=p01
Y Axis Title=Elevation
X Axis Title(PF)=Main Channel Distance
X Axis Title(XS)=Station
BEGIN DESCRIPTION:
UNT05306 IN WICK
END DESCRIPTION:
DSS Export Rating Curves= 0
DSS Export Rating Curve Sorted= 0
DSS Export Volume Flow Curves= 0
DXF OffsetX= 0
DXF OffsetY= 0
DXF ScaleX= 1
DXF ScaleY= 10

--- BRUSHYCREEKTRIB1.p01 (plan) ---

Plan Title=Multiple Run
Short Identifier=Multiple
Geom File=g01
Flow File=f01
Subcritical Flow
K Sum by GR= 0
Std Step Tol= 0.01
Critical Tol= 0.01
Num of Std Step Trials= 20
Max Error Tol= 0.3
Flow Tol Ratio= 0.001
Split Flow NTrial= 30
Split Flow Tol= 0.02
Split Flow Ratio= 0.02
Log Output Level= 0
Friction Slope Method= 1
Unsteady Friction Slope Method= 2
Unsteady Bridges Friction Slope Method= 1
Parabolic Critical Depth
Global Vel Dist=  1 , 1 , 1
Global Log Level= 0
CheckData=True
Encroach Param= -1, 0, 0, 0
BEGIN DESCRIPTION:
Multiple Run
END DESCRIPTION:

--- BRUSHYCREEKTRIB1.f01 (steady flow) ---

Flow Title=Multiple
Program Version=4.10
Number of Profiles= 7
Profile Names=10-year,25-year,50-year,1pct_min,100-year,1pct_plu,500-year
River Rch & RM=UNT05306 IN WICK,Reach-1         ,5463
     236     301     352     302     409     553     552
River Rch & RM=UNT05306 IN WICK,Reach-1         ,108
     607     815     983     868    1174    1587    1679
River Rch & RM=BRUSHYCRTR103,Reach-1         ,5463
     236     301     352     302     409     553     552
River Rch & RM=BRUSHYCRTR103,Reach-1         ,108
     607     815     983     868    1174    1587    1679
Boundary for River Rch & Prof#=BRUSHYCRTR103,Reach-1         , 1
Up Type= 0
Dn Type= 3
Dn Slope=0.005
Boundary for River Rch & Prof#=BRUSHYCRTR103,Reach-1         , 2
Up Type= 0
Dn Type= 3
Dn Slope=0.005
Boundary for River Rch & Prof#=BRUSHYCRTR103,Reach-1         , 3
Up Type= 0
Dn Type= 3
Dn Slope=0.005
Boundary for River Rch & Prof#=BRUSHYCRTR103,Reach-1         , 4
Up Type= 0
Dn Type= 3
Dn Slope=0.005
Boundary for River Rch & Prof#=BRUSHYCRTR103,Reach-1         , 5
Up Type= 0
Dn Type= 3
Dn Slope=0.005
Boundary for River Rch & Prof#=BRUSHYCRTR103,Reach-1         , 6
Up Type= 0
Dn Type= 3
Dn Slope=0.005
Boundary for River Rch & Prof#=BRUSHYCRTR103,Reach-1         , 7
Up Type= 0
Dn Type= 3
Dn Slope=0.005
DSS Import GetInterval= 0
DSS Import GetPeak= 0
DSS Import FillOption= 0

--- BRUSHYCREEKTRIB1.g01 (geometry) ---

Geom Title=Existing Conditions
Program Version=4.10

River Reach=BRUSHYCRTR103   ,Reach-1
Reach XY= 30
      3572467.33     10234022.58       3572673.5     10233799.05
      3572808.64     10233776.99      3573293.02     10233519.18
      3573476.85     10233159.59      3573715.33      10232987.5
      3573828.61     10232939.32      3573936.89     10232978.21
        3574053.     10232861.02      3574196.23       10232848.
      3574228.78       10232797.       3574336.2     10232844.75
      3574596.46     10232779.55      3574726.97     10232700.81
      3574753.83     10232626.95      3574825.12     10232664.83
       3574983.1     10232595.14      3575049.85     10232375.08
      3575150.51     10232349.53       3575218.5     10232239.97
      3575269.54      10232106.1      3575238.94     10232049.91
      3575476.74     10231984.06      3575440.19     10231787.23
        3575538.     10231855.01      3575577.58      10231773.7
      3575912.79     10231781.53      3575962.79     10231670.59
      3575997.68     10231726.84      3576141.52     10231755.44

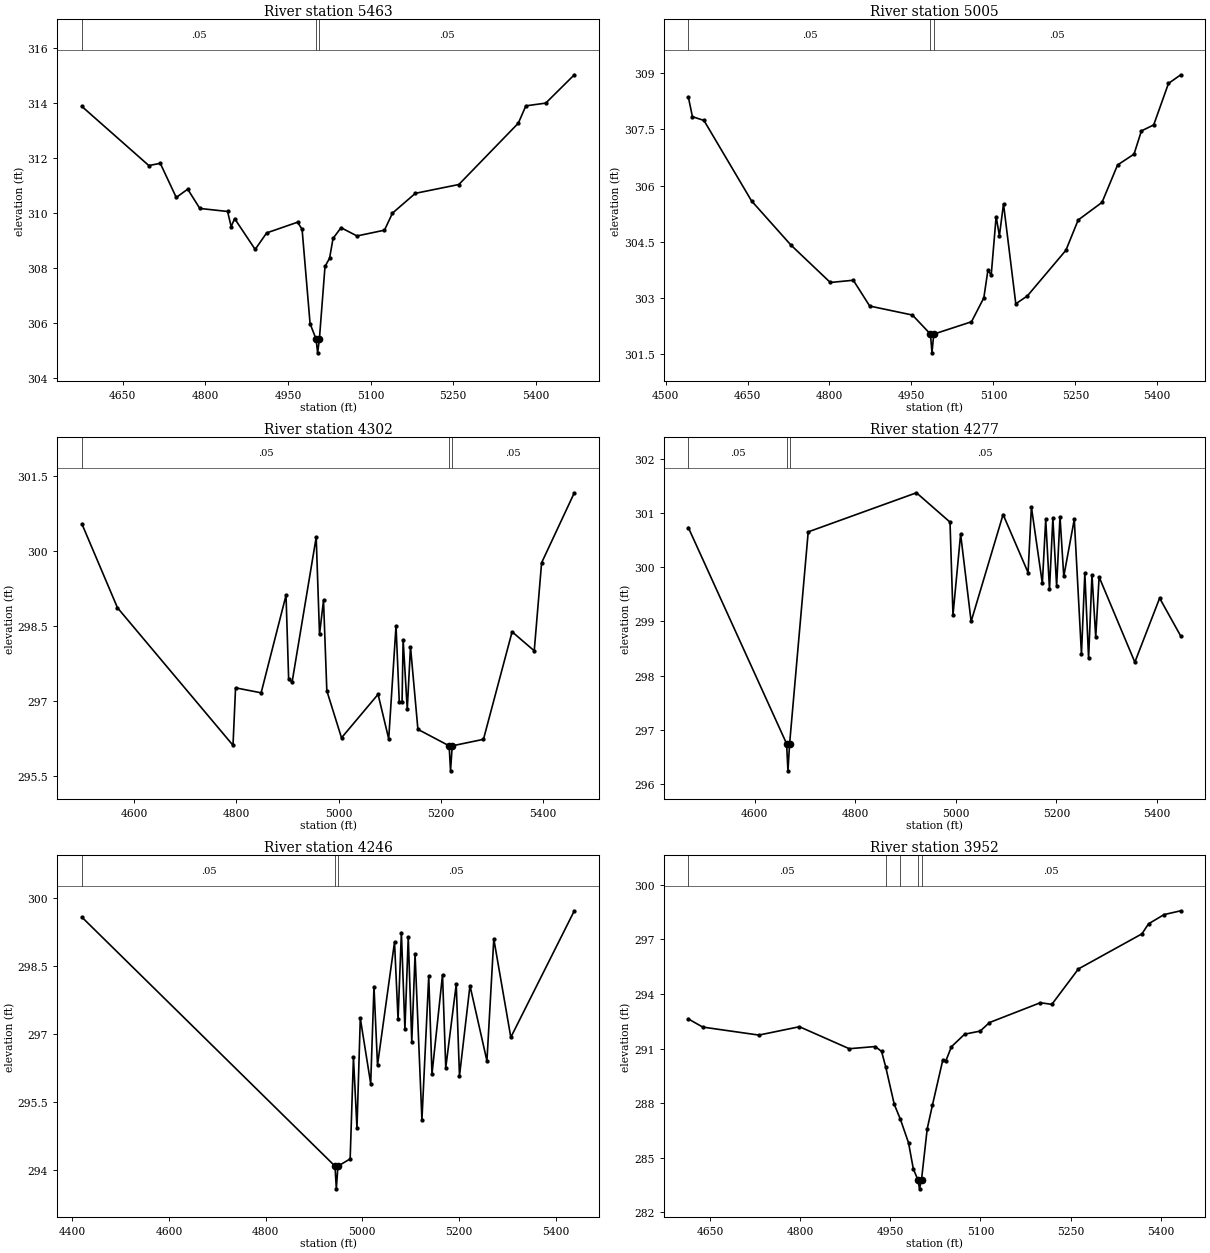
Type RM Length L Ch R = 1 ,5463    ,458,458,458
BEGIN DESCRIPTION:
UNT05306 IN WICK 10.0
END DESCRIPTION:
XS GIS Cut Line= 2
      3572742.14     10234341.68      3572198.38     10233631.81
#Sta/Elev= 30
  4575.8  313.89  4697.4  311.74  4718.2  311.82  4747.2  310.58    4768  310.88
    4790  310.18  4840.4  310.07  4846.9  309.52  4853.2  309.81  4890.5  308.69
  4911.3  309.29  4967.5  309.68  4975.7  309.42  4990.2  305.99  5001.1  305.43
  5003.9  304.93  5007.1  305.43  5017.3  308.07  5025.6  308.37  5031.9  309.09
  5046.4  309.48  5075.4  309.18  5125.3  309.39  5139.8  310.01  5181.4  310.73
  5260.3  311.05  5368.3  313.28    5382  313.91  5418.1  314.01    5470  315.04
#Mann= 3 ,-1 , 0
  4575.8     .05       0  5001.1     .03       0  5007.1     .05       0
Bank Sta=5001.1,5007.1
XS Rating Curve= 0 ,0
Exp/Cntr=0.3,0.1

Type RM Length L Ch R = 1 ,5005    ,703,703,703
BEGIN DESCRIPTION:
UNT05306 IN WICK 9.0
END DESCRIPTION:
XS GIS Cut Line= 2
      3573092.12     10234141.66      3572592.11     10233391.65
#Sta/Elev= 30
  4541.6  308.37  4549.1  307.84  4570.2  307.74  4657.3  305.59  4729.4  304.41
  4801.5  303.41  4843.6  303.47  4873.6  302.78  4951.8  302.54  4984.8  302.03
  4987.6  301.53  4990.8  302.03  5059.9  302.36  5082.5     303    5090  303.74
    5096  303.61    5105  305.17    5111  304.66  5118.5  305.51    5141  302.84
  5162.1  303.05  5232.7  304.27  5255.2  305.08  5298.8  305.55  5327.3  306.55
  5357.4  306.84  5370.9  307.46  5393.4  307.62  5420.5  308.73    5443  308.96
#Mann= 3 ,-1 , 0
  4541.6     .05       0  4984.8     .03       0  4990.8     .05       0
Bank Sta=4984.8,4990.8
XS Rating Curve= 0 ,0
Exp/Cntr=0.3,0.1

Type RM Length L Ch R = 1 ,4302    ,25,25,25
BEGIN DESCRIPTION:
Mapping XS fdaa13de
END DESCRIPTION:
XS GIS Cut Line= 5
      3573373.45     10233841.09      3573402.57     10233478.14
      3573389.55     10233386.99      3573280.17     10233256.79
      3573016.21      10233047.5
#Sta/Elev= 30
  4497.8  300.55  4567.5  298.87  4793.4  296.12  4798.4  297.27  4848.4  297.17
  4897.1  299.12  4902.2  297.45  4908.9  297.38  4956.1  300.28  4962.6  298.34
  4970.4  299.02  4976.9  297.21  5005.6  296.27  5077.1  297.14  5097.9  296.25
  5112.2  298.51  5118.6  296.98    5124  296.98  5126.1  298.23  5134.2  296.84
  5140.5  298.09    5155  296.44  5216.1  296.11  5218.8  295.61  5222.1  296.11
  5283.2  296.24  5339.2  298.39  5382.5  298.01  5396.9  299.77  5460.9  301.17
#Mann= 3 ,-1 , 0
  4497.8     .05       0  5216.1    .033       0  5222.1     .05       0
Bank Sta=5216.1,5222.1
XS Rating Curve= 0 ,0
Exp/Cntr=0.3,0.1

Type RM Length L Ch R = 1 ,4277    ,31,31,31
BEGIN DESCRIPTION:
Mapping XS 486f693b
END DESCRIPTION:
XS GIS Cut Line= 5
      3573445.07     10233849.82       3573420.8     10233405.22
       3573360.9     10233311.47      3573285.38     10233235.95
      3573048.79     10233025.89
#Sta/Elev= 30
  4467.7  300.73  4663.2  296.75  4665.9  296.25  4669.2  296.75  4706.2  300.65
  4921.5  301.37  4988.3  300.83  4994.2  299.12  5009.4  300.61  5030.3     299
  5093.9  300.97  5143.6   299.9  5150.2  301.11    5172   299.7  5178.7  300.88
  5186.2  299.59  5192.9   300.9  5200.4  299.65  5207.1  300.93  5214.6  299.83
  5235.5  300.88  5249.8   298.4  5256.5  299.89    5264  298.32  5270.7  299.86
  5278.2  298.71  5284.9  299.82    5356  298.25  5405.3  299.43  5447.4  298.73
#Mann= 3 ,-1 , 0
  4467.7     .05       0  4663.2     .03       0  4669.2     .05       0
Bank Sta=4663.2,4669.2
XS Rating Curve= 0 ,0
Exp/Cntr=0.3,0.1

Type RM Length L Ch R = 1 ,4246    ,294,294,294
BEGIN DESCRIPTION:
Mapping XS e4a321ce
END DESCRIPTION:
XS GIS Cut Line= 5
      3573497.15     10233856.34       3573485.9     10233511.99
      3573462.46     10233381.79      3573303.61     10233212.52
      3573072.39     10233006.12
#Sta/Elev= 30
  4419.9  299.58  4943.7  294.09  4946.4  293.59  4949.7  294.09    4975  294.25
  4981.8  296.49  4989.1  294.93    4996  297.35  5017.5  295.91  5024.3  298.05
  5031.6  296.32  5066.8  299.03  5074.1  297.33    5081  299.24  5088.3  297.11
  5095.2  299.14  5102.5  296.83  5109.3  298.76  5123.5  295.11  5137.6  298.28
  5144.3  296.12  5166.1  298.31  5172.8  296.26  5194.5   298.1  5201.2  296.08
  5222.9  298.07    5258  296.41  5272.2   299.1  5307.4  296.93  5438.8  299.72
#Mann= 3 ,-1 , 0
  4419.9     .05       0  4943.7     .03       0  4949.7     .05       0
Bank Sta=4943.7,4949.7
XS Rating Curve= 0 ,0
Exp/Cntr=0.3,0.1

Type RM Length L Ch R = 1 ,3952    ,493,493,493
BEGIN DESCRIPTION:
UNT05306 IN WICK 7.0
END DESCRIPTION:
XS GIS Cut Line= 2
      3573706.13     10233456.03      3573437.94     10232680.39
#Sta/Elev= 30
  4613.1  292.63  4637.2  292.18  4730.7  291.74  4798.3   292.2  4881.3  290.99
  4924.6  291.11  4935.2  290.84  4942.1  289.98  4956.3  287.93  4966.6   287.1
  4980.1  285.81  4988.1  284.37  4995.7  283.78  4998.4  283.28  5001.7  283.78
  5011.2  286.58  5019.8  287.87  5037.1  290.36  5042.4  290.33  5051.6   291.1
  5073.6  291.79  5099.5  291.96    5115  292.43  5199.7  293.52  5218.9  293.43
  5263.2  295.38    5369  297.31    5380  297.86  5405.9  298.37  5433.8  298.58
#Mann= 5 ,-1 , 0
  4613.1     .05       0  4942.1      .1       0  4966.6     .05       0
  4995.7     .03       0  5001.7     .05       0
Bank Sta=4995.7,5001.7
XS Rating Curve= 0 ,0
Exp/Cntr=0.3,0.1

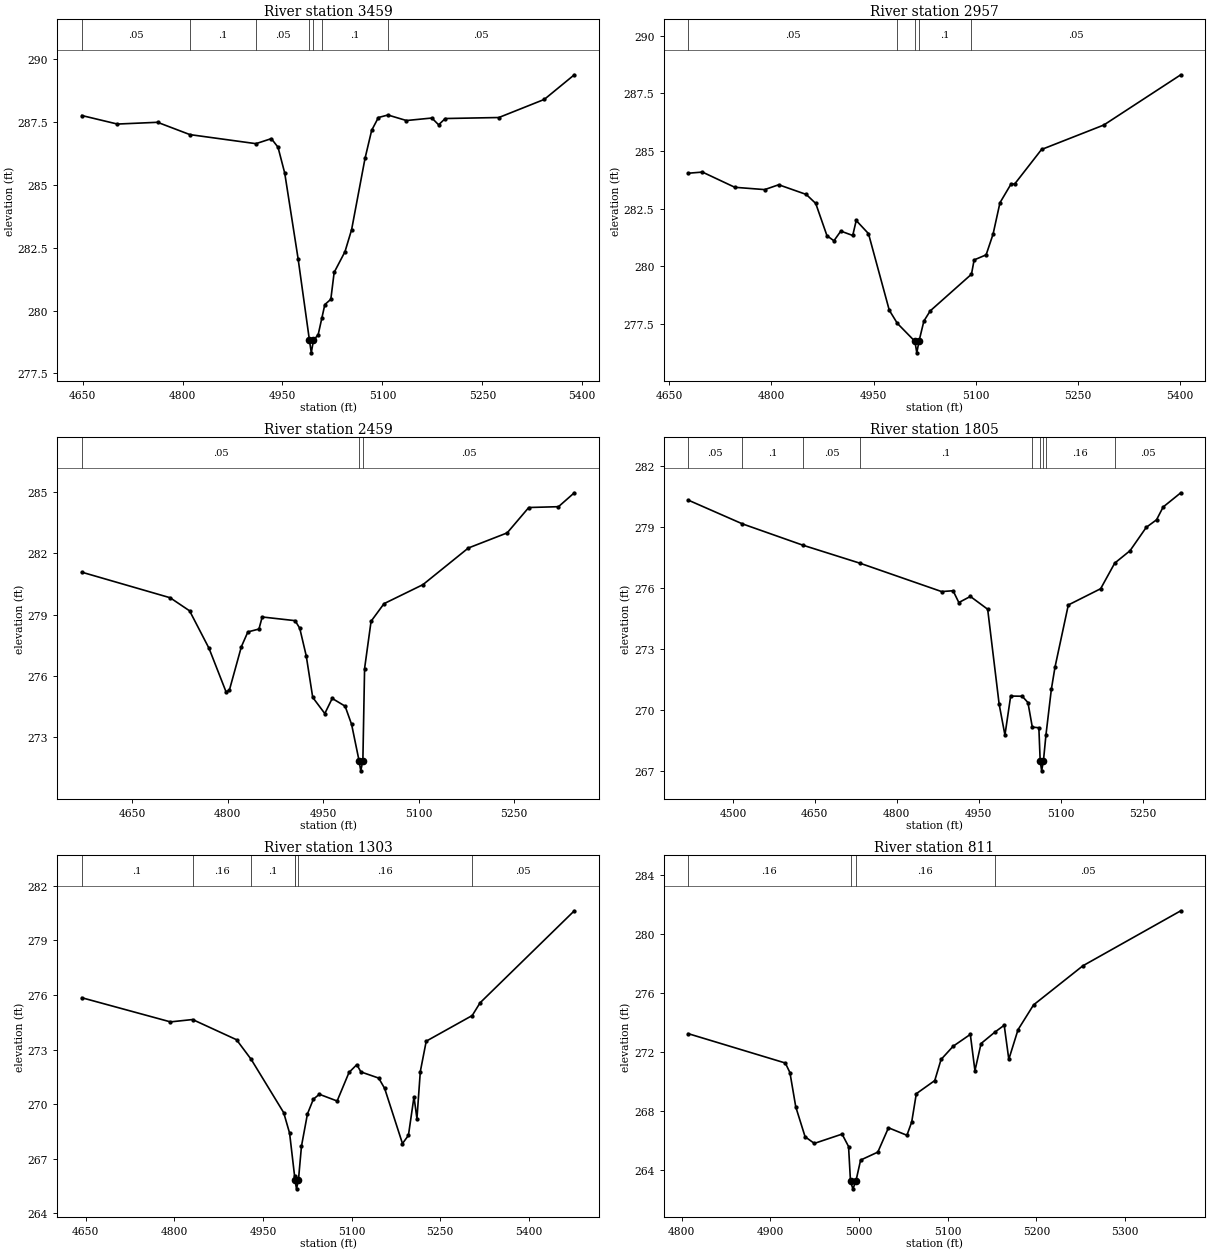
Type RM Length L Ch R = 1 ,3459    ,502,502,502
BEGIN DESCRIPTION:
UNT05306 IN WICK 6.0
END DESCRIPTION:
XS GIS Cut Line= 2
      3574012.59     10233294.96      3573943.15     10232558.83
#Sta/Elev= 30
  4648.7  287.76  4702.2  287.42  4762.5  287.49  4811.1     287  4910.2  286.64
  4933.3  286.84  4943.3   286.5  4953.4  285.47  4973.5  282.06  4990.5  278.82
  4993.3  278.32  4996.5  278.82  5003.6  279.04  5009.2  279.71  5013.6  280.24
  5022.6  280.45  5027.6  281.52  5043.8  282.34  5053.8  283.22  5073.9  286.05
  5083.9  287.17    5094  287.68  5108.3  287.78  5136.1  287.56  5174.3  287.66
  5184.4  287.39  5194.4  287.64  5274.8  287.68    5343   288.4  5388.1  289.38
#Mann= 7 ,-1 , 0
  4648.7     .05       0  4811.1      .1       0  4910.2     .05       0
  4990.5     .03       0  4996.5     .05       0  5009.2      .1       0
  5108.3     .05       0
Bank Sta=4990.5,4996.5
XS Rating Curve= 0 ,0
Exp/Cntr=0.3,0.1

Type RM Length L Ch R = 1 ,2957    ,498,498,498
BEGIN DESCRIPTION:
UNT05306 IN WICK 5.0
END DESCRIPTION:
XS GIS Cut Line= 2
      3574429.26     10233142.18      3574304.26     10232430.38
#Sta/Elev= 30
  4678.1  284.04    4699  284.09  4746.5  283.43  4790.3  283.33  4810.9  283.54
  4851.3  283.12  4865.2  282.73  4881.7  281.33  4891.9  281.11    4902  281.53
  4919.5  281.34  4924.6  281.99  4942.6  281.42  4973.1   278.1  4984.9  277.53
  5010.7  276.75  5013.5  276.25  5016.7  276.75  5023.9  277.63  5033.2  278.07
  5093.7  279.66  5097.6  280.28  5115.2   280.5  5125.4   281.4  5135.5  282.76
  5151.9  283.58    5157  283.57  5196.5  285.07  5287.8  286.13  5400.8  288.31
#Mann= 5 ,-1 , 0
  4678.1     .05       0  4984.9      .1       0  5010.7     .07       0
  5016.7      .1       0  5093.7     .05       0
Bank Sta=5010.7,5016.7
XS Rating Curve= 0 ,0
Exp/Cntr=0.3,0.1

Type RM Length L Ch R = 1 ,2459    ,654,654,654
BEGIN DESCRIPTION:
UNT05306 IN WICK 4.0
END DESCRIPTION:
XS GIS Cut Line= 2
      3574840.53       10233048.      3574693.15     10232288.06
#Sta/Elev= 30
  4570.6  281.07  4709.5  279.82  4740.1  279.18  4770.6  277.35  4797.4  275.22
  4802.5  275.29  4821.5  277.43  4831.7  278.15  4849.1  278.29  4854.2  278.88
  4905.9   278.7  4913.2  278.33  4923.4  276.98  4933.6  274.95  4952.6  274.16
  4964.2   274.9  4984.5  274.52  4994.7  273.63  5006.4  271.86  5009.1  271.36
  5012.4  271.86  5015.1  276.36  5025.3  278.67  5045.6  279.53  5106.8  280.46
  5178.1  282.25  5239.2  282.99  5273.1  284.23  5319.8  284.27  5344.7  284.95
#Mann= 3 ,-1 , 0
  4570.6     .05       0  5006.4     .03       0  5012.4     .05       0
Bank Sta=5006.4,5012.4
XS Rating Curve= 0 ,0
Exp/Cntr=0.3,0.1

Type RM Length L Ch R = 1 ,1805    ,502,502,502
BEGIN DESCRIPTION:
UNT05306 IN WICK 3.0
END DESCRIPTION:
XS GIS Cut Line= 3
      3575342.11     10232891.67      3575142.11     10232291.64
      3574892.14     10232191.66
#Sta/Elev= 30
  4418.2  280.32  4517.5  279.15  4628.3   278.1  4733.2  277.21    4882  275.82
  4903.1  275.86  4913.6  275.28  4934.7  275.58  4966.4  274.95  4987.4  270.28
    4998  268.76  5008.5  270.68  5029.6  270.67  5040.1  270.36  5048.1  269.15
  5060.1  269.12  5062.5   267.5  5065.2     267  5068.5   267.5  5073.1  268.77
    5083  271.02  5089.7  272.11    5114  275.16  5173.2  275.96    5199  277.22
    5227  277.83  5256.7  278.98  5275.5  279.35  5287.6  279.98  5319.9  280.68
#Mann= 9 ,-1 , 0
  4418.2     .05       0  4517.5      .1       0  4628.3     .05       0
  4733.2      .1       0  5048.1     .05       0  5062.5     .07       0
  5068.5     .05       0  5073.1     .16       0    5199     .05       0
Bank Sta=5062.5,5068.5
XS Rating Curve= 0 ,0
Exp/Cntr=0.3,0.1

Type RM Length L Ch R = 1 ,1303    ,492,492,492
BEGIN DESCRIPTION:
UNT05306 IN WICK 2.0
END DESCRIPTION:
XS GIS Cut Line= 2
       3575392.1      10232391.6      3575311.21     10231562.34
#Sta/Elev= 30
  4643.6  275.85  4793.7  274.52  4831.1  274.65  4905.4  273.54  4930.2  272.46
  4985.2  269.53  4995.2   268.4  5003.6  266.05  5004.2  265.84  5006.9  265.34
  5010.2  265.84  5015.3  267.69  5025.4  269.46  5035.4  270.27  5045.5  270.54
  5075.6  270.17  5095.7  271.74  5108.9  272.17  5115.8  271.77  5145.9  271.43
    5156  270.86  5186.1  267.83  5196.2  268.28  5205.6   270.4  5210.6   269.2
  5216.3  271.79  5226.3  273.46  5304.1  274.87  5317.4  275.57  5476.8  280.63
#Mann= 7 ,-1 , 0
  4643.6      .1       0  4831.1     .16       0  4930.2      .1       0
  5003.6     .16       0  5004.2     .07       0  5010.2     .16       0
  5304.1     .05       0
Bank Sta=5004.2,5010.2
XS Rating Curve= 0 ,0
Exp/Cntr=0.3,0.1

Type RM Length L Ch R = 1 ,811     ,323,323,323
BEGIN DESCRIPTION:
Mapping XS 733c4b7e
END DESCRIPTION:
XS GIS Cut Line= 2
      3575599.74     10232037.83      3575439.79     10231505.96
#Sta/Elev= 30
  4807.4  273.27  4916.9  271.28  4922.1  270.63  4928.7   268.3  4939.2  266.28
  4949.6  265.83  4980.9  266.46  4988.2  265.62  4990.4  263.25  4993.1  262.75
  4996.4  263.25  5001.8   264.7  5021.2  265.24  5033.2  266.89    5054  266.38
  5059.4  267.28  5064.6   269.2  5085.4  270.09  5092.5  271.52  5106.2  272.42
  5125.5  273.22  5130.7  270.76  5137.6   272.6  5153.3  273.38  5163.7  273.84
  5168.9  271.53  5179.3  273.54  5196.8  275.22  5252.4  277.87  5362.8   281.6
#Mann= 4 ,-1 , 0
  4807.4     .16       0  4990.4     .07       0  4996.4     .16       0
  5153.3     .05       0
Bank Sta=4990.4,4996.4
XS Rating Curve= 0 ,0
Exp/Cntr=0.3,0.1

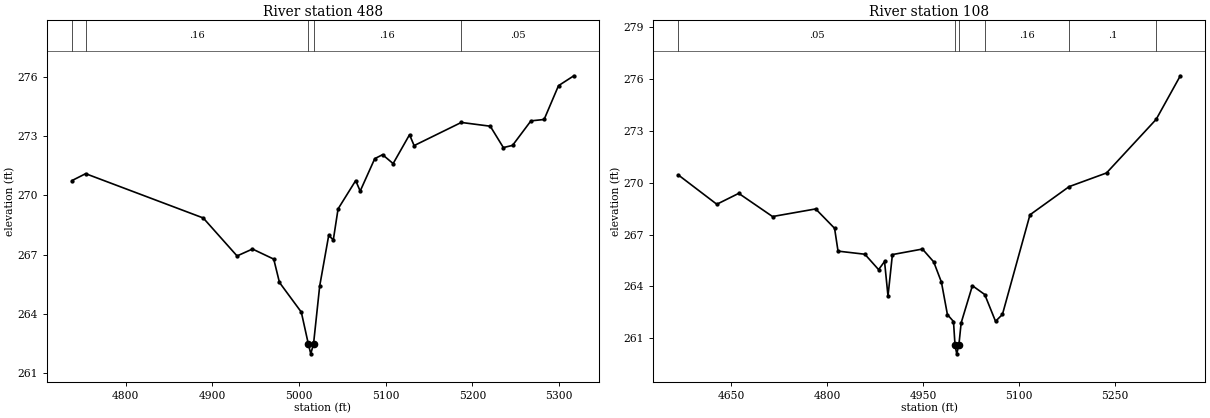
Type RM Length L Ch R = 1 ,488     ,380,380,380
BEGIN DESCRIPTION:
Mapping XS 7efb4d0b
END DESCRIPTION:
XS GIS Cut Line= 2
      3575707.81     10232001.36      3575898.61     10231454.91
#Sta/Elev= 30
  4738.1  270.75  4753.9   271.1  4889.5  268.86  4928.5  266.94  4946.3  267.29
  4970.8  266.78  4977.4   265.6  5002.6   264.1  5010.7  262.49  5013.5  261.99
  5016.7  262.49  5023.8  265.42  5034.2  267.98  5039.5  267.75    5045  269.32
  5065.3  270.75  5070.5  270.22  5087.3  271.86  5096.3  272.06  5108.5  271.61
  5127.4  273.07  5132.7  272.52  5187.1  273.69  5220.5   273.5  5235.6  272.42
  5246.2  272.53  5267.4  273.77  5282.6  273.84  5299.2  275.55  5316.9  276.05
#Mann= 5 ,-1 , 0
  4738.1     .05       0  4753.9     .16       0  5010.7     .07       0
  5016.7     .16       0  5187.1     .05       0
Bank Sta=5010.7,5016.7
XS Rating Curve= 0 ,0
Exp/Cntr=0.3,0.1

Type RM Length L Ch R = 1 ,108     ,0,0,0
BEGIN DESCRIPTION:
UNT05306 IN WICK 1.0
END DESCRIPTION:
XS GIS Cut Line= 4
       3575779.4     10232018.31      3575964.32     10231916.73
      3576099.74     10231576.89      3576015.34     10231386.02
#Sta/Elev= 30
    4567  270.44  4627.1  268.75  4661.4  269.38  4714.3  268.04  4781.8  268.48
  4811.4  267.36  4816.8  266.04  4858.8  265.86  4880.3  264.97  4889.6  265.44
    4895  263.44  4901.9  265.84  4948.9  266.16  4966.5  265.42  4978.6  264.25
    4988  262.37  4997.5  261.97  4999.9   260.6  5002.6   260.1  5005.9   260.6
  5009.5  261.89  5027.1  264.04  5046.4  263.53  5063.3  261.98  5074.1  262.38
  5117.2  268.14  5178.5  269.77    5237  270.56  5314.7  273.66  5352.5  276.18
#Mann= 6 ,-1 , 0
    4567     .05       0  4999.9     .03       0  5005.9     .05       0
  5046.4     .16       0  5178.5      .1       0  5314.7     .05       0
Bank Sta=4999.9,5005.9
XS Rating Curve= 0 ,0
Exp/Cntr=0.3,0.1

Chan Stop Cuts=-1
Use User Specified Reach Order=0
Composite Channel Slope=5