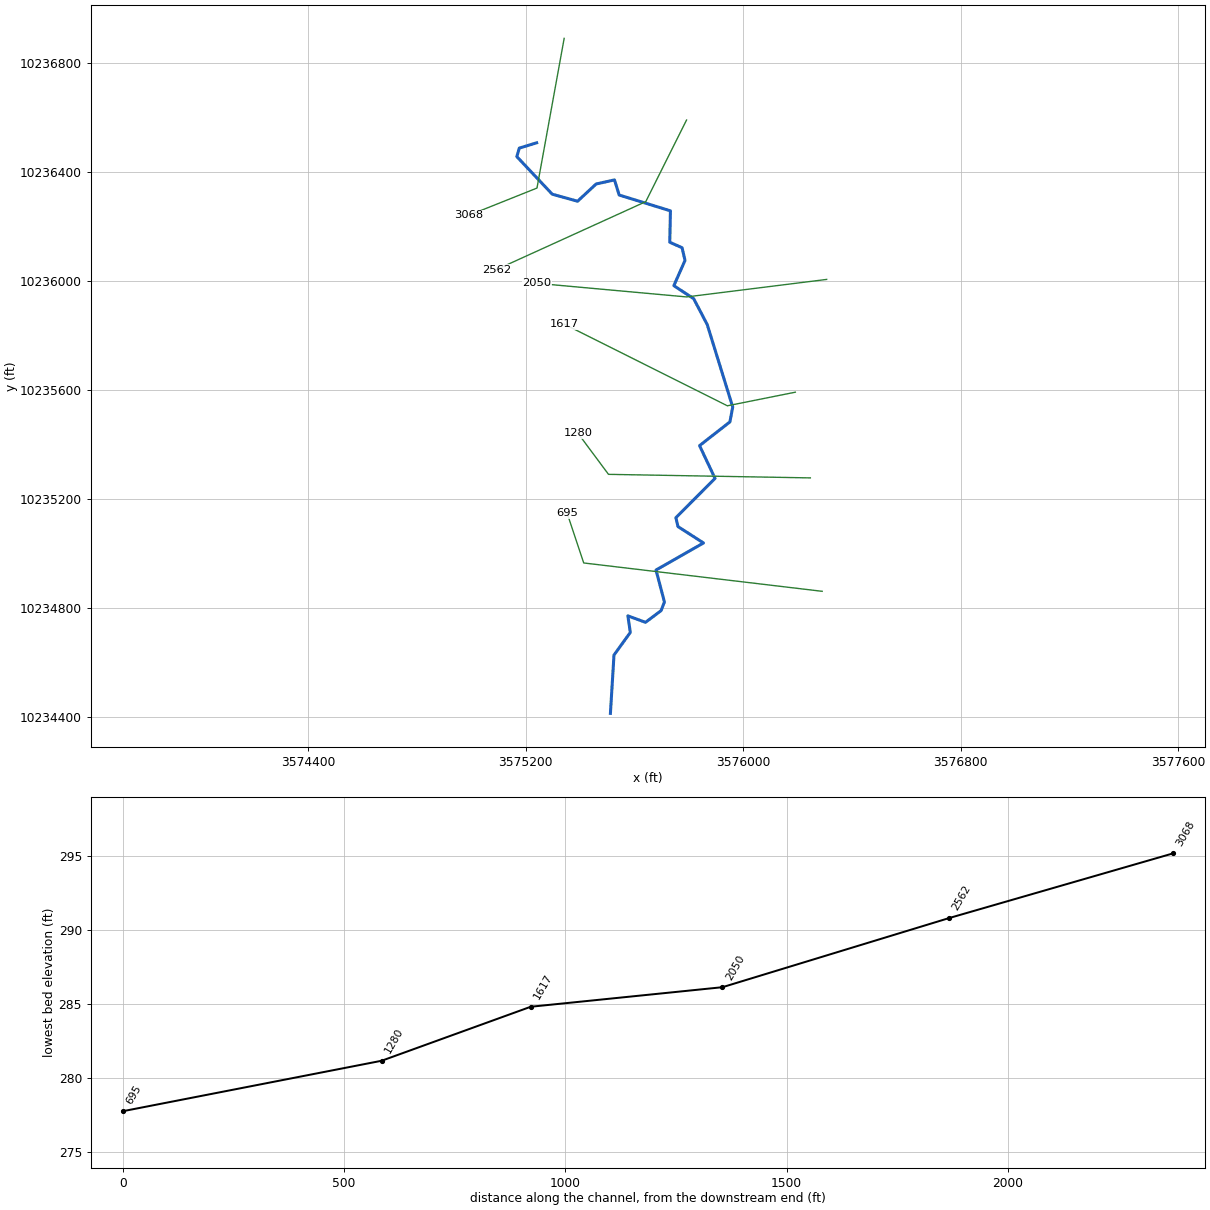
--- BRUSHYCREEKTRIB1.prj (project) ---

Proj Title=BRUSHY CREEK TRIB 10 4
Current Plan=p01
Default Exp/Contr=0.3,0.1
English Units
Geom File=g01
Flow File=f01
Plan File=p01
Y Axis Title=Elevation
X Axis Title(PF)=Main Channel Distance
X Axis Title(XS)=Station
BEGIN DESCRIPTION:
UNT05305 IN WICK
END DESCRIPTION:
DSS Export Rating Curves= 0
DSS Export Rating Curve Sorted= 0
DSS Export Volume Flow Curves= 0
DXF OffsetX= 0
DXF OffsetY= 0
DXF ScaleX= 1
DXF ScaleY= 10

--- BRUSHYCREEKTRIB1.p01 (plan) ---

Plan Title=Multiple Run
Short Identifier=Multiple
Geom File=g01
Flow File=f01
Subcritical Flow
K Sum by GR= 0
Std Step Tol= 0.01
Critical Tol= 0.01
Num of Std Step Trials= 20
Max Error Tol= 0.3
Flow Tol Ratio= 0.001
Split Flow NTrial= 30
Split Flow Tol= 0.02
Split Flow Ratio= 0.02
Log Output Level= 0
Friction Slope Method= 1
Unsteady Friction Slope Method= 2
Unsteady Bridges Friction Slope Method= 1
Parabolic Critical Depth
Global Vel Dist=  1 , 1 , 1
Global Log Level= 0
CheckData=True
Encroach Param= -1, 0, 0, 0
BEGIN DESCRIPTION:
Multiple Run
END DESCRIPTION:

--- BRUSHYCREEKTRIB1.f01 (steady flow) ---

Flow Title=Multiple
Program Version=4.10
Number of Profiles= 7
Profile Names=10-year,25-year,50-year,1pct_min,100-year,1pct_plu,500-year
River Rch & RM=UNT05305 IN WICK,Reach-1         ,3068
     207     261     302     258     348     471     462
River Rch & RM=BRUSHYCRTR104,Reach-1         ,3068
     207     261     302     258     348     471     462
Boundary for River Rch & Prof#=BRUSHYCRTR104,Reach-1         , 1
Up Type= 0
Dn Type= 3
Dn Slope=0.005
Boundary for River Rch & Prof#=BRUSHYCRTR104,Reach-1         , 2
Up Type= 0
Dn Type= 3
Dn Slope=0.005
Boundary for River Rch & Prof#=BRUSHYCRTR104,Reach-1         , 3
Up Type= 0
Dn Type= 3
Dn Slope=0.005
Boundary for River Rch & Prof#=BRUSHYCRTR104,Reach-1         , 4
Up Type= 0
Dn Type= 3
Dn Slope=0.005
Boundary for River Rch & Prof#=BRUSHYCRTR104,Reach-1         , 5
Up Type= 0
Dn Type= 3
Dn Slope=0.005
Boundary for River Rch & Prof#=BRUSHYCRTR104,Reach-1         , 6
Up Type= 0
Dn Type= 3
Dn Slope=0.005
Boundary for River Rch & Prof#=BRUSHYCRTR104,Reach-1         , 7
Up Type= 0
Dn Type= 3
Dn Slope=0.005
DSS Import GetInterval= 0
DSS Import GetPeak= 0
DSS Import FillOption= 0

--- BRUSHYCREEKTRIB1.g01 (geometry) ---

Geom Title=Existing Conditions
Program Version=4.10

River Reach=BRUSHYCRTR104   ,Reach-1
Reach XY= 30
       3575240.9     10236507.87      3575177.09     10236488.34
      3575167.98     10236457.09      3575298.19     10236319.07
      3575391.38     10236293.25      3575459.65     10236356.58
      3575527.05     10236371.53      3575544.38     10236315.97
      3575732.81     10236257.93      3575730.37      10236142.6
      3575775.63     10236122.31       3575786.4     10236075.67
      3575745.34     10235982.98      3575818.37     10235935.06
      3575868.12       10235840.      3575961.84     10235537.17
       3575951.5      10235482.5      3575839.92     10235395.33
      3575896.76     10235274.91      3575752.86     10235130.57
      3575760.46     10235097.96      3575854.39     10235037.69
      3575679.76     10234938.29      3575710.72     10234820.89
      3575698.56      10234789.3      3575641.13     10234746.14
      3575576.29     10234769.88      3575585.38     10234709.14
      3575525.28       10234626.      3575512.11     10234411.64

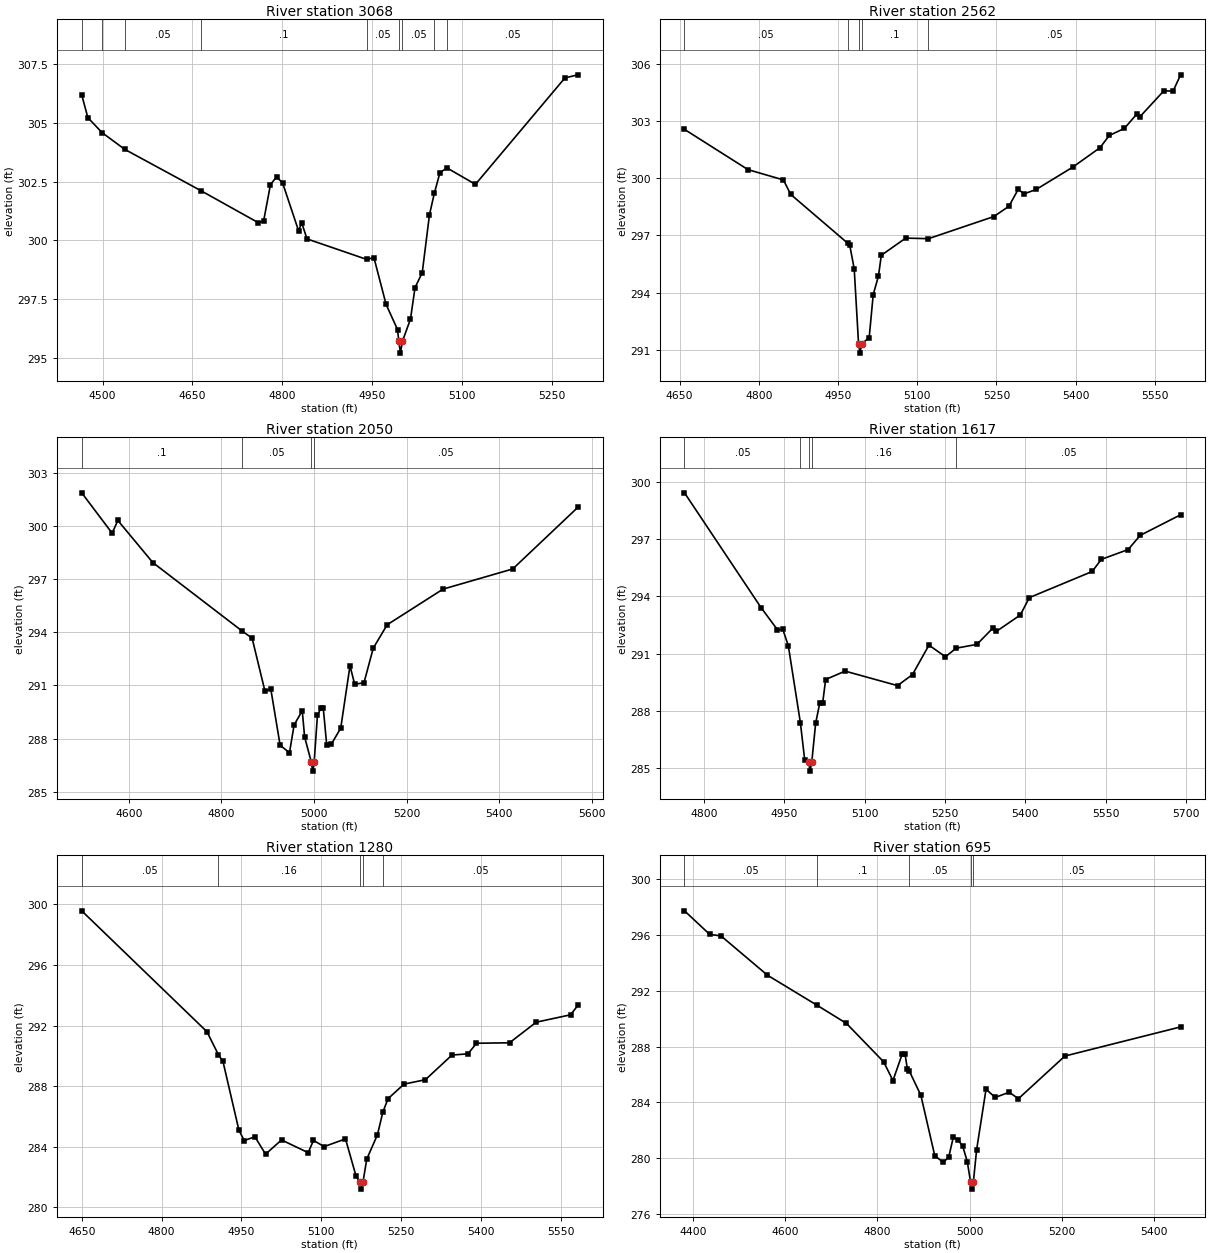
Type RM Length L Ch R = 1 ,3068    ,506,506,506
BEGIN DESCRIPTION:
UNT05305 IN WICK 6.0
END DESCRIPTION:
XS GIS Cut Line= 3
      3575342.11     10236891.67      3575242.11     10236341.64
       3574992.1     10236241.64
#Sta/Elev= 30
  4465.3  306.19  4475.5  305.22  4499.3  304.58  4537.1  303.87  4665.1   302.1
  4760.1  300.75    4769  300.82  4780.4  302.37  4790.6   302.7  4800.7  302.44
  4827.4   300.4  4832.5  300.75  4841.4  300.06  4940.8  299.19  4953.2  299.26
  4973.5  297.27  4992.6   296.2  4994.7   295.7  4997.4   295.2  5000.7   295.7
  5014.2  296.65  5021.8  297.99  5033.8  298.62  5045.9  301.09    5054     302
  5063.4  302.88  5075.1  303.08  5122.6  302.38  5272.1  306.91  5293.6  307.04
#Mann= 9 ,-1 , 0
  4465.3     .05       0  4499.3     .16       0  4537.1     .05       0
  4665.1      .1       0  4940.8     .05       0  4994.7     .03       0
  5000.7     .05       0    5054     .16       0  5075.1     .05       0
Bank Sta=4994.7,5000.7
XS Rating Curve= 0 ,0
Exp/Cntr=0.3,0.1

Type RM Length L Ch R = 1 ,2562    ,512,512,512
BEGIN DESCRIPTION:
UNT05305 IN WICK 5.0
END DESCRIPTION:
XS GIS Cut Line= 3
       3575792.1     10236591.63      3575642.11     10236291.64
      3575092.15     10236041.66
#Sta/Elev= 30
  4659.2  302.56  4779.4  300.45  4846.5  299.91  4860.4  299.15  4968.8  296.58
  4972.2  296.48  4980.6  295.25  4988.8  291.33  4991.6  290.83  4994.8  291.33
  5008.9  291.63  5016.6   293.9  5026.5  294.87  5031.9  295.96  5078.1  296.86
  5121.2  296.83    5245  297.99  5273.6  298.53  5291.2  299.42  5302.2  299.18
  5325.2  299.41  5394.4  300.58  5446.1   301.6  5463.6  302.24  5492.2  302.61
  5515.3  303.35  5521.9  303.23  5566.9  304.58  5584.5  304.57  5598.7  305.42
#Mann= 5 ,-1 , 0
  4659.2     .05       0  4968.8      .1       0  4988.8     .07       0
  4994.8      .1       0  5121.2     .05       0
Bank Sta=4988.8,4994.8
XS Rating Curve= 0 ,0
Exp/Cntr=0.3,0.1

Type RM Length L Ch R = 1 ,2050    ,433,433,433
BEGIN DESCRIPTION:
UNT05305 IN WICK 4.0
END DESCRIPTION:
XS GIS Cut Line= 3
      3576307.31     10236005.95      3575792.11     10235941.64
      3575242.07     10235991.65
#Sta/Elev= 30
  4498.5  301.88  4564.2   299.6  4576.5  300.32  4652.1  297.94  4845.1  294.07
  4866.5  293.67  4894.2  290.68  4906.8  290.81    4927  287.62  4947.2   287.2
  4957.2  288.77  4974.8  289.57  4979.9  288.09  4994.5  286.66  4997.3  286.16
  5000.5  286.66  5007.6  289.32  5015.2  289.72  5020.2  289.72  5027.7  287.62
  5037.8  287.69  5057.9  288.59  5077.9  292.11    5088  291.07  5108.1  291.15
  5128.2  293.11  5158.3  294.43  5278.8  296.44  5429.4  297.58    5570  301.06
#Mann= 4 ,-1 , 0
  4498.5      .1       0  4845.1     .05       0  4994.5     .03       0
  5000.5     .05       0
Bank Sta=4994.5,5000.5
XS Rating Curve= 0 ,0
Exp/Cntr=0.3,0.1

Type RM Length L Ch R = 1 ,1617    ,337,337,337
BEGIN DESCRIPTION:
UNT05305 IN WICK 3.0
END DESCRIPTION:
XS GIS Cut Line= 3
      3576192.12     10235591.65      3575942.11     10235541.64
      3575342.09     10235841.65
#Sta/Elev= 30
  4763.8  299.42  4906.6  293.41  4937.2  292.25  4947.4  292.26  4957.6   291.4
  4980.1  287.37  4988.2  285.41  4995.4  285.34  4998.1  284.84  5001.4  285.34
  5008.6  287.36  5016.2   288.4  5021.6   288.4  5027.2  289.64  5063.5  290.08
  5161.3  289.32  5189.3   289.9    5220  291.44  5250.8  290.83  5270.6  291.28
  5309.5  291.48  5340.2  292.36  5345.8  292.16  5390.5  293.02  5407.3  293.93
  5524.7   295.3  5541.4  295.93  5591.8  296.45  5614.1  297.19  5689.6  298.27
#Mann= 5 ,-1 , 0
  4763.8     .05       0  4980.1     .16       0  4995.4     .07       0
  5001.4     .16       0  5270.6     .05       0
Bank Sta=4995.4,5001.4
XS Rating Curve= 0 ,0
Exp/Cntr=0.3,0.1

Type RM Length L Ch R = 1 ,1280    ,585,585,585
BEGIN DESCRIPTION:
UNT05305 IN WICK 2.0
END DESCRIPTION:
XS GIS Cut Line= 3
      3576247.28     10235276.78      3575505.07      10235289.8
      3575392.09     10235441.66
#Sta/Elev= 30
    4650  299.58  4885.2  291.59  4906.8  290.06  4915.2  289.63  4945.2  285.08
  4955.2   284.4  4975.2  284.65  4995.2   283.5  5025.2  284.44  5075.2   283.6
  5085.2  284.41  5105.2     284  5145.3  284.51  5165.3  282.03  5172.3  281.69
    5175  281.19  5178.3  281.69  5185.3  283.18  5205.3  284.78  5215.6   286.3
  5225.3  287.17  5255.3  288.13  5295.3  288.42  5345.3  290.05  5375.3  290.13
  5391.3  290.83  5453.3  290.86  5503.4  292.22    5568  292.71  5581.6  293.33
#Mann= 5 ,-1 , 0
    4650     .05       0  4906.8     .16       0  5172.3     .07       0
  5178.3     .16       0  5215.6     .05       0
Bank Sta=5172.3,5178.3
XS Rating Curve= 0 ,0
Exp/Cntr=0.3,0.1

Type RM Length L Ch R = 1 ,695     ,0,0,0
BEGIN DESCRIPTION:
UNT05305 IN WICK 1.0
END DESCRIPTION:
XS GIS Cut Line= 3
      3576290.65     10234860.11      3575413.93     10234964.28
      3575353.18     10235146.53
#Sta/Elev= 30
  4381.9  297.75  4436.5  296.06    4461  295.95  4561.7  293.13  4668.8  290.98
  4732.9  289.67  4813.5  286.91  4833.6  285.57  4853.7  287.48  4859.9  287.45
  4864.9  286.38  4868.5  286.29    4894  284.52  4924.2  280.18  4942.6   279.7
  4954.4  280.07  4964.5  281.52  4974.6   281.3  4984.7  280.87  4994.7  279.75
  5001.8  278.28  5004.5  277.78  5007.8  278.28  5014.9  280.61  5035.3  284.95
  5055.1  284.36  5085.4  284.73  5105.5  284.27  5206.2  287.33  5456.9  289.42
#Mann= 5 ,-1 , 0
  4381.9     .05       0  4668.8      .1       0  4868.5     .05       0
  5001.8     .03       0  5007.8     .05       0
Bank Sta=5001.8,5007.8
XS Rating Curve= 0 ,0
Exp/Cntr=0.3,0.1

Chan Stop Cuts=-1
Use User Specified Reach Order=0
Composite Channel Slope=5