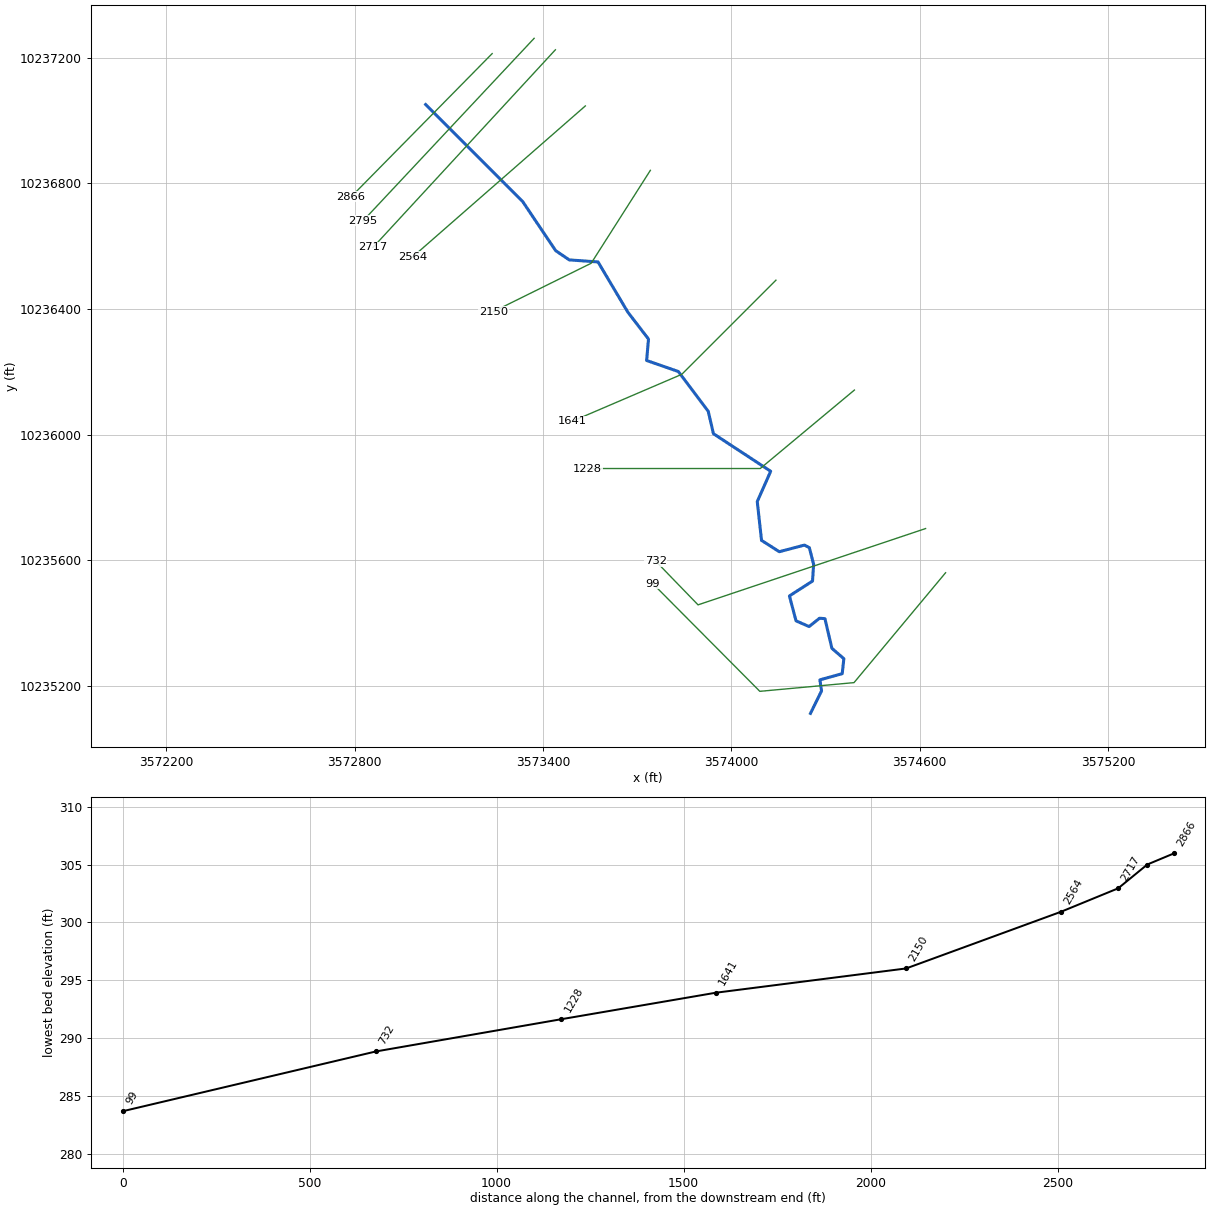
--- BRUSHYCREEKTRIB1.prj (project) ---

Proj Title=BRUSHY CREEK TRIB 10 5
Current Plan=p01
Default Exp/Contr=0.3,0.1
English Units
Geom File=g01
Flow File=f01
Plan File=p01
Y Axis Title=Elevation
X Axis Title(PF)=Main Channel Distance
X Axis Title(XS)=Station
BEGIN DESCRIPTION:
UNT05304 IN WICK
END DESCRIPTION:
DSS Export Rating Curves= 0
DSS Export Rating Curve Sorted= 0
DSS Export Volume Flow Curves= 0
DXF Filename=UNT05304 IN WICK.
DXF OffsetX= 0
DXF OffsetY= 0
DXF ScaleX= 1
DXF ScaleY= 10

--- BRUSHYCREEKTRIB1.p01 (plan) ---

Plan Title=Multiple Run
Short Identifier=Multiple
Geom File=g01
Flow File=f01
Subcritical Flow
K Sum by GR= 0
Std Step Tol= 0.01
Critical Tol= 0.01
Num of Std Step Trials= 20
Max Error Tol= 0.3
Flow Tol Ratio= 0.001
Split Flow NTrial= 30
Split Flow Tol= 0.02
Split Flow Ratio= 0.02
Log Output Level= 0
Friction Slope Method= 1
Unsteady Friction Slope Method= 2
Unsteady Bridges Friction Slope Method= 1
Parabolic Critical Depth
Global Vel Dist=  1 , 1 , 1
Global Log Level= 0
CheckData=True
Encroach Param= -1, 0, 0, 0
BEGIN DESCRIPTION:
Multiple Run
END DESCRIPTION:

--- BRUSHYCREEKTRIB1.f01 (steady flow) ---

Flow Title=Multiple
Program Version=4.10
Number of Profiles= 7
Profile Names=10-year,25-year,50-year,1pct_min,100-year,1pct_plu,500-year
River Rch & RM=UNT05304 IN WICK,Reach-1         ,2866
     137     167     189     159     214     290     274
River Rch & RM=BRUSHYCRTR105,Reach-1         ,2866
     137     167     189     159     214     290     274
Boundary for River Rch & Prof#=BRUSHYCRTR105,Reach-1         , 1
Up Type= 0
Dn Type= 3
Dn Slope=0.005
Boundary for River Rch & Prof#=BRUSHYCRTR105,Reach-1         , 2
Up Type= 0
Dn Type= 3
Dn Slope=0.005
Boundary for River Rch & Prof#=BRUSHYCRTR105,Reach-1         , 3
Up Type= 0
Dn Type= 3
Dn Slope=0.005
Boundary for River Rch & Prof#=BRUSHYCRTR105,Reach-1         , 4
Up Type= 0
Dn Type= 3
Dn Slope=0.005
Boundary for River Rch & Prof#=BRUSHYCRTR105,Reach-1         , 5
Up Type= 0
Dn Type= 3
Dn Slope=0.005
Boundary for River Rch & Prof#=BRUSHYCRTR105,Reach-1         , 6
Up Type= 0
Dn Type= 3
Dn Slope=0.005
Boundary for River Rch & Prof#=BRUSHYCRTR105,Reach-1         , 7
Up Type= 0
Dn Type= 3
Dn Slope=0.005
DSS Import GetInterval= 0
DSS Import GetPeak= 0
DSS Import FillOption= 0

--- BRUSHYCREEKTRIB1.g01 (geometry) ---

Geom Title=Existing Conditions
Program Version=4.10

River Reach=BRUSHYCRTR105   ,Reach-1
Reach XY= 30
       3573026.3     10237051.01      3573335.37     10236742.02
      3573440.36     10236585.73      3573483.76     10236556.22
      3573575.34      10236549.7      3573670.02     10236390.17
      3573736.16     10236303.95      3573730.15     10236235.79
      3573831.17     10236200.64       3573926.4     10236073.95
      3573943.01      10236002.5      3574125.37     10235882.86
       3574082.6     10235786.31       3574096.2     10235662.75
      3574152.79     10235626.62      3574232.94     10235647.73
       3574248.5     10235639.55      3574262.15     10235586.48
      3574258.64     10235533.11      3574185.05      10235485.8
       3574206.1     10235406.49      3574247.71      10235388.2
      3574281.07     10235414.74      3574298.15     10235413.34
       3574320.4     10235318.75      3574358.45     10235285.85
      3574353.22     10235238.08       3574282.1     10235218.38
      3574287.41     10235183.11      3574252.11     10235111.64

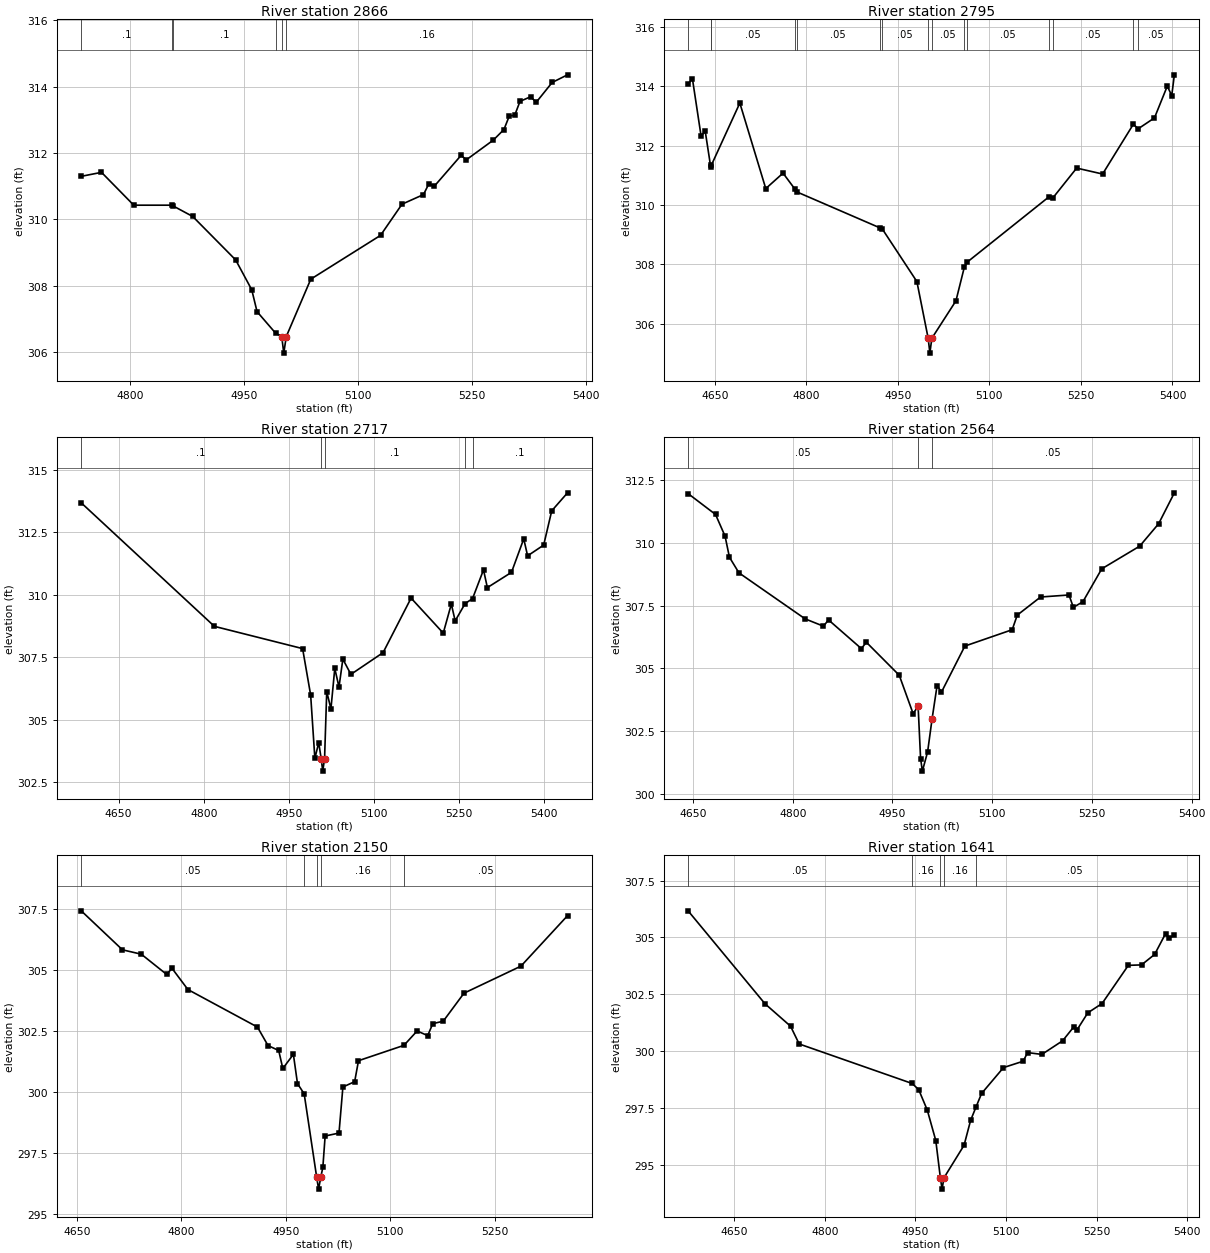
Type RM Length L Ch R = 1 ,2866    ,71,71,71
BEGIN DESCRIPTION:
UNT05304 IN WICK 5.0
END DESCRIPTION:
XS GIS Cut Line= 2
       3573238.1      10237213.4      3572788.47     10236756.83
#Sta/Elev= 30
  4735.4   311.3  4762.1  311.42  4804.6  310.43  4854.8  310.43  4856.3  310.41
  4882.3  310.09  4938.9  308.78  4960.1  307.88  4967.1  307.22  4991.6  306.57
  4999.6  306.47  5002.3  305.97  5005.6  306.47  5037.9   308.2  5129.8  309.52
  5158.1  310.46  5186.4  310.75  5193.4  311.07  5200.6     311  5235.9  311.93
    5243   311.8  5278.3  312.39  5292.4  312.71  5299.5  313.12  5306.6  313.14
  5313.6  313.56  5327.7   313.7  5334.9  313.53    5356  314.13  5376.2  314.36
#Mann= 6 ,-1 , 0
  4735.4      .1       0  4854.8     .05       0  4856.3      .1       0
  4991.6     .16       0  4999.6     .07       0  5005.6     .16       0
Bank Sta=4999.6,5005.6
XS Rating Curve= 0 ,0
Exp/Cntr=0.3,0.1

Type RM Length L Ch R = 1 ,2795    ,78,78,78
BEGIN DESCRIPTION:
Mapping XS cacb2d56
END DESCRIPTION:
XS GIS Cut Line= 2
      3573371.79     10237262.02      3572826.88     10236680.67
#Sta/Elev= 30
  4606.3  314.07  4613.4  314.25  4627.6  312.32  4634.4  312.48  4643.3  311.29
  4644.5  311.34  4691.1  313.43  4733.6  310.55  4761.9  311.07  4781.8  310.52
  4784.3  310.44  4920.4  309.23  4924.2   309.2  4981.2  307.42  4999.7  305.51
  5002.5  305.01  5005.7  305.51  5045.2  306.77  5058.9   307.9    5064  308.08
  5197.5  310.27  5203.8  310.23    5243  311.24  5285.5  311.04    5336  312.72
  5343.6  312.56  5370.5  312.93  5391.5     314  5398.8  313.68  5403.1  314.38
#Mann= 15 ,-1 , 0
  4606.3     .05       0  4643.3      .1       0  4644.5     .05       0
  4781.8      .1       0  4784.3     .05       0  4920.4      .1       0
  4924.2     .05       0  4999.7     .04       0  5005.7     .05       0
  5058.9     .16       0    5064     .05       0  5197.5     .16       0
  5203.8     .05       0    5336     .16       0  5343.6     .05       0
Bank Sta=4999.7,5005.7
XS Rating Curve= 0 ,0
Exp/Cntr=0.3,0.1

Type RM Length L Ch R = 1 ,2717    ,153,153,153
BEGIN DESCRIPTION:
Mapping XS 96df9314
END DESCRIPTION:
XS GIS Cut Line= 2
      3573439.49     10237225.55      3572858.48     10236595.98
#Sta/Elev= 30
  4584.1  313.68  4818.7  308.74  4974.1  307.85  4988.3  305.99  4995.7  303.46
  5002.5  304.09  5006.8  303.45  5009.6  302.95  5012.8  303.45  5016.6  306.13
    5024  305.44  5030.8  307.06  5038.2  306.31    5045  307.43  5059.2  306.82
  5115.9  307.69  5165.2  309.87  5221.9  308.47  5236.1  309.63  5242.9  308.96
  5260.4  309.65  5273.5  309.85  5292.8     311  5299.6  310.29  5342.1   310.9
  5363.7  312.24  5370.5  311.56  5398.8  311.99    5413  313.36  5440.8  314.08
#Mann= 5 ,-1 , 0
  4584.1      .1       0  5006.8     .07       0  5012.8      .1       0
  5260.4     .05       0  5273.5      .1       0
Bank Sta=5006.8,5012.8
XS Rating Curve= 0 ,0
Exp/Cntr=0.3,0.1

Type RM Length L Ch R = 1 ,2564    ,414,414,414
BEGIN DESCRIPTION:
Mapping XS 45121703
END DESCRIPTION:
XS GIS Cut Line= 2
      3573534.96     10237046.72      3572984.31     10236565.33
#Sta/Elev= 30
  4642.6  311.95  4683.9  311.12  4698.2  310.26  4704.8  309.42  4719.1   308.8
  4818.7  306.97  4846.2  306.68  4853.8  306.93  4903.2  305.79  4910.8  306.04
  4960.2  304.73    4981  303.21  4988.6  303.49  4992.3  301.42    4995  300.92
  5002.9  301.69  5009.5  302.98  5017.1  304.32  5023.7  304.06  5058.9  305.89
  5130.1  306.54  5137.7  307.12  5172.8  307.84  5215.5  307.92  5222.1  307.43
  5236.4  307.65  5264.8  308.96  5321.8  309.86  5350.3  310.75    5374  311.98
#Mann= 3 , 0 , 0
  4642.6     .05       0  4988.6     .03       0  5009.5     .05       0
Bank Sta=4988.6,5009.5
XS Rating Curve= 0 ,0
Exp/Cntr=0.3,0.1

Type RM Length L Ch R = 1 ,2150    ,509,509,509
BEGIN DESCRIPTION:
UNT05304 IN WICK 4.0
END DESCRIPTION:
XS GIS Cut Line= 3
      3573742.09     10236841.61      3573553.58     10236545.56
      3573242.11     10236391.64
#Sta/Elev= 30
  4656.2  307.44  4715.4  305.84  4742.5  305.66  4778.9  304.83  4786.6  305.08
  4809.4  304.21  4909.3  302.67  4924.5  301.91  4939.8  301.71  4945.7  300.97
  4960.9  301.55  4966.8  300.35  4976.4  299.93  4994.3  296.52  4997.1  296.02
  5000.3  296.52  5003.2  296.91  5006.5   298.2  5026.4  298.32    5032  300.21
  5048.9  300.43  5054.4  301.29  5119.7  301.92  5138.6  302.51  5153.8  302.32
  5161.1  302.81  5176.1  302.91  5205.9  304.06  5287.7  305.17  5354.6  307.24
#Mann= 5 ,-1 , 0
  4656.2     .05       0  4976.4     .16       0  4994.3     .07       0
  5000.3     .16       0  5119.7     .05       0
Bank Sta=4994.3,5000.3
XS Rating Curve= 0 ,0
Exp/Cntr=0.3,0.1

Type RM Length L Ch R = 1 ,1641    ,413,413,413
BEGIN DESCRIPTION:
UNT05304 IN WICK 3.0
END DESCRIPTION:
XS GIS Cut Line= 3
      3574142.11     10236491.65      3573842.11     10236191.64
      3573492.07     10236041.63
#Sta/Elev= 30
  4573.7  306.17    4701  302.08  4743.4  301.09  4757.6  300.31  4944.7  298.57
  4955.5   298.3  4969.7   297.4  4983.8  296.06  4991.4  294.42  4994.2  293.92
  4997.4  294.42  5030.6  295.85  5041.5  296.95  5050.2  297.52  5059.6  298.13
  5095.9  299.27  5128.5  299.55  5135.8  299.93  5159.4  299.85  5193.8  300.45
  5211.9  301.05  5217.4  300.92  5235.5  301.68  5259.1  302.09  5302.6  303.77
  5324.4  303.79  5346.1  304.25  5364.3  305.17  5369.7  304.97  5378.8   305.1
#Mann= 5 ,-1 , 0
  4573.7     .05       0  4944.7     .16       0  4991.4     .07       0
  4997.4     .16       0  5050.2     .05       0
Bank Sta=4991.4,4997.4
XS Rating Curve= 0 ,0
Exp/Cntr=0.3,0.1

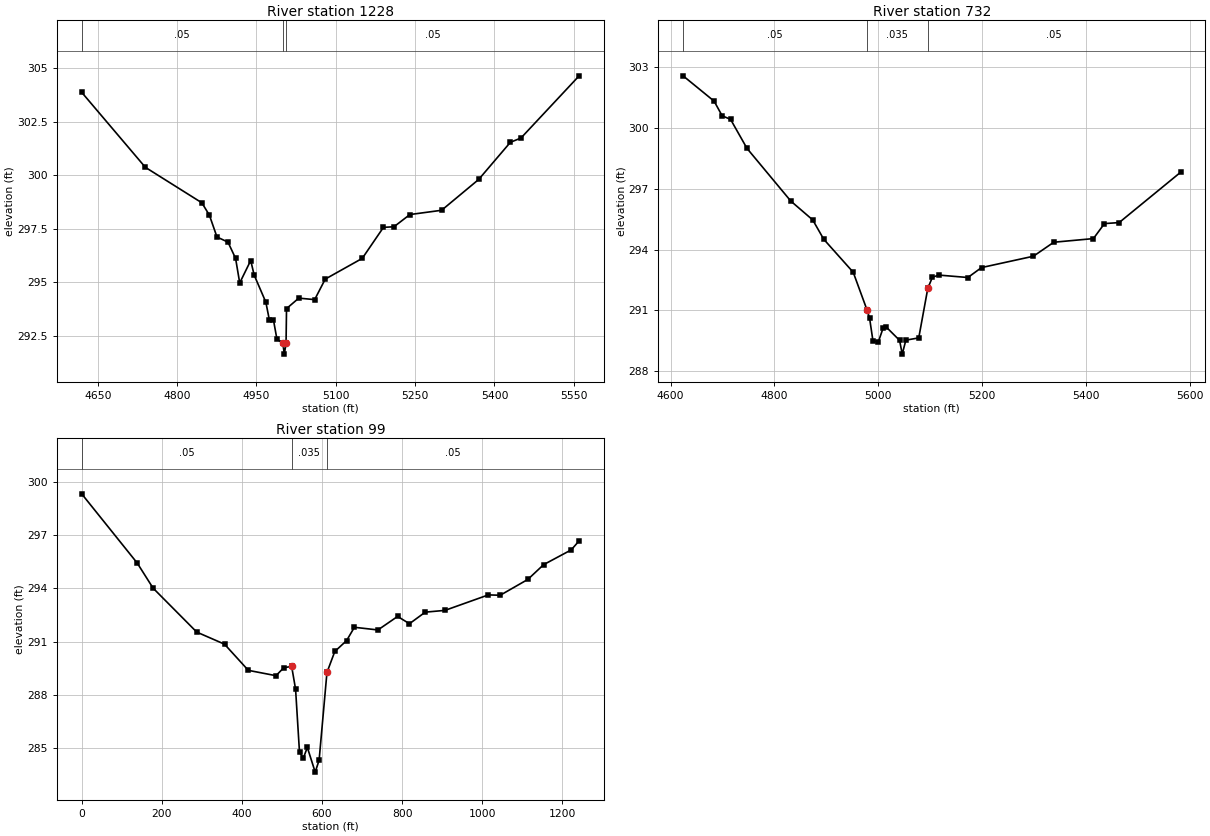
Type RM Length L Ch R = 1 ,1228    ,496,496,496
BEGIN DESCRIPTION:
UNT05304 IN WICK 2.0
END DESCRIPTION:
XS GIS Cut Line= 3
      3574392.12     10236141.66      3574092.11     10235891.64
      3573542.14     10235891.64
#Sta/Elev= 30
  4619.6  303.88    4740  300.37  4846.8  298.71  4861.1  298.13  4875.4  297.11
  4896.2  296.87  4910.6  296.11  4918.4  294.96  4939.2  296.01  4945.7  295.33
  4967.8  294.06  4974.3  293.25  4982.1  293.24  4988.7  292.34    5000  292.13
  5002.7  291.63    5006  292.13  5006.9  293.76  5030.1  294.25  5060.1  294.18
  5080.1  295.14  5150.1  296.11  5190.1  297.56  5210.1  297.59  5240.1  298.16
  5300.1  298.36  5370.1   299.8  5430.1  301.54  5450.1  301.74  5560.1  304.65
#Mann= 3 ,-1 , 0
  4619.6     .05       0    5000    .035       0    5006     .05       0
Bank Sta=5000,5006
XS Rating Curve= 0 ,0
Exp/Cntr=0.3,0.1

Type RM Length L Ch R = 1 ,732     ,677,677,677
BEGIN DESCRIPTION:
UNT05304 IN WICK 1.0
END DESCRIPTION:
XS GIS Cut Line= 3
      3574618.83     10235700.41      3573893.96     10235457.33
      3573759.42     10235596.21
#Sta/Elev= 30
  4624.2  302.57    4684  301.32  4699.4   300.6  4715.7  300.42  4747.3  298.99
  4831.7  296.39  4873.9  295.46    4895  294.51  4951.8  292.88  4978.1  291.04
  4983.3  290.62  4989.9  289.48  5000.4  289.46  5009.6  290.14  5014.9  290.19
  5041.1  289.52  5046.2  288.84  5053.2  289.53    5078  289.64  5095.4  292.08
  5104.2  292.63  5116.5  292.74  5172.6  292.62  5198.9  293.11  5298.8  293.67
    5338  294.36  5414.3  294.54  5435.6  295.28  5463.9  295.33  5582.1  297.81
#Mann= 3 , 0 , 0
  4624.2     .05       0  4978.1    .035       0  5095.4     .05       0
Bank Sta=4978.1,5095.4
XS Rating Curve= 0 ,0
Exp/Cntr=0.3,0.1

Type RM Length L Ch R = 1 ,99      ,0,0,0
XS GIS Cut Line= 4
     3574682.471      10235559.6     3574390.804      10235209.6
     3574090.804    10235181.822     3573749.832    10235524.878
#Sta/Elev= 30
       0  299.31  138.69  295.42  178.31  294.01  287.28  291.54  356.63  290.86
  416.06  289.39  485.06  289.09  504.64  289.54  524.22  289.61  534.01  288.33
   543.8  284.78  553.59  284.47  563.38  285.06  582.96  283.67  592.75  284.34
  612.33  289.27  631.91  290.45  661.28  291.06  680.86  291.81   739.6  291.66
  788.73  292.42  818.28  292.01  857.69  292.66  906.94  292.76  1015.3  293.63
 1044.86  293.61 1113.81   294.5 1153.22  295.33 1222.17  296.16 1241.88  296.67
#Mann= 3 , 0 , 0
       0     .05       0  524.22    .035       0  612.33     .05       0
Bank Sta=524.22,612.33
XS Rating Curve= 0 ,0
Exp/Cntr=0.3,0.1

Chan Stop Cuts=-1
Use User Specified Reach Order=0
Composite Channel Slope=5