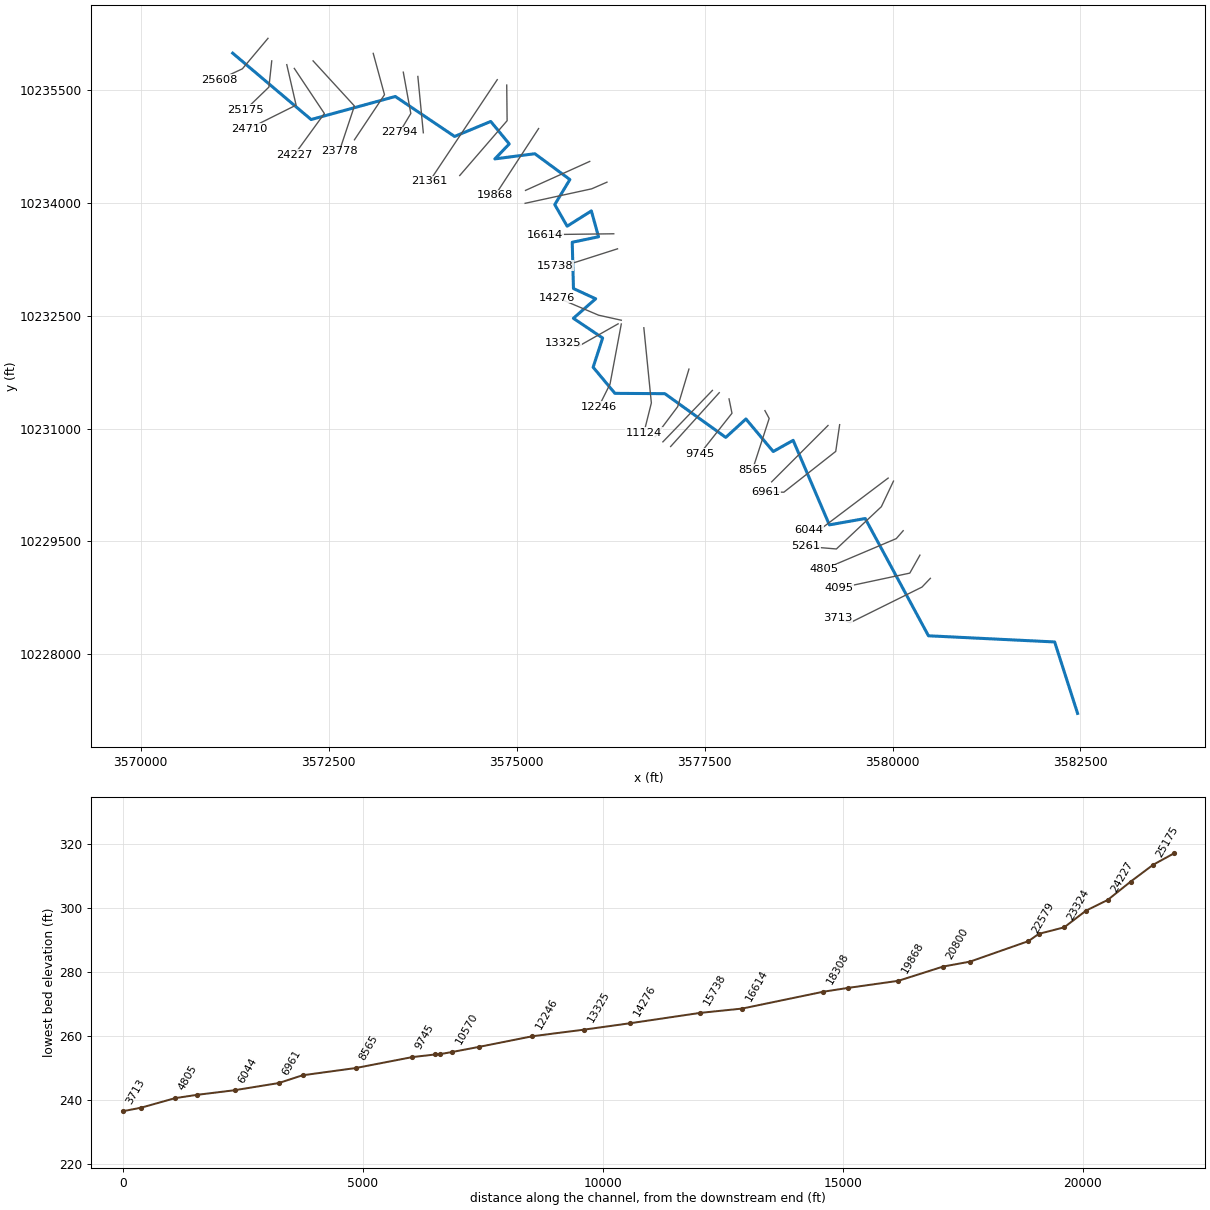
--- BRUSHYCREEKTRIB1.prj (project) ---

Proj Title=BRUSHY CREEK TRIB 10
Current Plan=p01
Default Exp/Contr=0.3,0.1
English Units
Geom File=g01
Flow File=f01
Plan File=p01
Y Axis Title=Elevation
X Axis Title(PF)=Main Channel Distance
X Axis Title(XS)=Station
BEGIN DESCRIPTION:
UNT0509 IN WICK
END DESCRIPTION:
DSS Export Rating Curves= 0
DSS Export Rating Curve Sorted= 0
DSS Export Volume Flow Curves= 0
DXF Filename=UNT0509 IN WICK.
DXF OffsetX= 0
DXF OffsetY= 0
DXF ScaleX= 1
DXF ScaleY= 10

--- BRUSHYCREEKTRIB1.p01 (plan) ---

Plan Title=Multiple Run
Short Identifier=Multiple
Geom File=g01
Flow File=f01
Subcritical Flow
K Sum by GR= 0
Std Step Tol= 0.01
Critical Tol= 0.01
Num of Std Step Trials= 20
Max Error Tol= 0.3
Flow Tol Ratio= 0.001
Split Flow NTrial= 30
Split Flow Tol= 0.02
Split Flow Ratio= 0.02
Log Output Level= 0
Friction Slope Method= 1
Unsteady Friction Slope Method= 2
Unsteady Bridges Friction Slope Method= 1
Parabolic Critical Depth
Global Vel Dist=  1 , 1 , 1
Global Log Level= 0
CheckData=True
Encroach Param= -1, 0, 0, 0
BEGIN DESCRIPTION:
Multiple Run
END DESCRIPTION:

--- BRUSHYCREEKTRIB1.f01 (steady flow) ---

Flow Title=Multiple
Program Version=4.10
Number of Profiles= 7
Profile Names=10-year,25-year,50-year,1pct_min,100-year,1pct_plu,500-year
River Rch & RM=UNT0509 IN WICK,Reach-1         ,25608
     178     222     255     216     293     396     384
River Rch & RM=UNT0509 IN WICK,Reach-1         ,21361
     293     378     445     385     520     704     711
River Rch & RM=UNT0509 IN WICK,Reach-1         ,18828
     439     579     691     604     817    1105    1146
River Rch & RM=UNT0509 IN WICK,Reach-1         ,12246
     607     815     983     868    1174    1587    1679
River Rch & RM=UNT0509 IN WICK,Reach-1         ,7457
     820    1119    1365    1217    1646    2227    2403
River Rch & RM=UNT0509 IN WICK,Reach-1         ,6044
     923    1264    1545    1381    1867    2525    2735
River Rch & RM=BRUSHYCRTR10,Reach-1         ,25608
     178     222     255     216     293     396     384
River Rch & RM=BRUSHYCRTR10,Reach-1         ,21361
     293     378     445     385     520     704     711
River Rch & RM=BRUSHYCRTR10,Reach-1         ,18828
     439     579     691     604     817    1105    1146
River Rch & RM=BRUSHYCRTR10,Reach-1         ,12246
     607     815     983     868    1174    1587    1679
River Rch & RM=BRUSHYCRTR10,Reach-1         ,7457
     820    1119    1365    1217    1646    2227    2403
River Rch & RM=BRUSHYCRTR10,Reach-1         ,6044
     923    1264    1545    1381    1867    2525    2735
Boundary for River Rch & Prof#=BRUSHYCRTR10,Reach-1         , 1
Up Type= 0
Dn Type= 3
Dn Slope=0.005
Boundary for River Rch & Prof#=BRUSHYCRTR10,Reach-1         , 2
Up Type= 0
Dn Type= 3
Dn Slope=0.005
Boundary for River Rch & Prof#=BRUSHYCRTR10,Reach-1         , 3
Up Type= 0
Dn Type= 3
Dn Slope=0.005
Boundary for River Rch & Prof#=BRUSHYCRTR10,Reach-1         , 4
Up Type= 0
Dn Type= 3
Dn Slope=0.005
Boundary for River Rch & Prof#=BRUSHYCRTR10,Reach-1         , 5
Up Type= 0
Dn Type= 3
Dn Slope=0.005
Boundary for River Rch & Prof#=BRUSHYCRTR10,Reach-1         , 6
Up Type= 0
Dn Type= 3
Dn Slope=0.005
Boundary for River Rch & Prof#=BRUSHYCRTR10,Reach-1         , 7
Up Type= 0
Dn Type= 3
Dn Slope=0.005
DSS Import GetInterval= 0
DSS Import GetPeak= 0
DSS Import FillOption= 0

--- BRUSHYCREEKTRIB1.g01 (geometry) ---

Geom Title=Existing Conditions
Program Version=4.10

River Reach=BRUSHYCRTR10    ,Reach-1
Reach XY= 30
      3571222.41     10235994.45      3572265.75     10235111.42
       3573385.9     10235418.05      3574174.76     10234886.49
      3574655.25     10235085.88      3574901.81     10234786.85
      3574710.44     10234587.85      3575241.73     10234656.74
      3575708.33     10234313.37      3575507.24      10233979.1
      3575672.02     10233692.56      3575993.93     10233895.87
      3576089.48      10233551.8      3575739.47     10233479.06
      3575755.86     10232862.93      3576051.36     10232726.98
      3575754.63     10232467.38      3576144.02     10232205.27
      3576017.59     10231816.12      3576307.44     10231468.81
      3576971.33     10231464.65      3577781.87     10230882.94
      3578050.08     10231128.09      3578413.17     10230695.03
      3578678.29     10230843.75      3579160.28     10229719.48
       3579637.2     10229803.74      3580478.33      10228243.8
       3582157.2     10228161.71      3582462.11     10227211.64

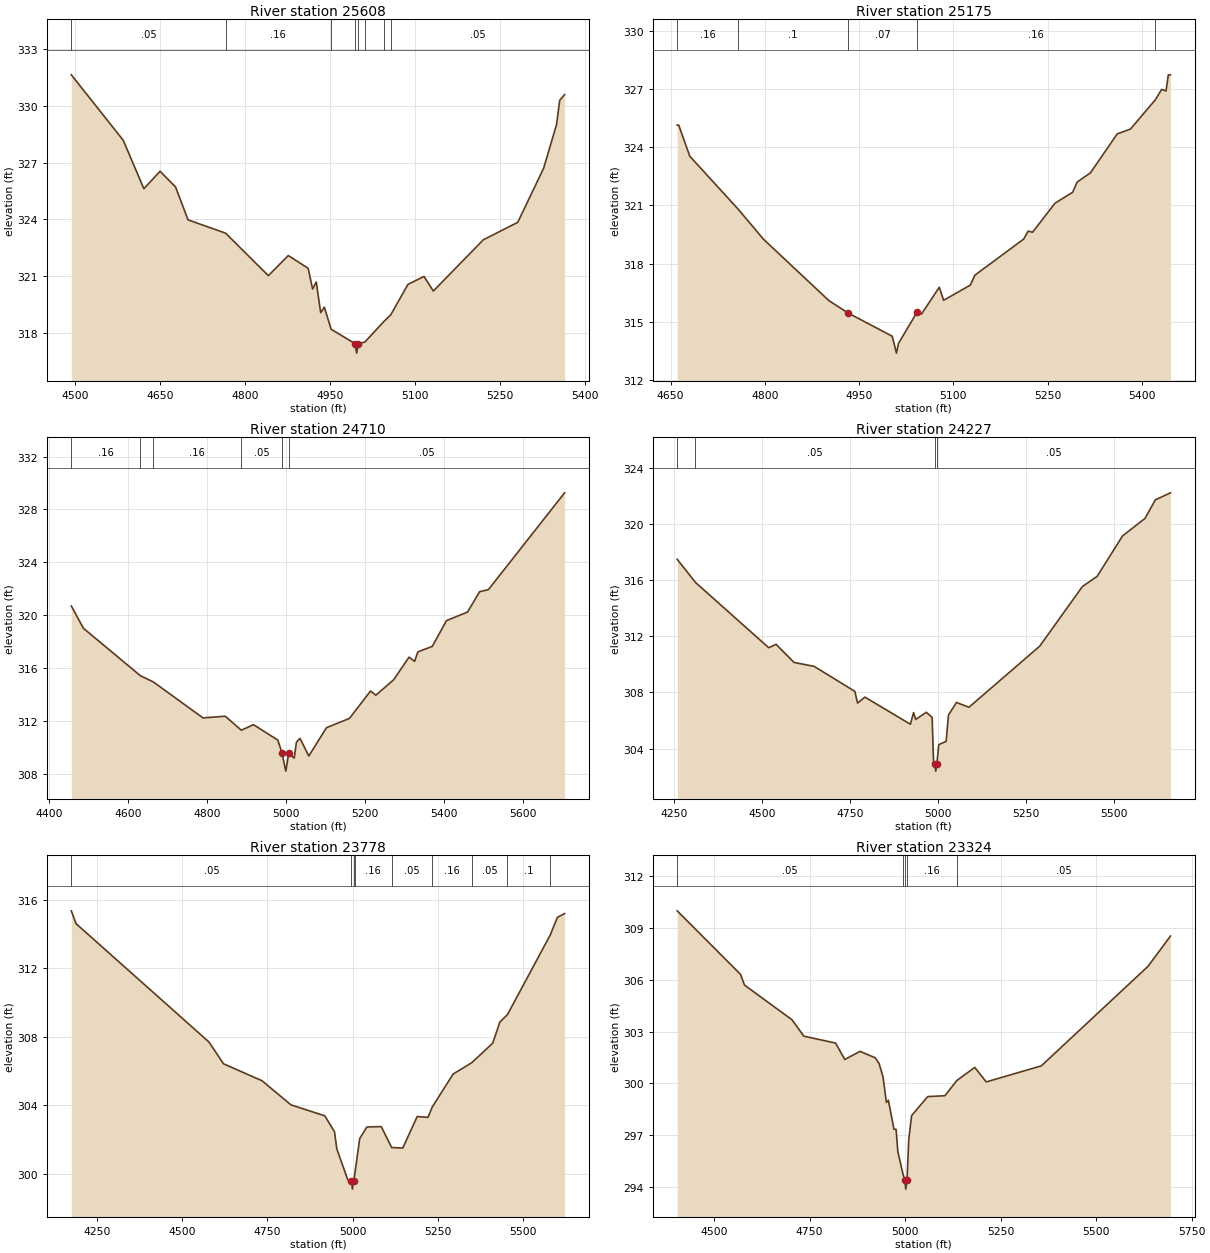
Type RM Length L Ch R = 1 ,25608   ,433,433,433
BEGIN DESCRIPTION:
UNT0509 IN WICK 31.0
END DESCRIPTION:
XS GIS Cut Line= 3
       3571692.1     10236191.64      3571351.32     10235786.12
      3571042.11     10235641.64
#Sta/Elev= 30
  4493.7  331.62  4585.4  328.17  4621.8  325.62  4650.4  326.54  4677.8  325.71
  4699.8  323.98  4766.1  323.28  4841.6  321.04  4876.8   322.1  4911.9  321.43
  4919.7  320.34  4926.2  320.71    4934  319.09  4940.5  319.38  4952.4  318.22
  4994.7  317.46  4997.5  316.96  5000.7  317.46  5011.9  317.54    5046  318.64
  5057.8  318.98  5088.1  320.58  5116.5     321  5132.9  320.23  5221.2  322.93
    5282  323.85  5327.7   326.7  5350.5     329    5356  330.27  5364.7  330.58
#Mann= 8 ,-1 , 0
  4493.7     .05       0  4766.1     .16       0  4952.4     .05       0
  4994.7    .035       0  5000.7     .05       0  5011.9     .16       0
    5046      .1       0  5057.8     .05       0
Bank Sta=4994.7,5000.7
XS Rating Curve= 0 ,0
Exp/Cntr=0.3,0.1

Type RM Length L Ch R = 1 ,25175   ,465,465,465
BEGIN DESCRIPTION:
UNT0509 IN WICK 30.0
END DESCRIPTION:
XS GIS Cut Line= 3
       3571742.1     10235891.63      3571704.18     10235542.63
      3571392.13     10235241.66
#Sta/Elev= 30
  4660.6  325.13  4663.1  325.13  4680.7  323.53  4757.8   320.8  4797.9  319.26
    4902   316.1  4932.2  315.47  5002.6  314.27  5009.4   313.4  5012.6   313.9
  5042.2  315.51  5049.2  315.41  5077.5  316.79  5084.4  316.12  5126.9   316.9
  5134.1  317.41  5211.8  319.27    5219  319.68  5225.9  319.62  5261.4  321.11
  5289.7  321.68  5296.7   322.2    5318  322.68  5360.5  324.68  5381.6  324.93
  5421.3  326.44  5431.2  326.97  5438.2  326.89  5441.8  327.72  5445.2  327.72
#Mann= 5 ,-1 , 0
  4660.6     .16       0  4757.8      .1       0  4932.2     .07       0
  5042.2     .16       0  5421.3      .1       0
Bank Sta=4932.2,5042.2
XS Rating Curve= 0 ,0
Exp/Cntr=0.3,0.1

Type RM Length L Ch R = 1 ,24710   ,483,483,483
BEGIN DESCRIPTION:
UNT0509 IN WICK 29.0
END DESCRIPTION:
XS GIS Cut Line= 3
      3571942.12      10235841.6      3572066.16     10235303.05
       3571442.1     10234991.64
#Sta/Elev= 30
  4455.4  320.69  4486.1     319  4630.3  315.41    4663  314.94  4789.2  312.21
  4845.3  312.34  4886.3  311.28  4917.1   311.7  4978.7  310.53    4989  309.59
    4999  308.18  5006.2  309.53  5020.3  309.17  5025.9  310.38  5034.9  310.66
  5057.3  309.33    5102  311.47  5160.1  312.17  5213.8  314.25  5227.2  313.93
    5272  315.09  5311.2  316.81  5325.5   316.5  5333.5  317.21  5370.2  317.63
  5406.2  319.58  5459.6  320.23  5490.1  321.77  5512.5  321.93  5705.5  329.26
#Mann= 6 ,-1 , 0
  4455.4     .16       0  4630.3     .05       0    4663     .16       0
  4886.3     .05       0    4989     .03       0  5006.2     .05       0
Bank Sta=4989,5006.2
XS Rating Curve= 0 ,0
Exp/Cntr=0.3,0.1

Type RM Length L Ch R = 1 ,24227   ,449,449,449
BEGIN DESCRIPTION:
UNT0509 IN WICK 28.0
END DESCRIPTION:
XS GIS Cut Line= 3
      3572042.12     10235791.63      3572442.11     10235191.64
      3572042.08     10234641.61
#Sta/Elev= 30
  4259.5  317.49  4311.4  315.84  4519.4  311.19  4540.4  311.43  4591.5  310.14
  4648.6  309.86  4764.3  308.08  4771.8  307.25  4792.8  307.67    4922  305.74
    4931  306.57    4937  306.08  4967.1  306.59  4983.7  306.23  4987.9  302.94
  4991.1   302.9  4993.9   302.4  4997.1   302.9  5002.6  304.29  5023.5  304.52
  5030.1  306.39  5052.8  307.29  5088.4  306.95  5289.3   311.3  5410.7  315.55
  5452.4  316.27  5524.6  319.15  5588.4   320.4  5617.8  321.72  5660.7  322.22
#Mann= 4 ,-1 , 0
  4259.5     .16       0  4311.4     .05       0  4991.1     .03       0
  4997.1     .05       0
Bank Sta=4991.1,4997.1
XS Rating Curve= 0 ,0
Exp/Cntr=0.3,0.1

Type RM Length L Ch R = 1 ,23778   ,454,454,454
BEGIN DESCRIPTION:
UNT0509 IN WICK 27.0
END DESCRIPTION:
XS GIS Cut Line= 3
      3572292.11     10235891.64      3572842.11     10235291.64
       3572642.1     10234691.63
#Sta/Elev= 30
  4175.4  315.34  4189.3  314.59    4579  307.68  4621.5  306.41  4734.4  305.42
  4819.5  304.01  4918.7  303.37  4947.1  302.44  4953.9  301.44  4985.9  299.64
  4996.9  299.59  4999.6  299.09  5002.9  299.59  5006.1   299.9    5021  302.04
    5042  302.72  5084.2  302.74  5114.7  301.52  5147.4  301.49  5189.6  303.33
  5221.2  303.28  5233.6  303.88    5295  305.81  5349.4  306.47    5411  307.61
  5432.1  308.85  5454.3  309.28    5580  313.94  5600.7  314.96  5621.8  315.18
#Mann= 9 ,-1 , 0
  4175.4     .05       0  4996.9     .03       0  5002.9     .05       0
  5006.1     .16       0  5114.7     .05       0  5233.6     .16       0
  5349.4     .05       0  5454.3      .1       0    5580     .05       0
Bank Sta=4996.9,5002.9
XS Rating Curve= 0 ,0
Exp/Cntr=0.3,0.1

Type RM Length L Ch R = 1 ,23324   ,530,530,530
BEGIN DESCRIPTION:
UNT0509 IN WICK 26.0
END DESCRIPTION:
XS GIS Cut Line= 3
      3573092.12     10235991.59      3573242.11     10235441.64
      3572842.13     10234841.68
#Sta/Elev= 30
  4403.4     310  4569.2  306.32  4579.6   305.7  4703.9  303.69    4735  302.74
    4818  302.34  4842.1  301.39  4881.9  301.86  4921.6  301.49    4932  301.15
  4942.3  300.36    4951   298.9  4956.2  299.03  4970.8  297.35  4976.4  297.35
  4980.9  296.06  4993.5  294.84    4999  294.38  5001.7  293.88    5005  294.38
  5009.5  296.76    5017  298.14  5059.1  299.24  5104.1  299.29  5135.7  300.18
  5182.3  300.93  5212.3  300.09  5356.5  301.02    5636  306.79  5694.5  308.54
#Mann= 5 ,-1 , 0
  4403.4     .05       0  4993.5     .16       0    4999     .07       0
    5005     .16       0  5135.7     .05       0
Bank Sta=4999,5005
XS Rating Curve= 0 ,0
Exp/Cntr=0.3,0.1

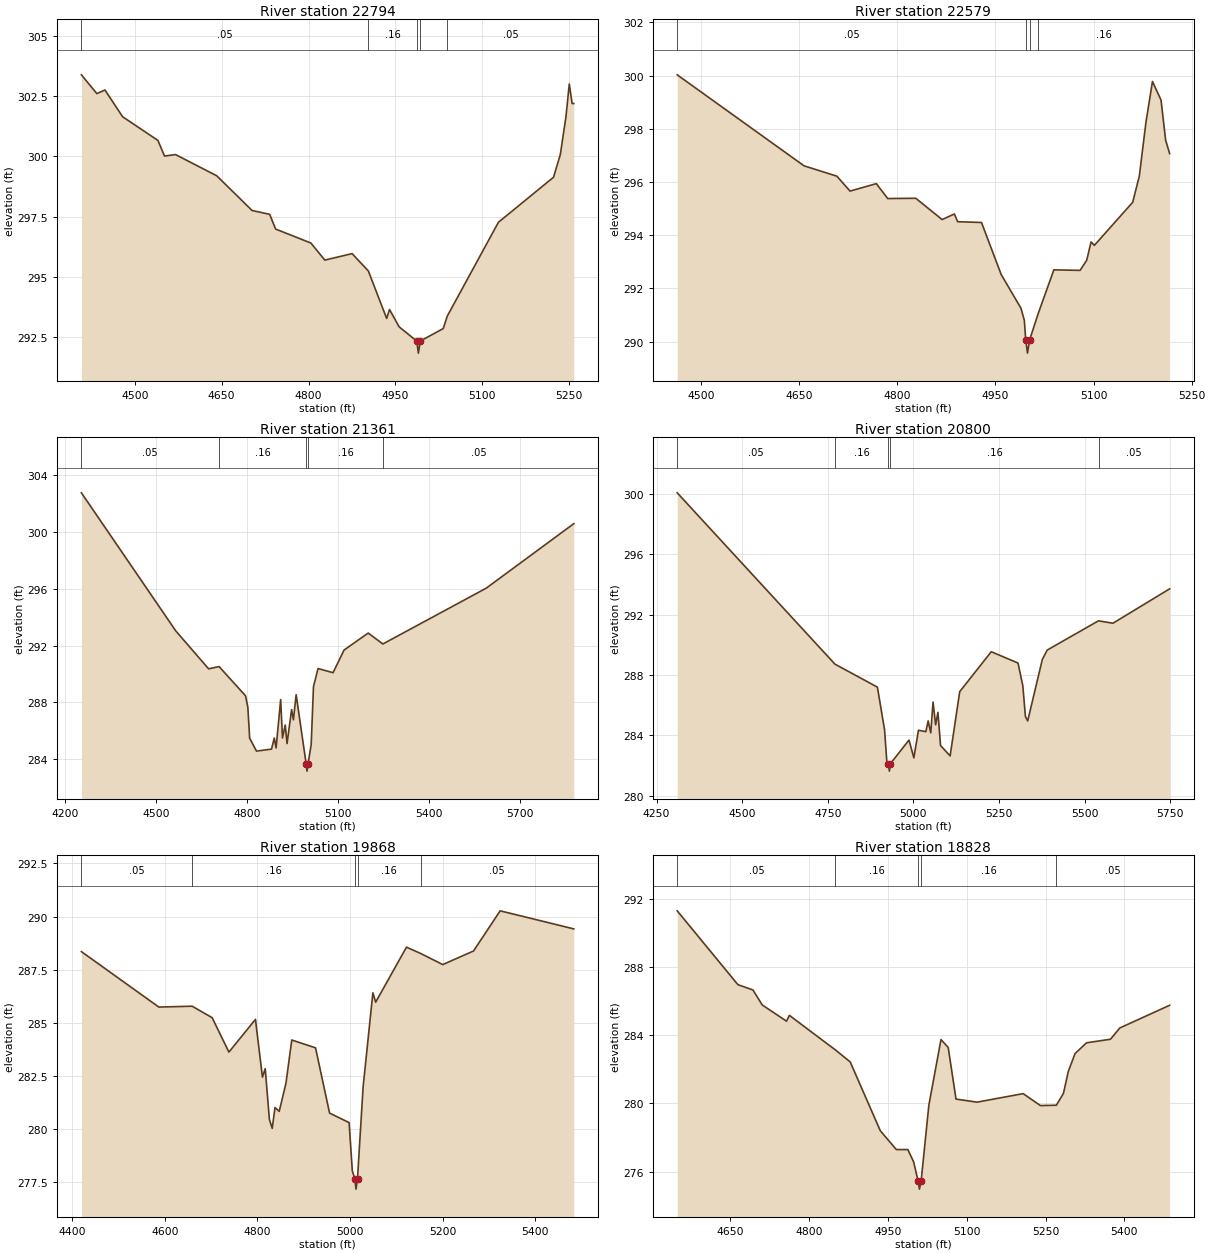
Type RM Length L Ch R = 1 ,22794   ,215,215,215
BEGIN DESCRIPTION:
UNT0509 IN WICK 25.0
END DESCRIPTION:
XS GIS Cut Line= 3
       3573492.1     10235741.66      3573592.11     10235191.64
      3573442.09     10234941.62
#Sta/Elev= 30
  4407.7  303.38  4434.4   302.6  4448.4  302.75  4478.9  301.64  4539.8  300.66
  4551.3  300.01  4570.3  300.07  4641.5  299.19  4702.5  297.75    4733  297.59
  4743.1  296.98  4804.1   296.4  4828.2  295.69  4875.3  295.96  4903.4  295.24
    4935  293.27    4940  293.64  4956.6  292.92  4987.1  292.33  4989.8  291.83
  4993.1  292.33  5032.8  292.85  5039.8  293.37  5128.1  297.26  5223.3  299.13
    5235  300.07  5244.7  301.63  5250.5     303  5255.4  302.19  5258.3  302.19
#Mann= 5 ,-1 , 0
  4407.7     .05       0  4903.4     .16       0  4987.1     .07       0
  4993.1     .16       0  5039.8     .05       0
Bank Sta=4987.1,4993.1
XS Rating Curve= 0 ,0
Exp/Cntr=0.3,0.1

Type RM Length L Ch R = 1 ,22579   ,1218,1218,1218
BEGIN DESCRIPTION:
UNT0509 IN WICK 24.0
END DESCRIPTION:
XS GIS Cut Line= 2
      3573685.75      10235684.5      3573758.56     10234935.53
#Sta/Elev= 30
  4463.7  300.03  4657.5  296.61  4707.7  296.22  4727.8  295.66    4768  295.94
  4785.4  295.38  4828.3  295.39  4868.5  294.59  4887.3   294.8  4892.3  294.51
  4928.7  294.48  4958.9  292.52    4989  291.26  4994.2   290.8  4996.3  290.07
    4999  289.57  5002.3  290.07  5015.7  291.08  5039.3   292.7  5079.4  292.68
  5089.5  293.06  5096.2  293.75  5101.2  293.62  5159.8  295.24  5169.9  296.22
  5179.9  298.22    5190  299.78  5203.1  299.08  5210.1  297.58  5216.2  297.07
#Mann= 4 ,-1 , 0
  4463.7     .05       0  4996.3     .03       0  5002.3     .05       0
  5015.7     .16       0
Bank Sta=4996.3,5002.3
XS Rating Curve= 0 ,0
Exp/Cntr=0.3,0.1

Type RM Length L Ch R = 1 ,21361   ,561,561,561
BEGIN DESCRIPTION:
UNT0509 IN WICK 23.0
END DESCRIPTION:
XS GIS Cut Line= 3
      3574742.13     10235641.68      3574342.11     10235041.64
      3573842.13     10234291.68
#Sta/Elev= 30
  4254.5  302.75  4565.5  293.03  4673.7  290.36  4708.2  290.52  4795.4  288.46
  4802.9  287.66  4808.9  285.48  4831.4  284.57    4881  284.71    4890  285.49
    4896  284.79  4911.1   288.2  4917.1  285.49  4926.1  286.41  4932.1   285.1
  4947.1  287.49  4953.1  286.77  4962.1  288.54  4995.2  283.66  4997.9  283.16
  5001.2  283.66  5011.7  285.04  5019.2  289.11  5034.2  290.38  5083.8  290.09
  5119.9  291.68  5199.5  292.88  5247.9  292.11  5588.6  296.04    5877  300.58
#Mann= 5 ,-1 , 0
  4254.5     .05       0  4708.2     .16       0  4995.2     .07       0
  5001.2     .16       0  5247.9     .05       0
Bank Sta=4995.2,5001.2
XS Rating Curve= 0 ,0
Exp/Cntr=0.3,0.1

Type RM Length L Ch R = 1 ,20800   ,932,932,932
BEGIN DESCRIPTION:
UNT0509 IN WICK 22.0
END DESCRIPTION:
XS GIS Cut Line= 3
      3574868.04      10235569.9      3574873.25     10235095.93
      3574243.02     10234366.74
#Sta/Elev= 30
  4310.5  300.08  4770.9  288.72  4895.1  287.19    4916  284.35  4922.6  282.25
  4927.2  282.12    4930  281.62  4933.2  282.12  4987.3  283.68  5001.5   282.5
  5014.9  284.33  5036.6  284.24  5043.2  284.95  5050.9  284.16  5057.5   286.2
  5065.1  284.69  5071.8  285.52  5079.4  283.32  5107.4  282.63  5135.4  286.89
  5227.5  289.54  5305.6  288.79  5319.7  287.28  5327.3  285.24  5333.9  284.95
  5376.7  289.03  5390.9  289.65  5540.7  291.59  5582.9  291.43  5748.3  293.71
#Mann= 5 ,-1 , 0
  4310.5     .05       0  4770.9     .16       0  4927.2     .07       0
  4933.2     .16       0  5540.7     .05       0
Bank Sta=4927.2,4933.2
XS Rating Curve= 0 ,0
Exp/Cntr=0.3,0.1

Type RM Length L Ch R = 1 ,19868   ,1040,1040,1040
BEGIN DESCRIPTION:
UNT0509 IN WICK 21.0
END DESCRIPTION:
XS GIS Cut Line= 2
      3575292.08     10234991.61      3574711.77      10234101.1
#Sta/Elev= 30
  4420.1  288.35  4587.2  285.74  4659.2  285.78  4702.3  285.24  4738.5  283.62
  4795.8  285.16  4810.9  282.44  4816.9  282.84  4825.9  280.45    4832  280.03
    4838  281.01  4847.1  280.83  4861.7  282.16  4874.2  284.19  4925.5  283.82
  4955.8  280.75    4998   280.3  5004.9  278.03  5010.1  277.67  5012.9  277.17
  5016.1  277.67  5028.2  281.98  5049.3  286.41  5055.3  285.97  5121.8  288.56
  5152.7  288.26  5200.2  287.74  5266.6  288.38    5324  290.27    5483  289.42
#Mann= 5 ,-1 , 0
  4420.1     .05       0  4659.2     .16       0  5010.1     .07       0
  5016.1     .16       0  5152.7     .05       0
Bank Sta=5010.1,5016.1
XS Rating Curve= 0 ,0
Exp/Cntr=0.3,0.1

Type RM Length L Ch R = 1 ,18828   ,520,520,520
BEGIN DESCRIPTION:
UNT0509 IN WICK 20.0
END DESCRIPTION:
XS GIS Cut Line= 2
      3575972.19     10234554.25      3575118.02     10234168.83
#Sta/Elev= 30
  4549.1  291.29  4664.6  286.96  4693.2  286.65  4710.9  285.77  4757.1  284.82
  4762.6  285.16  4850.3  283.13  4878.3  282.43  4935.5   278.4  4966.1  277.29
    4988  277.29    4999  276.57  5007.4  275.47  5010.1  274.97  5013.4  275.47
    5028  279.89  5051.1  283.74  5064.8  283.28  5079.7  280.25  5119.7  280.07
  5207.4  280.57  5240.4  279.87  5270.7  279.89  5284.2  280.59  5293.4  281.87
  5306.2  282.92  5328.1  283.55  5373.7  283.76  5391.4  284.42  5486.2  285.75
#Mann= 5 ,-1 , 0
  4549.1     .05       0  4850.3     .16       0  5007.4     .07       0
  5013.4     .16       0  5270.7     .05       0
Bank Sta=5007.4,5013.4
XS Rating Curve= 0 ,0
Exp/Cntr=0.3,0.1

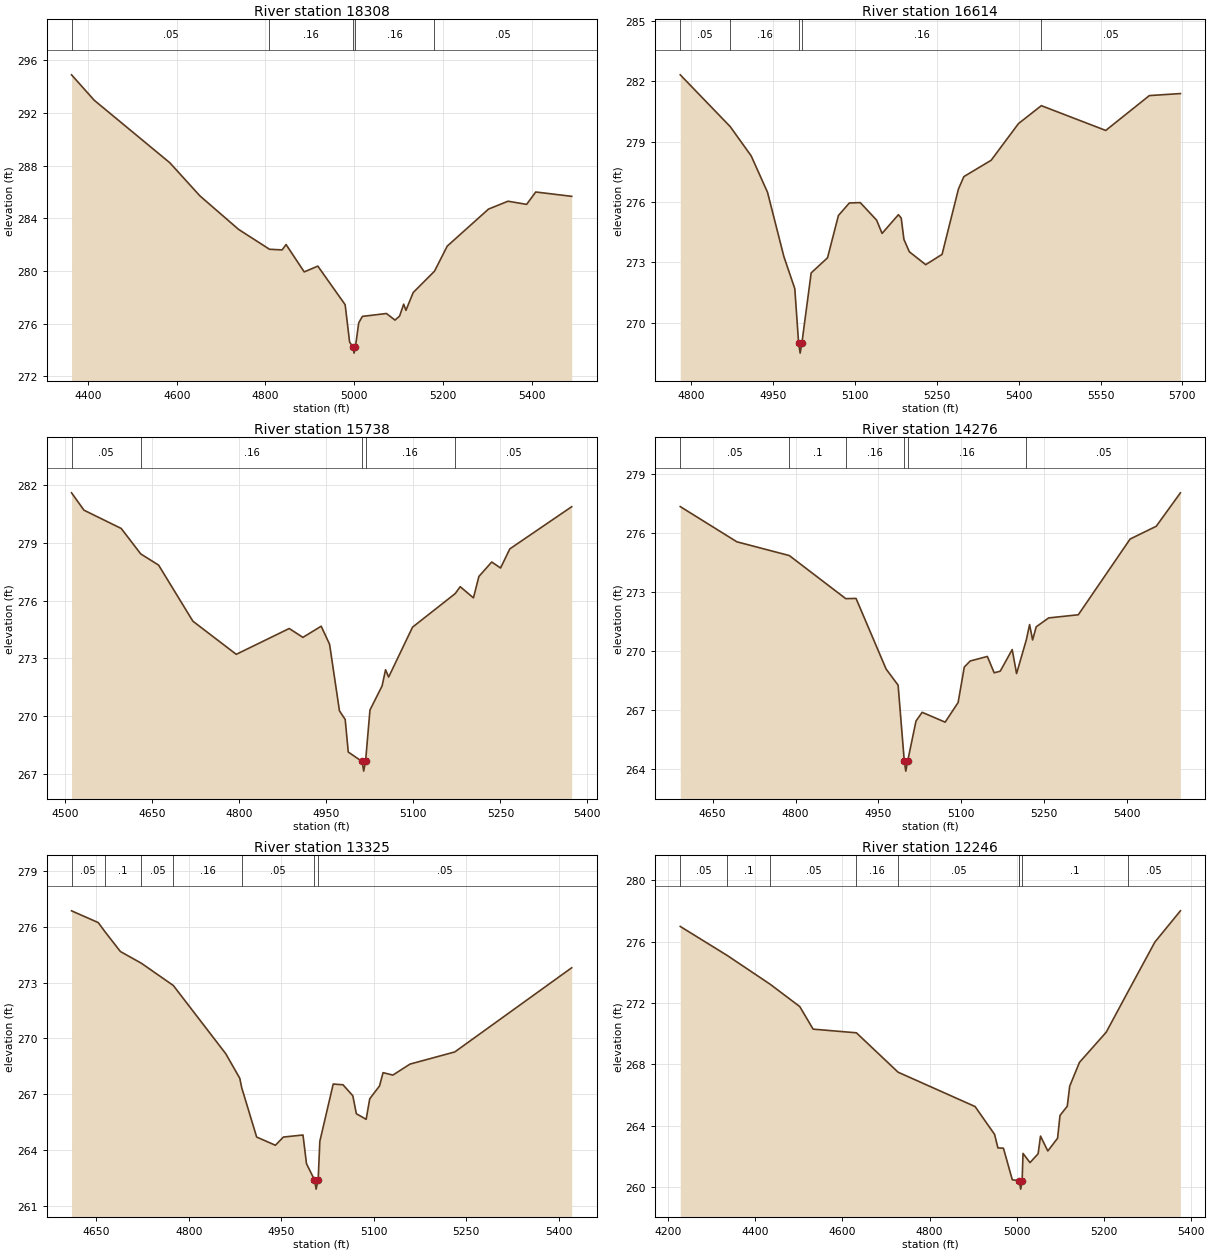
Type RM Length L Ch R = 1 ,18308   ,1694,1694,1694
BEGIN DESCRIPTION:
UNT0509 IN WICK 19.0
END DESCRIPTION:
XS GIS Cut Line= 3
      3576201.36     10234278.21      3575998.25     10234189.68
      3575112.85     10233996.97
#Sta/Elev= 30
  4362.7  294.91  4413.8  292.98  4584.3  288.23    4652  285.72  4739.3  283.17
    4809  281.66  4837.5  281.61  4846.4  282.02  4887.3  279.94    4918  280.38
  4979.6  277.45  4989.7   274.6  4996.9  274.27  4999.7  273.77  5002.9  274.27
  5010.2  276.07  5018.5  276.56  5072.7  276.78    5092  276.28  5102.3  276.58
  5111.6  277.49  5116.7  277.02    5133  278.37    5181  279.99  5209.8   281.9
  5302.8  284.71  5346.8  285.31  5388.8  285.07  5409.3  286.01  5490.4  285.68
#Mann= 5 ,-1 , 0
  4362.7     .05       0    4809     .16       0  4996.9     .07       0
  5002.9     .16       0    5181     .05       0
Bank Sta=4996.9,5002.9
XS Rating Curve= 0 ,0
Exp/Cntr=0.3,0.1

Type RM Length L Ch R = 1 ,16614   ,876,876,876
BEGIN DESCRIPTION:
UNT0509 IN WICK 18.0
END DESCRIPTION:
XS GIS Cut Line= 2
      3576292.11     10233591.64      3575375.18     10233580.33
#Sta/Elev= 30
  4779.4  282.31    4871  279.74  4909.4  278.29  4939.4  276.48  4969.4  273.29
  4989.4   271.7  4996.4     269  4999.2   268.5  5002.4     269  5019.4  272.48
  5049.4  273.23  5069.4  275.33  5089.4  275.95  5109.4  275.97  5139.4   275.1
  5149.4  274.44  5179.4  275.37  5184.5   275.2  5189.5  274.14  5199.4  273.53
  5229.4  272.89  5259.4   273.4  5289.4  276.64  5299.4  277.26  5349.4  278.07
  5399.5  279.89  5441.4  280.78  5559.5  279.55  5639.5  281.28  5696.4  281.38
#Mann= 5 ,-1 , 0
  4779.4     .05       0    4871     .16       0  4996.4     .07       0
  5002.4     .16       0  5441.4     .05       0
Bank Sta=4996.4,5002.4
XS Rating Curve= 0 ,0
Exp/Cntr=0.3,0.1

Type RM Length L Ch R = 1 ,15738   ,1462,1462,1462
BEGIN DESCRIPTION:
UNT0509 IN WICK 17.0
END DESCRIPTION:
XS GIS Cut Line= 3
      3576342.13     10233391.65      3575628.46     10233163.64
      3575515.49     10233168.77
#Sta/Elev= 30
  4510.6  281.59    4532  280.69  4596.3  279.74  4629.9  278.42  4660.7  277.84
  4719.8  274.93  4794.6  273.21  4885.9  274.55  4909.5  274.09    4941  274.67
  4955.5  273.73  4972.5  270.28  4982.4  269.83  4987.7  268.14  5011.5  267.65
  5014.3  267.15  5017.5  267.65  5025.1  270.32    5046  271.57    5052  272.41
  5057.3  272.03  5098.5  274.62    5172  276.36  5180.7  276.72  5203.5  276.14
  5212.9  277.25    5235     278  5250.3  277.69  5266.2  278.68  5372.9  280.87
#Mann= 5 ,-1 , 0
  4510.6     .05       0  4629.9     .16       0  5011.5     .07       0
  5017.5     .16       0    5172     .05       0
Bank Sta=5011.5,5017.5
XS Rating Curve= 0 ,0
Exp/Cntr=0.3,0.1

Type RM Length L Ch R = 1 ,14276   ,951,951,951
BEGIN DESCRIPTION:
UNT0509 IN WICK 16.0
END DESCRIPTION:
XS GIS Cut Line= 3
      3576392.08     10232441.65      3576090.13     10232508.75
      3575542.08     10232741.65
#Sta/Elev= 30
  4591.5  277.36  4693.9  275.57  4788.8  274.87  4890.9  272.68  4909.5  272.69
  4963.9   269.1  4985.6  268.28  4996.8  264.41  4999.5  263.91  5002.8  264.41
    5018  266.46  5029.1   266.9  5070.7   266.4  5094.2   267.4  5105.3   269.2
    5116  269.51  5147.1  269.74  5159.4  268.91  5170.3  268.99    5192  270.09
  5199.9  268.87  5217.5  270.58  5223.5  271.36  5228.9  270.58  5235.5  271.25
    5258   271.7  5311.6  271.86  5405.3  275.71  5452.6  276.36  5496.3  278.06
#Mann= 6 ,-1 , 0
  4591.5     .05       0  4788.8      .1       0  4890.9     .16       0
  4996.8     .07       0  5002.8     .16       0  5217.5     .05       0
Bank Sta=4996.8,5002.8
XS Rating Curve= 0 ,0
Exp/Cntr=0.3,0.1

Type RM Length L Ch R = 1 ,13325   ,1079,1079,1079
BEGIN DESCRIPTION:
UNT0509 IN WICK 14.0
END DESCRIPTION:
XS GIS Cut Line= 3
      3576349.82     10232393.49       3575820.3     10232094.01
      3575622.46     10232137.02
#Sta/Elev= 30
  4610.1  276.84  4653.4  276.21  4664.1  275.73  4689.3  274.66  4723.4  274.03
  4775.1  272.84  4860.2  269.18  4882.8  267.87    4886  267.36  4910.2  264.72
  4940.6  264.28  4953.5  264.72  4985.3  264.83    4991  263.29  5003.9  262.43
  5006.6  261.93  5009.9  262.43  5012.6  264.49  5034.3  267.56  5050.2  267.52
  5066.1  266.93  5071.8  265.97  5087.7  265.67  5093.5  266.77  5109.4  267.46
  5115.1  268.17    5131  268.04  5158.9  268.63  5231.4  269.28  5420.9  273.79
#Mann= 7 ,-1 , 0
  4610.1     .05       0  4664.1      .1       0  4723.4     .05       0
  4775.1     .16       0    4886     .05       0  5003.9     .03       0
  5009.9     .05       0
Bank Sta=5003.9,5009.9
XS Rating Curve= 0 ,0
Exp/Cntr=0.3,0.1

Type RM Length L Ch R = 1 ,12246   ,1122,1122,1122
BEGIN DESCRIPTION:
UNT0509 IN WICK 13.0
END DESCRIPTION:
XS GIS Cut Line= 3
      3576392.11     10232391.67      3576242.11     10231591.64
      3576092.09     10231291.62
#Sta/Elev= 30
  4227.2     277    4335  275.11  4434.3  273.22  4501.9  271.77  4532.5   270.3
    4632  270.06  4727.8  267.49  4904.7  265.25  4949.6  263.43  4957.2  262.55
  4969.9  262.53  4990.3  260.47  5005.5  260.41  5006.8  260.36  5009.5  259.86
  5012.8  260.36  5014.9  262.19    5031  261.59  5049.6  262.17  5055.1  263.32
  5071.9  262.35  5094.3  263.18  5099.9  264.67  5116.6  265.27  5122.2  266.58
  5144.6  268.13  5206.1   270.1  5255.9  272.73  5317.9  275.98  5376.6  278.02
#Mann= 9 ,-1 , 0
  4227.2     .05       0    4335      .1       0  4434.3     .05       0
    4632     .16       0  4727.8     .05       0  5005.5      .1       0
  5006.8     .03       0  5012.8      .1       0  5255.9     .05       0
Bank Sta=5006.8,5012.8
XS Rating Curve= 0 ,0
Exp/Cntr=0.3,0.1

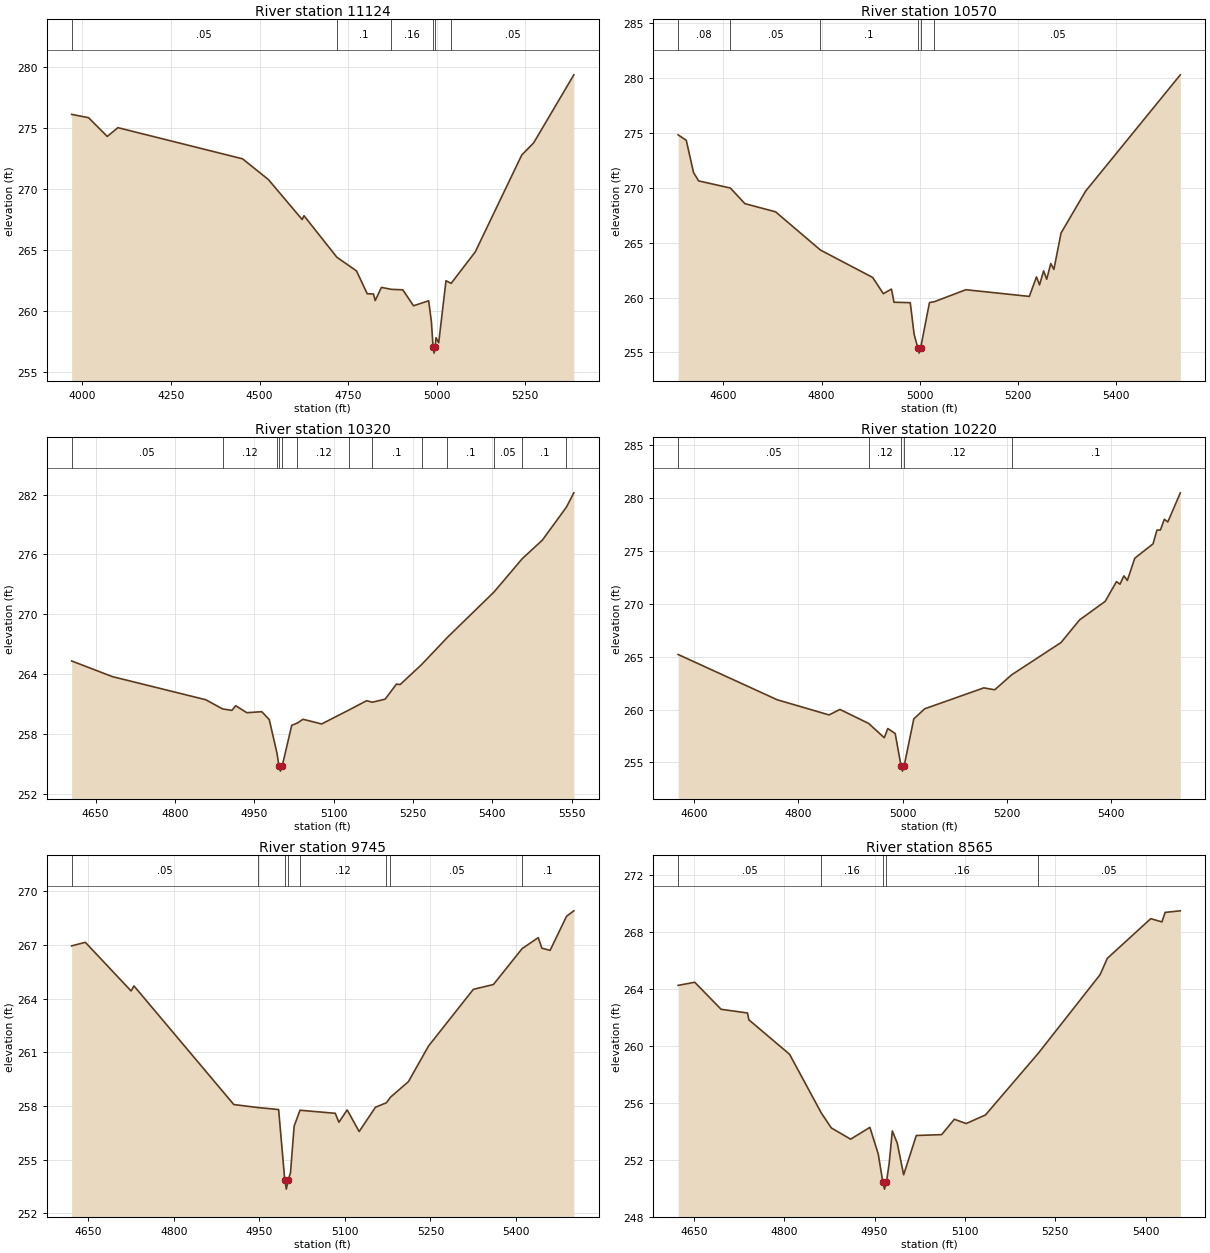
Type RM Length L Ch R = 1 ,11124   ,554,554,554
BEGIN DESCRIPTION:
UNT0509 IN WICK 11.0
END DESCRIPTION:
XS GIS Cut Line= 3
      3576692.11     10232341.63      3576792.11     10231341.64
       3576692.1     10230941.63
#Sta/Elev= 30
  3969.7  276.12  4017.4  275.85  4070.2  274.31  4100.3  275.03  4452.1  272.47
  4524.9  270.77  4620.4  267.48  4625.4   267.8  4718.1  264.39  4773.7  263.26
  4803.8  261.39  4821.4  261.37  4826.4  260.83    4844  261.91    4872  261.75
  4904.3  261.71  4934.5   260.4  4977.3  260.81    4985   259.1  4989.7  257.01
  4992.5  256.51  4995.7  257.01  4997.9  257.78  5005.6  257.36  5026.2  262.46
  5040.7  262.24  5108.7  264.82  5240.1  272.79  5273.6  273.78    5387  279.37
#Mann= 6 ,-1 , 0
  3969.7     .05       0  4718.1      .1       0    4872     .16       0
  4989.7     .07       0  4995.7     .16       0  5040.7     .05       0
Bank Sta=4989.7,4995.7
XS Rating Curve= 0 ,0
Exp/Cntr=0.3,0.1

Type RM Length L Ch R = 1 ,10570   ,250,250,250
BEGIN DESCRIPTION:
UNT0509 IN WICK 10.0
END DESCRIPTION:
XS GIS Cut Line= 3
      3577292.12     10231791.68      3577142.11     10231291.64
      3576842.08     10230891.61
#Sta/Elev= 30
  4508.1  274.83  4524.7  274.33  4539.5  271.39  4549.9  270.63  4614.5  269.98
  4643.9  268.56  4706.5  267.81  4797.7  264.33    4904  261.83  4925.8  260.35
  4942.3  260.77  4947.5  259.57  4980.6  259.53  4988.4  256.66  4995.8  255.43
  4998.6  254.93  5001.8  255.43  5019.7  259.54  5029.8  259.62  5093.7  260.71
  5222.9   260.1  5237.5  261.88  5243.7  261.15    5252  262.43  5258.3  261.67
  5266.6   263.1  5272.9  262.56  5287.5  265.88  5337.5   269.7  5530.2   280.3
#Mann= 6 ,-1 , 0
  4508.1     .08       0  4614.5     .05       0  4797.7      .1       0
  4995.8     .07       0  5001.8      .1       0  5029.8     .05       0
Bank Sta=4995.8,5001.8
XS Rating Curve= 0 ,0
Exp/Cntr=0.3,0.1

Type RM Length L Ch R = 1 ,10320   ,100,100,100
BEGIN DESCRIPTION:
Mapping XS 5237af07
END DESCRIPTION:
XS GIS Cut Line= 2
      3577604.17     10231508.09      3576945.75     10230823.68
#Sta/Elev= 30
  4604.6  265.32  4681.5  263.75  4858.2  261.43    4890  260.51  4907.6  260.36
  4914.8  260.83  4935.9  260.13  4964.2  260.23  4978.3  259.44  4992.9  256.08
  4996.7  254.77  4999.4  254.27  5002.7  254.77  5020.8  258.86  5031.7   259.1
  5042.1  259.47  5077.4     259  5129.7  260.42  5162.3  261.33  5173.4  261.18
  5197.5  261.49  5218.9     263  5225.8  262.95  5266.5  264.96  5315.1  267.68
  5403.3  272.23  5456.8  275.58  5494.7  277.43  5540.2  280.74  5554.3  282.18
#Mann= 13 ,-1 , 0
  4604.6     .05       0    4890     .12       0  4992.9     .05       0
  4996.7     .04       0  5002.7     .05       0  5031.7     .12       0
  5129.7     .05       0  5173.4      .1       0  5266.5     .05       0
  5315.1      .1       0  5403.3     .05       0  5456.8      .1       0
  5540.2     .05       0
Bank Sta=4996.7,5002.7
XS Rating Curve= 0 ,0
Exp/Cntr=0.3,0.1

Type RM Length L Ch R = 1 ,10220   ,475,475,475
BEGIN DESCRIPTION:
Mapping XS 58814ec8
END DESCRIPTION:
XS GIS Cut Line= 2
      3577695.27     10231477.66      3577048.59     10230761.54
#Sta/Elev= 30
  4568.8  265.21  4759.4  260.92  4858.8  259.49  4879.7  260.01    4935  258.68
  4964.9  257.33  4971.7   258.2  4985.9  257.73  4997.1  254.67  4999.8  254.17
  5003.1  254.67  5021.6  259.11  5042.6  260.07  5156.2  262.05  5177.2  261.87
  5209.5  263.28  5304.5  266.34  5340.1  268.48  5389.4  270.24  5411.1  272.11
  5417.8  271.86  5425.3  272.65    5432  272.22  5446.2  274.32  5481.3  275.68
  5488.8  276.98  5495.5  276.99    5503  278.01  5509.7  277.75  5533.7  280.51
#Mann= 5 ,-1 , 0
  4568.8     .05       0    4935     .12       0  4997.1     .07       0
  5003.1     .12       0  5209.5      .1       0
Bank Sta=4997.1,5003.1
XS Rating Curve= 0 ,0
Exp/Cntr=0.3,0.1

Type RM Length L Ch R = 1 ,9745    ,1180,1180,1180
BEGIN DESCRIPTION:
UNT0509 IN WICK 9.0
END DESCRIPTION:
XS GIS Cut Line= 3
      3577825.51     10231395.19      3577864.57     10231204.25
      3577439.46     10230666.36
#Sta/Elev= 30
    4621  266.95    4645  267.15  4725.2  264.43  4730.3  264.71  4905.3  258.08
  4947.8  257.91  4983.9   257.8  4994.7  253.85  4997.4  253.35  5000.7  253.85
  5004.7  254.27  5011.1  256.87  5021.4  257.76  5083.2  257.59  5089.6  257.09
  5104.1  257.78  5125.1  256.57  5153.7  257.93    5173  258.18    5180  258.49
  5211.5  259.36  5246.7  261.35  5325.3  264.52  5360.5  264.79  5410.9   266.8
  5439.1  267.41  5445.5  266.82  5459.9   266.7  5488.8  268.61  5501.5  268.91
#Mann= 8 ,-1 , 0
    4621     .05       0  4947.8     .16       0  4994.7     .07       0
  5000.7     .16       0  5021.4     .12       0    5173     .16       0
    5180     .05       0  5410.9      .1       0
Bank Sta=4994.7,5000.7
XS Rating Curve= 0 ,0
Exp/Cntr=0.3,0.1

Type RM Length L Ch R = 1 ,8565    ,1108,1108,1108
BEGIN DESCRIPTION:
UNT0509 IN WICK 8.0
END DESCRIPTION:
XS GIS Cut Line= 3
      3578302.93     10231238.99      3578359.36     10231134.81
      3578138.55     10230455.06
#Sta/Elev= 30
  4624.1  264.25  4651.7  264.47  4695.4  262.57  4739.2  262.31  4741.5  261.83
    4809  259.41  4861.7  255.28  4878.3  254.23  4910.3  253.44  4942.3  254.27
  4956.2  252.39  4963.7  250.43  4966.5  249.93  4969.7  250.43  4974.2  251.71
  4979.5  254.02  4987.7  253.16  4998.3  250.94  5019.3   253.7  5061.3  253.76
  5082.4  254.84    5102  254.54    5134  255.14  5221.7  259.48  5324.2     265
  5336.2  266.15  5408.3  268.94  5426.8  268.71  5432.1  269.38  5457.3  269.49
#Mann= 5 ,-1 , 0
  4624.1     .05       0  4861.7     .16       0  4963.7     .07       0
  4969.7     .16       0  5221.7     .05       0
Bank Sta=4963.7,4969.7
XS Rating Curve= 0 ,0
Exp/Cntr=0.3,0.1

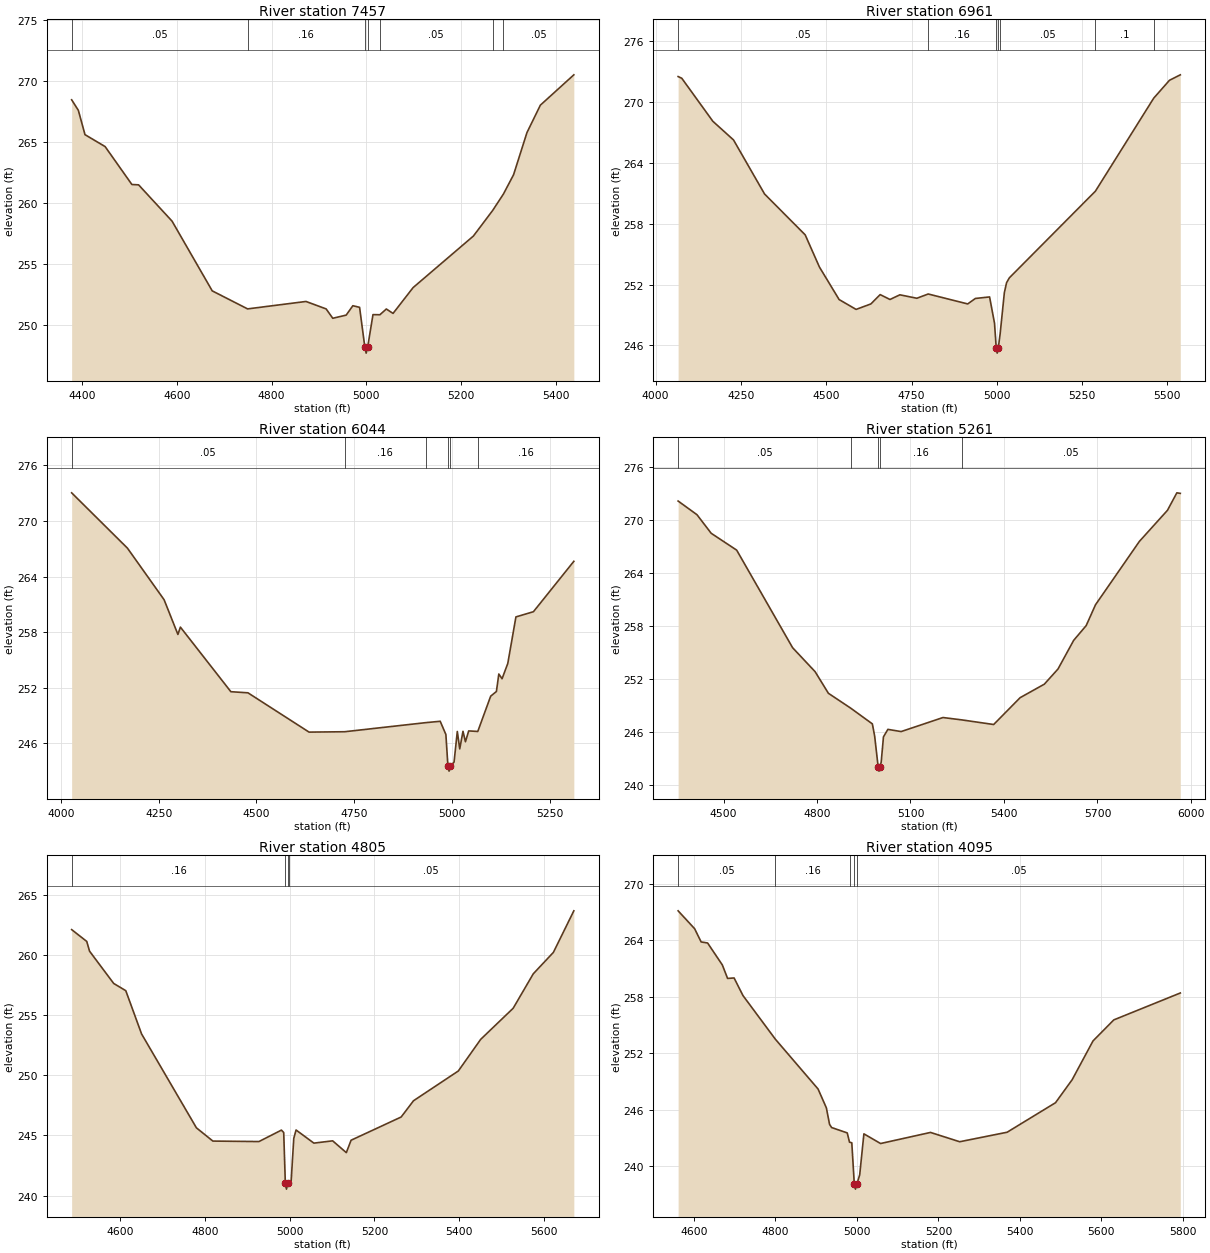
Type RM Length L Ch R = 1 ,7457    ,496,496,496
BEGIN DESCRIPTION:
UNT0509 IN WICK 7.0
END DESCRIPTION:
XS GIS Cut Line= 3
      3579142.08     10231041.62      3578742.11     10230641.64
      3578392.12     10230291.66
#Sta/Elev= 30
  4377.8  268.46  4391.9   267.6    4406   265.6  4448.5  264.62    4505  261.51
  4519.2  261.48  4589.9   258.5  4674.7  252.78  4749.4   251.3  4872.7  251.91
  4915.2   251.3  4929.3  250.53  4957.6  250.79  4971.7  251.56  4985.9  251.43
    4997  248.17  4999.8  247.67    5003  248.17  5014.2  250.83  5028.8  250.82
  5042.4  251.29  5056.6  250.93    5099  253.05  5226.3  257.28  5266.8  259.37
  5289.6  260.72  5311.1  262.31  5339.4  265.77  5367.7  268.02  5438.4  270.51
#Mann= 7 ,-1 , 0
  4377.8     .05       0  4749.4     .16       0    4997     .07       0
    5003     .16       0  5028.8     .05       0  5266.8     .16       0
  5289.6     .05       0
Bank Sta=4997,5003
XS Rating Curve= 0 ,0
Exp/Cntr=0.3,0.1

Type RM Length L Ch R = 1 ,6961    ,917,917,917
BEGIN DESCRIPTION:
UNT0509 IN WICK 6.0
END DESCRIPTION:
XS GIS Cut Line= 4
      3579296.87     10231052.37      3579244.78     10230696.44
      3578554.67     10230153.91      3578320.27     10230158.25
#Sta/Elev= 30
  4065.8  272.51  4076.6  272.34  4167.6   268.1  4228.2  266.26  4319.2  260.93
  4438.3   256.9    4480  253.73  4537.8  250.52  4587.5  249.55  4630.8  250.09
    4658  251.01  4686.9  250.53  4715.8  250.99  4765.5  250.65  4798.9  251.07
  4914.6  250.09  4937.2  250.63  4978.8  250.78  4993.2  248.19  4998.3  245.74
  5001.1  245.24  5004.3  245.74  5009.8  247.17  5022.1  251.21  5028.5  252.18
  5036.6  252.66    5289  261.21  5459.9  270.38    5506  272.14  5537.8  272.68
#Mann= 7 ,-1 , 0
  4065.8     .05       0  4798.9     .16       0  4998.3     .07       0
  5004.3     .16       0  5009.8     .05       0    5289      .1       0
  5459.9     .05       0
Bank Sta=4998.3,5004.3
XS Rating Curve= 0 ,0
Exp/Cntr=0.3,0.1

Type RM Length L Ch R = 1 ,6044    ,783,783,783
BEGIN DESCRIPTION:
UNT0509 IN WICK 5.0
END DESCRIPTION:
XS GIS Cut Line= 3
      3579942.09     10230341.63       3579032.1     10229654.77
      3578888.88     10229650.43
#Sta/Elev= 30
  4027.6  273.04  4170.2  267.07  4263.8  261.51  4299.2  257.76  4305.5  258.55
  4434.5  251.58  4478.2  251.46  4634.3  247.22  4725.1  247.26  4932.3  248.24
  4969.5  248.39    4984  246.96  4989.3  243.51  4992.1  243.01  4995.3  243.51
  5004.9  243.99  5013.2  247.29  5019.4  245.41  5027.7  247.31    5034  246.18
  5042.3  247.35  5065.5  247.29  5098.5   251.1  5113.1   251.6  5119.3  253.49
  5127.6  252.98  5142.2  254.63    5163  259.65  5207.7  260.21    5311  265.65
#Mann= 6 ,-1 , 0
  4027.6     .05       0  4725.1     .16       0  4932.3     .12       0
  4989.3     .07       0  4995.3     .12       0  5065.5     .16       0
Bank Sta=4989.3,4995.3
XS Rating Curve= 0 ,0
Exp/Cntr=0.3,0.1

Type RM Length L Ch R = 1 ,5261    ,456,456,456
BEGIN DESCRIPTION:
UNT0509 IN WICK 4.0
END DESCRIPTION:
XS GIS Cut Line= 4
      3580012.99     10230301.45      3579851.82     10229961.06
      3579253.46      10229398.7      3578841.09     10229433.42
#Sta/Elev= 30
  4354.3  272.15  4414.9   270.6  4460.4   268.5  4542.2  266.59  4721.7  255.54
    4794  252.82  4836.5  250.38  4908.3  248.69  4977.7  246.91    4985  245.54
  4996.2  242.06  4998.9  241.56  5002.2  242.06    5006  242.58  5013.3  245.44
  5027.5  246.29    5070  246.04  5204.3  247.63  5265.2  247.36    5367  246.84
  5451.9  249.88  5529.6  251.41  5573.5  253.13  5623.7  256.37  5663.8  258.04
  5693.9  260.41  5834.4  267.57  5924.7   271.1  5954.8  273.08  5965.9  273.02
#Mann= 5 ,-1 , 0
  4354.3     .05       0  4908.3     .16       0  4996.2     .07       0
  5002.2     .16       0  5265.2     .05       0
Bank Sta=4996.2,5002.2
XS Rating Curve= 0 ,0
Exp/Cntr=0.3,0.1

Type RM Length L Ch R = 1 ,4805    ,710,710,710
BEGIN DESCRIPTION:
UNT0509 IN WICK 3.0
END DESCRIPTION:
XS GIS Cut Line= 3
      3580142.08     10229641.61      3580050.15     10229536.55
      3579088.52      10229129.6
#Sta/Elev= 30
  4486.3  262.09  4521.9  261.11  4528.5   260.3  4585.4  257.62  4613.9  257.02
  4651.1  253.43  4780.4  245.63  4819.2  244.53  4927.8  244.49  4980.8  245.44
  4986.2  245.24    4990  241.04  4992.7  240.54    4996  241.04  4998.1  241.09
  5003.8  241.24  5009.9  244.75  5015.3  245.45  5057.3  244.36  5101.6  244.55
  5133.8  243.57    5145   244.6  5263.1  246.53  5292.2  247.88  5397.8  250.35
  5450.6  252.98  5527.1  255.56  5574.5  258.42  5621.9   260.2  5670.1  263.65
#Mann= 4 ,-1 , 0
  4486.3     .16       0    4990    .035       0    4996     .16       0
  4998.1     .05       0
Bank Sta=4990,4996
XS Rating Curve= 0 ,0
Exp/Cntr=0.3,0.1

Type RM Length L Ch R = 1 ,4095    ,382,382,382
BEGIN DESCRIPTION:
UNT0509 IN WICK 2.0
END DESCRIPTION:
XS GIS Cut Line= 3
      3580364.58     10229316.26      3580230.02     10229077.52
      3579292.49     10228877.86
#Sta/Elev= 30
  4561.2  267.15  4601.7  265.25  4617.7  263.84  4633.6  263.73  4669.8  261.39
  4682.6  259.96  4698.6  260.01  4720.2  258.15  4799.8   253.5  4904.7   248.2
  4925.1  246.19  4932.9  244.44    4938   244.1  4976.3  243.53  4981.9  242.54
  4987.5  242.48  4993.7  238.05  4996.5  237.55  4999.7  238.05  5006.9  239.07
  5017.2  243.43  5058.1   242.4  5180.7  243.58  5252.3  242.59  5368.7   243.6
  5487.5  246.74  5528.4  249.19  5579.5  253.31  5630.6  255.55  5793.8  258.41
#Mann= 5 ,-1 , 0
  4561.2     .05       0  4799.8     .16       0  4981.9     .05       0
  4993.7    .035       0  4999.7     .05       0
Bank Sta=4993.7,4999.7
XS Rating Curve= 0 ,0
Exp/Cntr=0.3,0.1

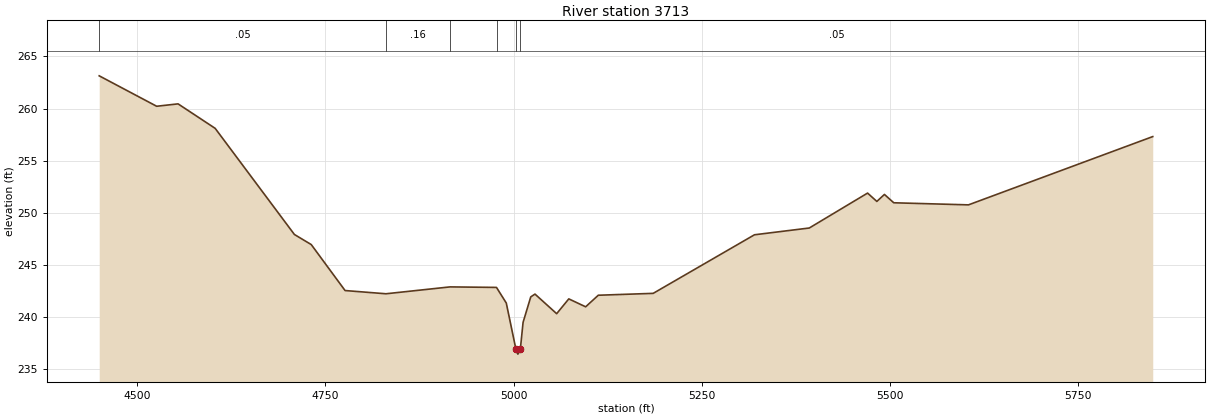
Type RM Length L Ch R = 1 ,3713    ,0,0,0
BEGIN DESCRIPTION:
UNT0509 IN WICK 1.0
END DESCRIPTION:
XS GIS Cut Line= 4
      3580503.46     10229008.07      3580392.11     10228891.64
      3579435.75     10228417.79      3579276.11      10228478.2
#Sta/Elev= 30
  4449.8  263.14  4526.1  260.22  4554.5  260.45  4603.8   258.1    4709  247.92
  4731.4  246.95  4776.3  242.54  4830.6  242.23  4915.7  242.89  4977.4  242.84
  4990.4  241.34  5003.1  236.94  5005.8  236.44  5009.1  236.94  5012.7  239.49
  5022.9  241.93  5028.5   242.2  5057.3  240.32  5073.4  241.74  5095.8  240.98
  5112.6  242.09  5185.5  242.27    5320  247.89  5392.8  248.54  5470.2  251.89
  5482.5  251.09  5492.6  251.76    5505  250.96  5604.2  250.76  5848.9  257.31
#Mann= 6 ,-1 , 0
  4449.8     .05       0  4830.6     .16       0  4915.7     .12       0
  4977.4     .05       0  5003.1    .035       0  5009.1     .05       0
Bank Sta=5003.1,5009.1
XS Rating Curve= 0 ,0
Exp/Cntr=0.3,0.1

Chan Stop Cuts=-1
Use User Specified Reach Order=0
Composite Channel Slope=5