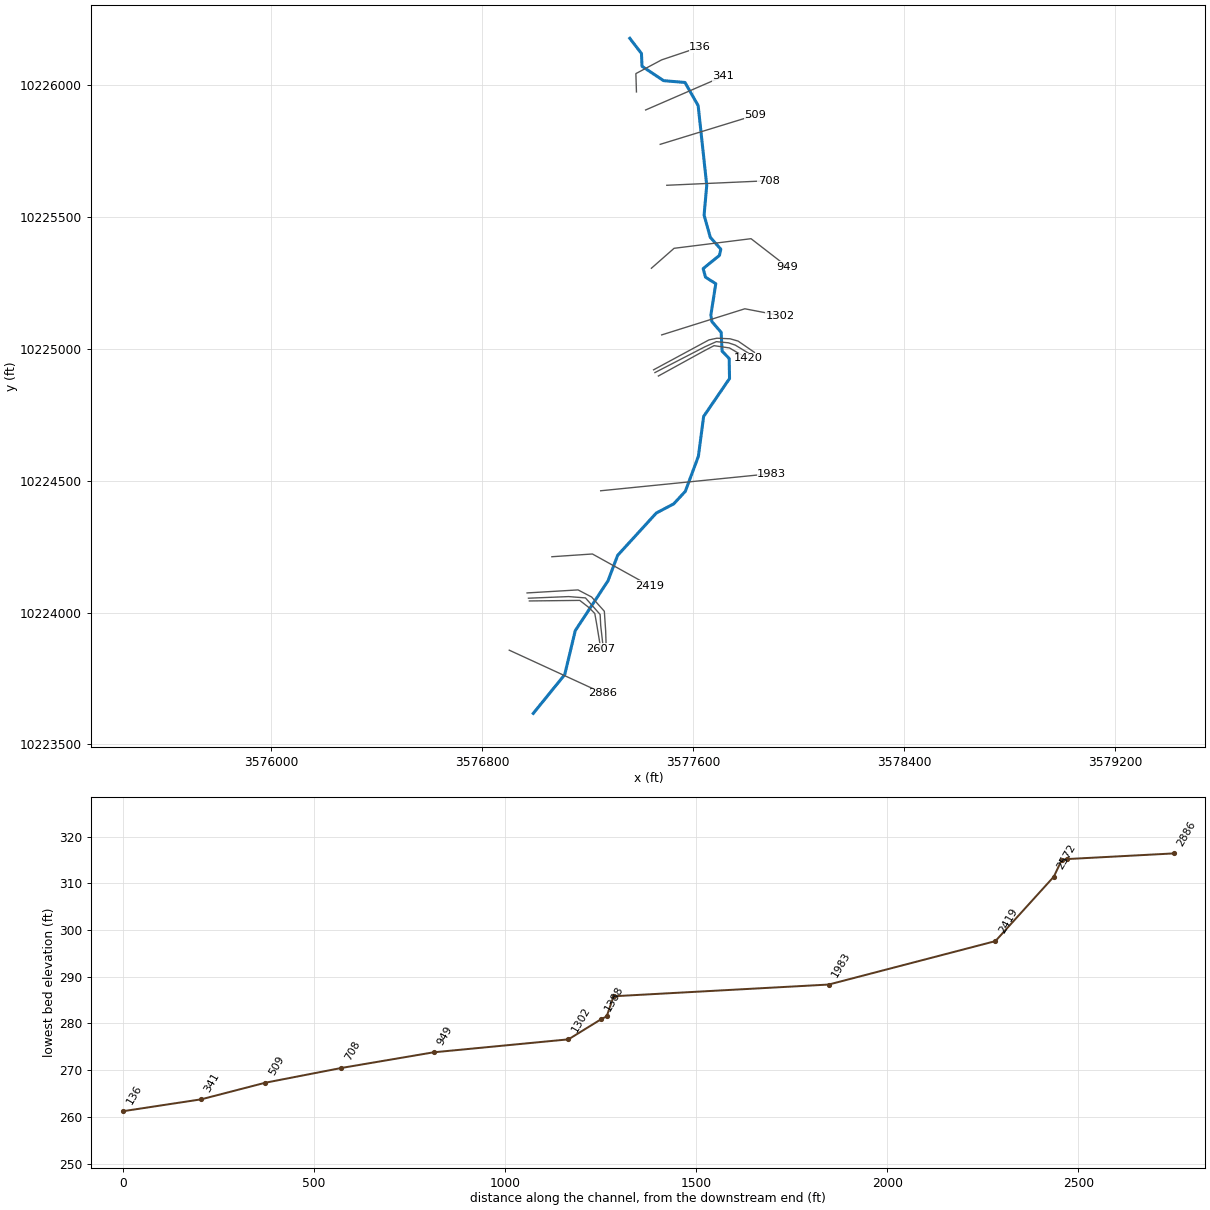
--- BRUSHYCREEKTRIB1.prj (project) ---

Proj Title=BRUSHY CREEK TRIB 11 1
Current Plan=p01
Default Exp/Contr=0.3,0.1
English Units
Geom File=g01
Flow File=f01
Plan File=p01
Y Axis Title=Elevation
X Axis Title(PF)=Main Channel Distance
X Axis Title(XS)=Station
BEGIN DESCRIPTION:
UNT113 IN WICK
END DESCRIPTION:
DSS Export Rating Curves= 0
DSS Export Rating Curve Sorted= 0
DSS Export Volume Flow Curves= 0
DXF Filename=UNT113 IN WICK.
DXF OffsetX= 0
DXF OffsetY= 0
DXF ScaleX= 1
DXF ScaleY= 10

--- BRUSHYCREEKTRIB1.p01 (plan) ---

Plan Title=Multiple Run
Short Identifier=Multiple
Geom File=g01
Flow File=f01
Subcritical Flow
K Sum by GR= 0
Std Step Tol= 0.01
Critical Tol= 0.01
Num of Std Step Trials= 20
Max Error Tol= 0.3
Flow Tol Ratio= 0.001
Split Flow NTrial= 30
Split Flow Tol= 0.02
Split Flow Ratio= 0.02
Log Output Level= 0
Friction Slope Method= 1
Unsteady Friction Slope Method= 2
Unsteady Bridges Friction Slope Method= 1
Parabolic Critical Depth
Global Vel Dist=  1 , 1 , 1
Global Log Level= 0
CheckData=True
Encroach Param= -1, 0, 0, 0
BEGIN DESCRIPTION:
Multiple Run
END DESCRIPTION:

--- BRUSHYCREEKTRIB1.f01 (steady flow) ---

Flow Title=Multiple
Program Version=4.10
Number of Profiles= 7
Profile Names=10-year,25-year,50-year,1pct_min,100-year,1pct_plu,500-year
River Rch & RM=UNT113 IN WICK,Reach-1         ,2886
     123     150     170     143     193     261     247
River Rch & RM=BRUSHYCRTR111,Reach-1         ,2886
     123     150     170     143     193     261     247
Boundary for River Rch & Prof#=BRUSHYCRTR111,Reach-1         , 1
Up Type= 0
Dn Type= 3
Dn Slope=0.005
Boundary for River Rch & Prof#=BRUSHYCRTR111,Reach-1         , 2
Up Type= 0
Dn Type= 3
Dn Slope=0.005
Boundary for River Rch & Prof#=BRUSHYCRTR111,Reach-1         , 3
Up Type= 0
Dn Type= 3
Dn Slope=0.005
Boundary for River Rch & Prof#=BRUSHYCRTR111,Reach-1         , 4
Up Type= 0
Dn Type= 3
Dn Slope=0.005
Boundary for River Rch & Prof#=BRUSHYCRTR111,Reach-1         , 5
Up Type= 0
Dn Type= 3
Dn Slope=0.005
Boundary for River Rch & Prof#=BRUSHYCRTR111,Reach-1         , 6
Up Type= 0
Dn Type= 3
Dn Slope=0.005
Boundary for River Rch & Prof#=BRUSHYCRTR111,Reach-1         , 7
Up Type= 0
Dn Type= 3
Dn Slope=0.005
DSS Import GetInterval= 0
DSS Import GetPeak= 0
DSS Import FillOption= 0

--- BRUSHYCREEKTRIB1.g01 (geometry) ---

Geom Title=Existing Conditions
Program Version=4.10

River Reach=BRUSHYCRTR111   ,Reach-1
Reach XY= 30
      3576993.89     10223617.78      3577113.05     10223764.52
      3577152.98     10223931.19      3577277.13     10224120.26
      3577313.59     10224216.61      3577460.29     10224377.21
      3577525.83     10224411.49       3577570.1     10224459.24
      3577619.58     10224592.05      3577639.55     10224743.09
      3577737.64     10224886.75      3577736.34     10224962.71
      3577709.43     10224990.49      3577705.95     10225061.67
       3577670.8     10225102.47      3577666.89     10225127.21
      3577685.55     10225246.13      3577646.49     10225270.87
      3577637.81     10225303.42      3577699.44     10225353.33
      3577704.65     10225376.77      3577664.72     10225421.91
      3577641.28     10225506.11      3577651.27     10225618.96
      3577618.71     10225921.04       3577568.8     10226008.72
      3577487.64     10226015.66      3577406.04     10226069.91
      3577403.87     10226118.52      3577359.77     10226175.98

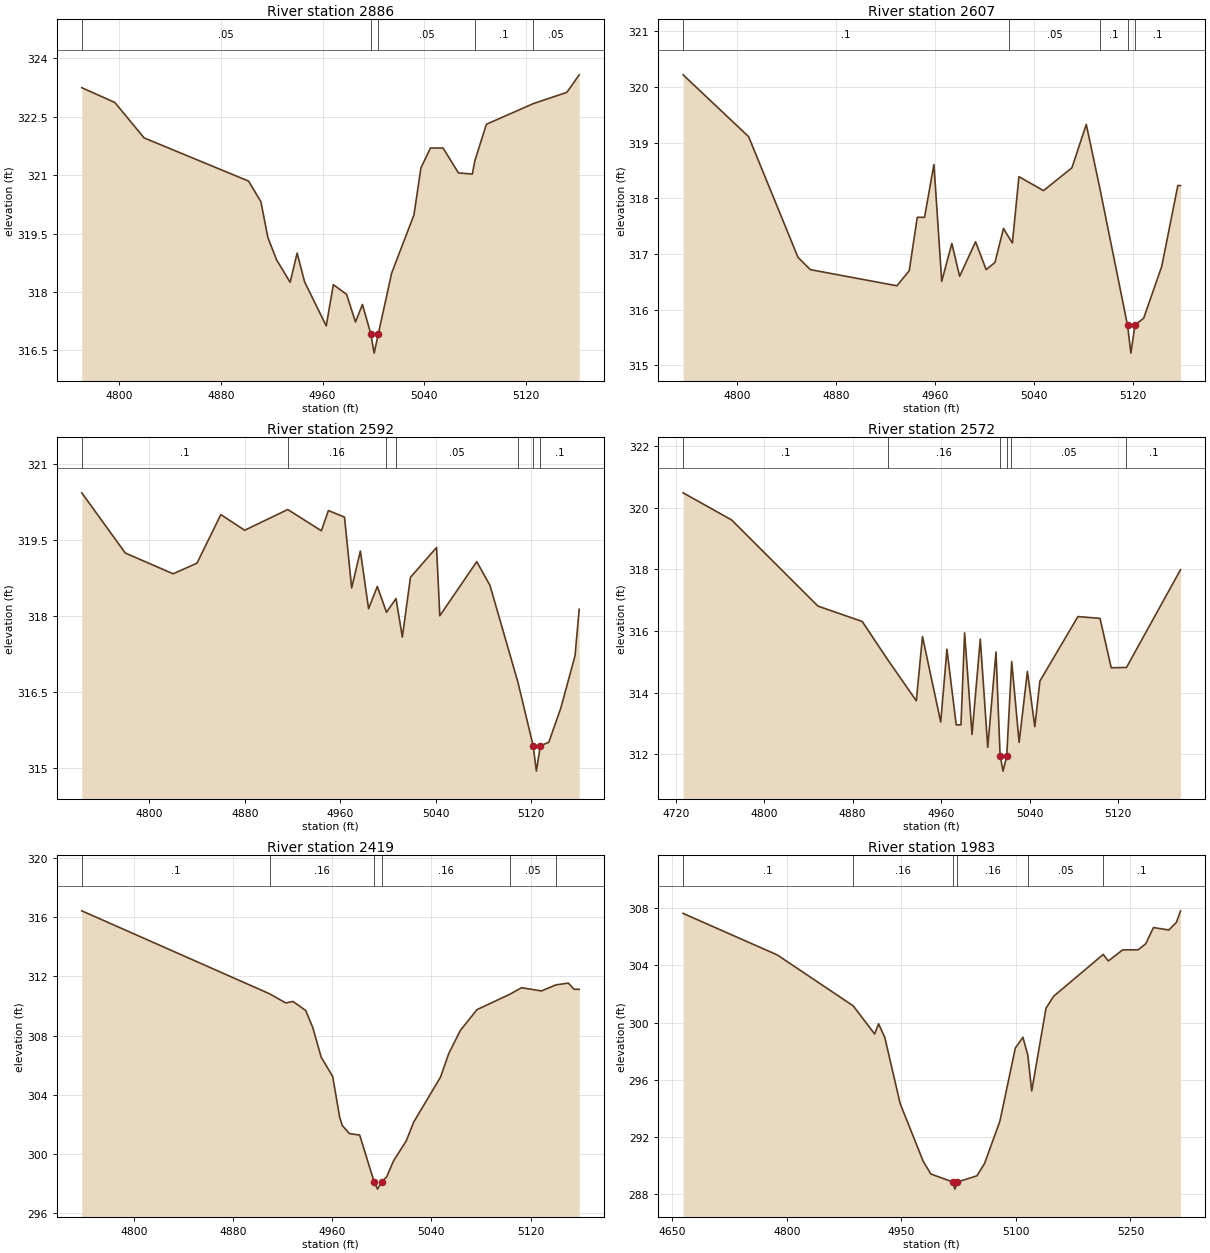
Type RM Length L Ch R = 1 ,2886    ,279,279,279
BEGIN DESCRIPTION:
UNT113 IN WICK 6.0
END DESCRIPTION:
XS GIS Cut Line= 2
      3576902.88     10223857.25      3577258.39     10223693.77
#Sta/Elev= 30
  4770.6  323.25  4796.6  322.87  4819.6  321.96  4901.8  320.85  4911.5  320.32
    4917   319.4  4923.8  318.83  4934.5  318.25    4940     319  4945.9  318.26
  4962.9  317.13  4968.5  318.19  4978.9  317.94  4985.9  317.23  4991.4  317.68
  4997.9  316.93  5000.6  316.43  5003.9  316.93  5014.4  318.49  5031.9  319.98
  5037.4  321.19  5044.9   321.7  5054.8   321.7  5066.9  321.06  5077.8  321.03
  5079.9  321.38  5088.9  322.31  5125.8  322.84  5152.2  323.13  5161.9  323.58
#Mann= 5 ,-1 , 0
  4770.6     .05       0  4997.9     .04       0  5003.9     .05       0
  5079.9      .1       0  5125.8     .05       0
Bank Sta=4997.9,5003.9
XS Rating Curve= 0 ,0
Exp/Cntr=0.3,0.1

Type RM Length L Ch R = 1 ,2607    ,15,15,15
BEGIN DESCRIPTION:
Mapping XS d4014a3e
END DESCRIPTION:
XS GIS Cut Line= 6
      3576979.08     10224043.83      3577169.99     10224045.95
       3577206.1     10224017.78      3577227.04     10223996.12
      3577234.99     10223951.34      3577249.67     10223862.27
#Sta/Elev= 30
  4756.1  320.22  4809.1  319.11  4849.1  316.94  4859.1  316.72  4929.1  316.43
  4939.1   316.7  4945.6  317.66  4951.5  317.66  4959.1  318.61  4965.4  316.51
  4973.6  317.19  4979.9   316.6  4992.8  317.22  5001.4  316.72  5008.5  316.85
  5015.4  317.46  5019.7   317.3  5022.6   317.2  5027.9  318.39  5047.8  318.14
  5070.8  318.55  5082.4  319.33  5093.4  318.18  5115.8  315.72  5118.5  315.22
  5121.8  315.72  5128.9  315.85  5143.5  316.78  5156.5  318.23  5158.7  318.23
#Mann= 5 ,-1 , 0
  4756.1      .1       0  5019.7     .05       0  5093.4      .1       0
  5115.8     .07       0  5121.8      .1       0
Bank Sta=5115.8,5121.8
XS Rating Curve= 0 ,0
Exp/Cntr=0.3,0.1

Type RM Length L Ch R = 1 ,2592    ,20,20,20
BEGIN DESCRIPTION:
Mapping XS 92efbc2f
END DESCRIPTION:
XS GIS Cut Line= 6
      3576975.62     10224054.25       3577128.1      10224060.4
      3577191.65     10224055.34      3577247.27     10223992.51
      3577249.43     10223950.62      3577257.86     10223876.26
#Sta/Elev= 30
  4743.3  320.43  4779.8  319.24  4819.9  318.83  4839.9  319.04  4859.9     320
  4879.9  319.69    4916   320.1  4944.2  319.68  4950.1  320.08  4963.6  319.95
  4969.6  318.55  4976.9  319.28  4983.8  318.14  4991.1  318.58  4998.8  318.07
  5006.8  318.34  5012.1  317.58  5018.9  318.76  5040.8  319.35  5043.5     318
  5074.5  319.07  5085.6   318.6  5109.1  316.68  5121.8  315.43  5124.5  314.93
  5127.8  315.43  5134.9   315.5  5144.9  316.17  5156.9  317.21  5160.4  318.13
#Mann= 7 ,-1 , 0
  4743.3      .1       0    4916     .16       0  4998.8      .1       0
  5006.8     .05       0  5109.1      .1       0  5121.8     .07       0
  5127.8      .1       0
Bank Sta=5121.8,5127.8
XS Rating Curve= 0 ,0
Exp/Cntr=0.3,0.1

Type RM Length L Ch R = 1 ,2572    ,153,153,153
BEGIN DESCRIPTION:
Mapping XS 0a77530b
END DESCRIPTION:
XS GIS Cut Line= 6
      3576970.38     10224074.21      3577163.49     10224085.68
      3577214.77     10224058.95      3577263.16     10224004.78
      3577268.21     10223930.39      3577269.88     10223878.99
#Sta/Elev= 30
  4726.7  320.48  4770.6   319.6  4848.6  316.81  4888.7  316.31  4911.6  315.08
  4937.6  313.74  4943.2  315.82  4959.7  313.05  4965.3  315.41  4973.7  312.96
    4978  312.96  4981.3  315.94    4988  312.65  4995.5  315.74  5002.2  312.23
  5009.7  315.32  5013.4  311.96  5016.1  311.46  5019.4  311.96  5023.2  314.54
  5023.9  315.01  5030.6  312.39  5038.1  314.69  5044.8   312.9  5049.4  314.38
  5083.8  316.47  5103.8  316.41  5113.9  314.81  5127.7  314.82  5176.6  317.99
#Mann= 6 ,-1 , 0
  4726.7      .1       0  4911.6     .16       0  5013.4     .07       0
  5019.4     .16       0  5023.2     .05       0  5127.7      .1       0
Bank Sta=5013.4,5019.4
XS Rating Curve= 0 ,0
Exp/Cntr=0.3,0.1

Type RM Length L Ch R = 1 ,2419    ,436,436,436
BEGIN DESCRIPTION:
UNT113 IN WICK 5.0
END DESCRIPTION:
XS GIS Cut Line= 3
      3577064.36      10224211.4      3577218.02     10224221.82
      3577434.14     10224102.04
#Sta/Elev= 30
  4758.1  316.43  4909.5  310.83  4922.6  310.21  4928.4  310.31  4938.7   309.7
  4944.4  308.54  4951.1  306.56  4960.4  305.25  4966.1  302.48  4968.2  301.93
  4973.9  301.39  4982.2  301.29  4993.8  298.14  4996.6  297.64  4999.8  298.14
  5003.9  298.46  5009.6  299.57  5019.7  300.89  5025.7  302.16  5047.4  305.21
    5054  306.79  5063.4  308.36  5076.8  309.76  5103.6  310.81  5112.7  311.24
  5128.7  311.02  5140.5  311.43  5150.4  311.55  5155.2  311.13  5159.2  311.13
#Mann= 6 ,-1 , 0
  4758.1      .1       0  4909.5     .16       0  4993.8     .07       0
  4999.8     .16       0  5103.6     .05       0  5140.5     .16       0
Bank Sta=4993.8,4999.8
XS Rating Curve= 0 ,0
Exp/Cntr=0.3,0.1

Type RM Length L Ch R = 1 ,1983    ,563,563,563
BEGIN DESCRIPTION:
UNT113 IN WICK 4.0
END DESCRIPTION:
XS GIS Cut Line= 2
      3577249.29      10224461.4      3577897.43     10224526.48
#Sta/Elev= 30
  4664.2  307.64  4787.6  304.73  4886.9  301.17    4915   299.2  4920.1  299.91
  4928.3  298.96  4948.4  294.33  4978.6  290.29  4988.6   289.4  5017.4  288.84
  5020.1  288.34  5023.4  288.84  5048.9  289.27    5059  290.14  5079.1  293.11
  5099.2  298.21  5109.2  298.97  5115.6  297.72  5120.7  295.21  5139.4     301
  5149.4  301.84  5214.4  304.77    5221  304.31  5239.9  305.09    5260  305.09
    5270  305.51  5280.1  306.65  5300.2  306.48  5310.2  307.01  5315.6  307.82
#Mann= 6 ,-1 , 0
  4664.2      .1       0  4886.9     .16       0  5017.4     .07       0
  5023.4     .16       0  5115.6     .05       0  5214.4      .1       0
Bank Sta=5017.4,5023.4
XS Rating Curve= 0 ,0
Exp/Cntr=0.3,0.1

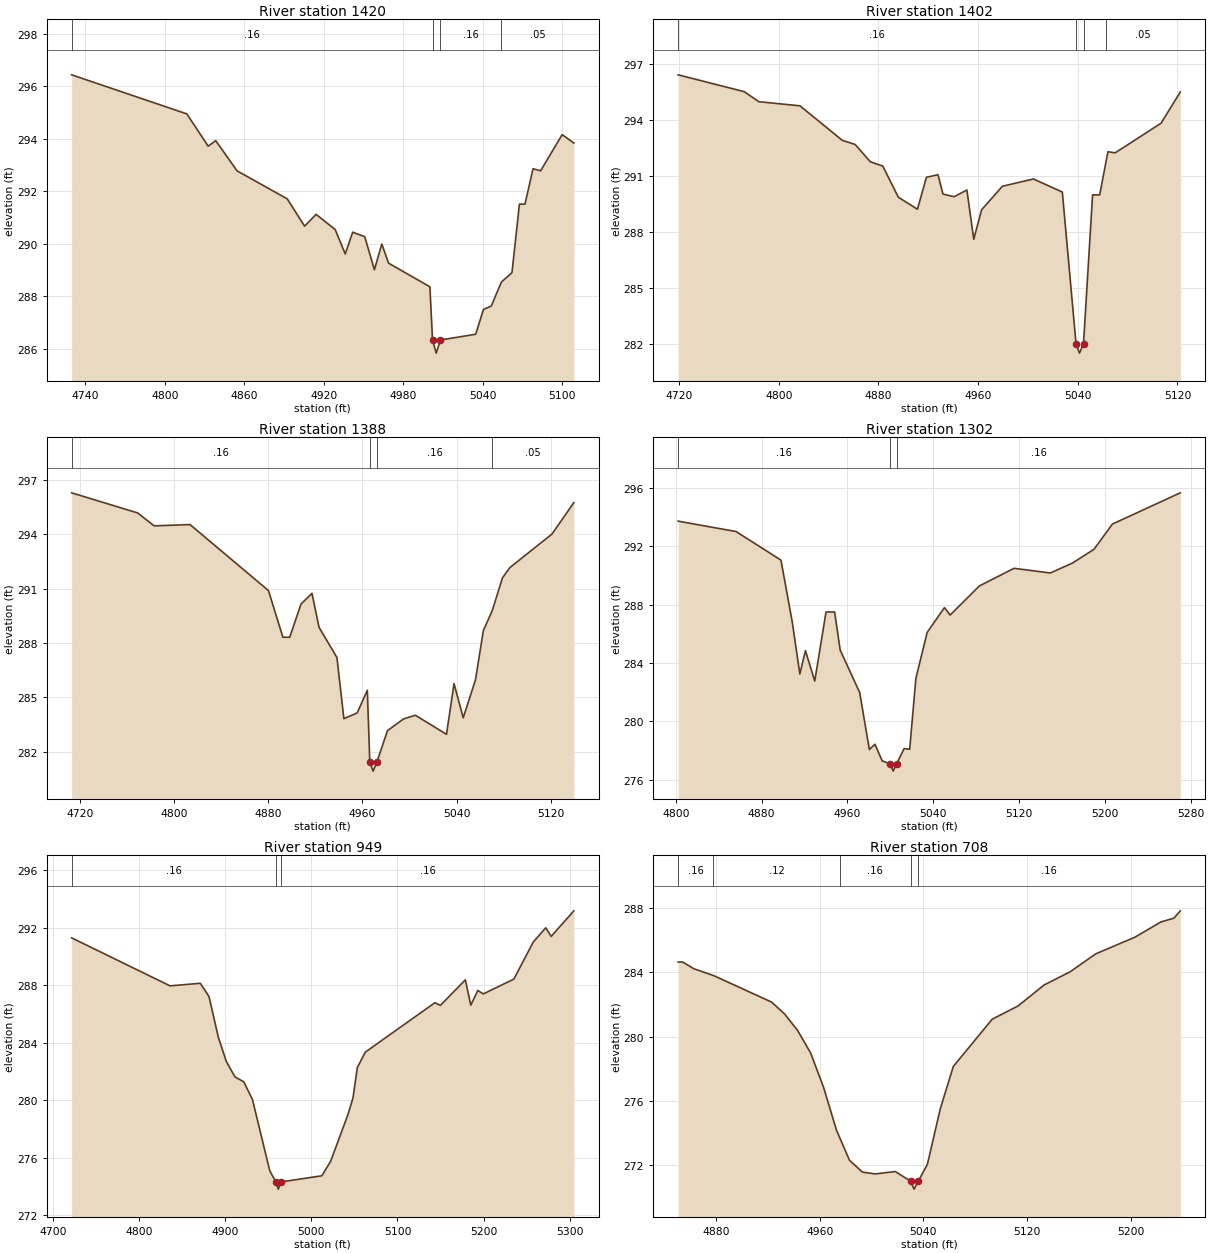
Type RM Length L Ch R = 1 ,1420    ,18,18,18
BEGIN DESCRIPTION:
Mapping XS e3807df0
END DESCRIPTION:
XS GIS Cut Line= 6
      3577467.98     10224896.28      3577637.72     10224989.61
      3577678.96     10225011.32      3577737.55     10225002.63
      3577774.44     10224980.93      3577806.96     10224963.59
#Sta/Elev= 30
  4729.7  296.44  4816.7  294.95  4832.8  293.72  4838.5  293.93  4854.6  292.78
  4892.5  291.71  4905.6  290.67  4914.3  291.12  4928.7  290.54  4936.3  289.61
  4941.9  290.44    4951  290.27  4958.3  289.01  4963.9  289.99    4969  289.26
  5000.2  288.36  5002.2  286.33    5005  285.83  5008.2  286.33  5034.8  286.55
  5040.7   287.5  5046.5  287.62  5054.2  288.54  5062.2   288.9  5067.8  291.51
    5072  291.51  5078.1  292.86  5083.8  292.78  5100.1  294.16  5108.9  293.84
#Mann= 4 ,-1 , 0
  4729.7     .16       0  5002.2     .07       0  5008.2     .16       0
  5054.2     .05       0
Bank Sta=5002.2,5008.2
XS Rating Curve= 0 ,0
Exp/Cntr=0.3,0.1

Type RM Length L Ch R = 1 ,1402    ,14,14,14
BEGIN DESCRIPTION:
Mapping XS 119423a8
END DESCRIPTION:
XS GIS Cut Line= 6
      3577454.96      10224909.3      3577644.24     10225006.97
      3577687.64     10225026.51      3577733.21     10225022.17
      3577759.25     10225013.49      3577818.48     10224977.53
#Sta/Elev= 30
  4719.2  296.43  4772.2  295.53    4784  294.99    4817  294.77    4851  292.92
  4861.3   292.7  4873.5  291.77  4883.5  291.54    4896  289.87  4911.3  289.23
  4918.5  290.94  4927.8  291.08  4931.8  290.04  4940.8   289.9    4951  290.26
  4956.5  287.62  4962.8   289.2  4979.5  290.46  5004.4  290.85  5027.6  290.15
  5038.6  282.02  5041.4  281.52  5044.6  282.02  5051.9     290  5057.6     290
  5062.6  291.75  5064.2  292.31    5070  292.25  5106.9  293.84  5122.3  295.51
#Mann= 4 ,-1 , 0
  4719.2     .16       0  5038.6     .07       0  5044.6     .16       0
  5062.6     .05       0
Bank Sta=5038.6,5044.6
XS Rating Curve= 0 ,0
Exp/Cntr=0.3,0.1

Type RM Length L Ch R = 1 ,1388    ,86,86,86
BEGIN DESCRIPTION:
Mapping XS 326bc54a
END DESCRIPTION:
XS GIS Cut Line= 6
      3577449.81     10224919.75      3577659.43     10225033.02
      3577689.81     10225039.53      3577739.72     10225037.36
       3577770.1     10225028.68      3577832.03     10224985.97
#Sta/Elev= 30
  4713.2  296.28  4769.3  295.17  4783.2  294.46  4813.7  294.53  4880.3  290.89
  4892.5  288.32  4898.3  288.32  4907.9  290.15  4917.2  290.74  4923.2  288.87
  4938.4   287.2  4944.3  283.83  4955.6  284.15  4964.2   285.4  4966.3  281.44
  4969.1  280.94  4972.3  281.44  4981.3  283.17    4995  283.82    5005  284.02
  5031.4  282.97  5037.8  285.76  5045.6  283.88    5056  285.97  5062.7  288.69
  5070.2  289.78  5078.9  291.59  5085.2  292.16    5121  294.01  5139.5  295.74
#Mann= 4 ,-1 , 0
  4713.2     .16       0  4966.3     .07       0  4972.3     .16       0
  5070.2     .05       0
Bank Sta=4966.3,4972.3
XS Rating Curve= 0 ,0
Exp/Cntr=0.3,0.1

Type RM Length L Ch R = 1 ,1302    ,353,353,353
BEGIN DESCRIPTION:
UNT113 IN WICK 3.0
END DESCRIPTION:
XS GIS Cut Line= 3
      3577480.58      10225052.1      3577795.71     10225151.07
      3577931.12     10225125.03
#Sta/Elev= 30
  4802.1  293.72  4856.1  293.01    4898  291.05  4908.5  286.82  4915.6  283.25
  4920.8  284.85  4929.5  282.77    4940   287.5    4948   287.5  4953.2  284.89
  4971.4  281.98  4980.4  278.08  4985.6  278.44  4992.4   277.3  4999.8   277.1
  5002.6   276.6  5005.8   277.1  5012.8  278.14    5018   278.1  5023.8  282.96
  5034.3   286.1  5050.4   287.8  5055.7  287.29  5082.9  289.28  5115.3  290.49
  5149.1  290.17  5169.5  290.84  5189.8  291.79    5207  293.52  5270.3  295.66
#Mann= 3 ,-1 , 0
  4802.1     .16       0  4999.8     .07       0  5005.8     .16       0
Bank Sta=4999.8,5005.8
XS Rating Curve= 0 ,0
Exp/Cntr=0.3,0.1

Type RM Length L Ch R = 1 ,949     ,241,241,241
BEGIN DESCRIPTION:
UNT113 IN WICK 2.0
END DESCRIPTION:
XS GIS Cut Line= 4
      3577441.54     10225304.71      3577527.48     10225380.24
      3577819.15      10225416.7      3577957.13     10225309.96
#Sta/Elev= 30
  4721.9   291.3  4836.1  287.96  4871.2  288.14  4881.3  287.22  4892.2  284.37
  4901.4   282.7  4911.5  281.62  4921.6  281.29  4931.7  280.06  4951.8   275.1
  4958.9  274.32  4961.7  273.82  4964.9  274.32  5012.3  274.75  5022.4  275.75
  5042.5     279  5048.4  280.16  5053.4  282.27  5062.7  283.35  5143.5  286.79
  5149.8   286.6  5178.8  288.38  5185.1  286.62  5193.3  287.64  5199.6   287.4
  5235.1  288.43  5257.6  291.01  5272.1     292  5278.4   291.4  5304.7  293.18
#Mann= 3 ,-1 , 0
  4721.9     .16       0  4958.9     .07       0  4964.9     .16       0
Bank Sta=4958.9,4964.9
XS Rating Curve= 0 ,0
Exp/Cntr=0.3,0.1

Type RM Length L Ch R = 1 ,708     ,199,199,199
BEGIN DESCRIPTION:
Mapping XS c2dbed95
END DESCRIPTION:
XS GIS Cut Line= 2
      3577499.94     10225619.12      3577887.15     10225636.48
#Sta/Elev= 30
  4850.7  284.65  4854.3  284.65  4862.9  284.23    4878  283.81  4922.9  282.15
    4933   281.4    4943  280.37    4953  278.97    4963  276.82    4973  274.14
  4975.5  273.67    4983  272.27    4993  271.53    5003  271.42  5018.3  271.57
  5030.1  270.97  5032.8  270.47  5036.1  270.97  5043.1  272.02  5053.1   275.5
  5063.1  278.13  5093.1  281.08  5113.1  281.91  5133.2  283.22  5153.2  284.04
  5173.2  285.17  5203.2   286.2  5223.2  287.15  5233.3  287.39  5238.3  287.85
#Mann= 5 ,-1 , 0
  4850.7     .16       0    4878     .12       0  4975.5     .16       0
  5030.1     .07       0  5036.1     .16       0
Bank Sta=5030.1,5036.1
XS Rating Curve= 0 ,0
Exp/Cntr=0.3,0.1

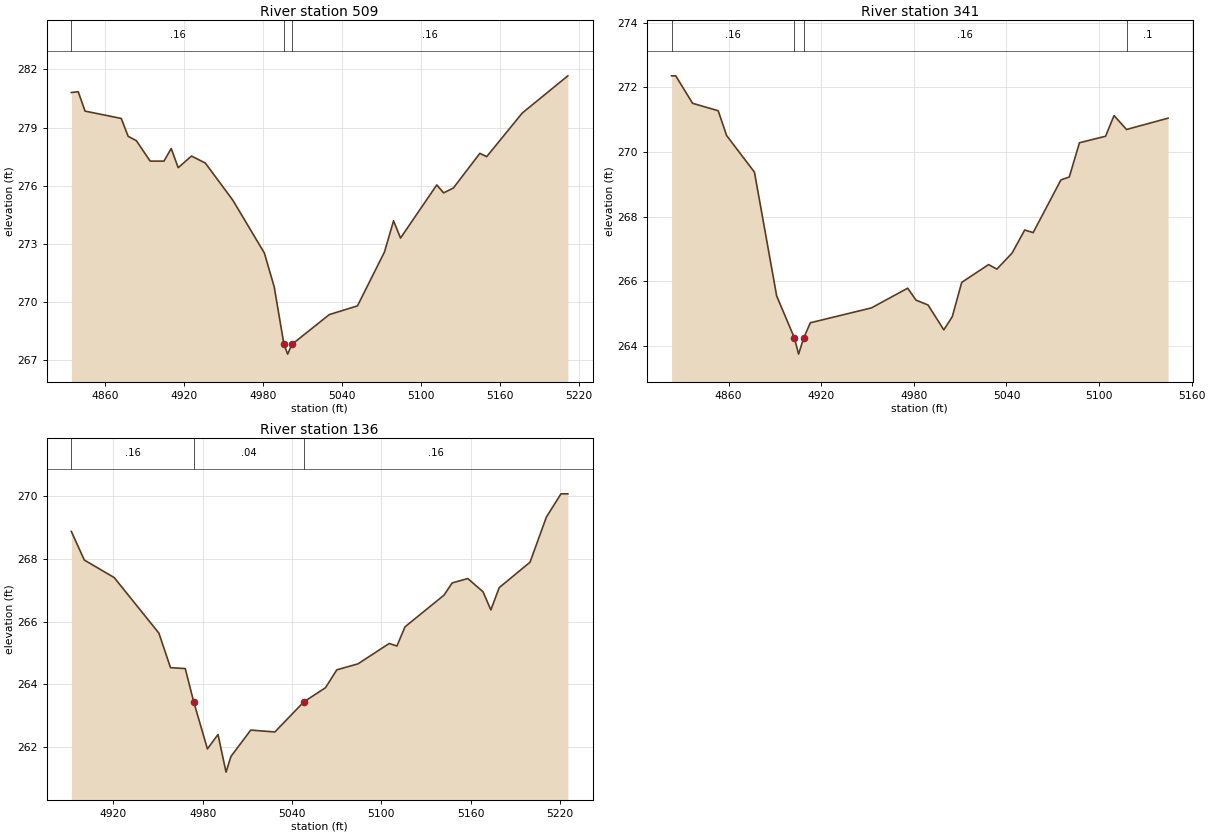
Type RM Length L Ch R = 1 ,509     ,168,168,168
BEGIN DESCRIPTION:
Mapping XS ec94cb14
END DESCRIPTION:
XS GIS Cut Line= 2
      3577474.93     10225774.28      3577835.21     10225884.97
#Sta/Elev= 30
  4834.6  280.81  4839.8  280.85    4845  279.85  4872.5  279.47  4877.7  278.55
    4884  278.32  4894.4  277.27  4904.9  277.27  4910.4  277.92  4915.7  276.93
  4925.8  277.53  4936.3  277.17  4957.2  275.25  4981.1  272.53  4988.6  270.78
    4996  267.81  4998.8  267.31    5002  267.81  5030.4  269.35  5051.8   269.8
  5072.3  272.58  5079.2  274.19  5084.5   273.3    5112  276.04  5117.2  275.63
  5124.6  275.88  5144.7  277.67  5149.9   277.5  5176.9  279.75  5211.5  281.67
#Mann= 3 ,-1 , 0
  4834.6     .16       0    4996     .07       0    5002     .16       0
Bank Sta=4996,5002
XS Rating Curve= 0 ,0
Exp/Cntr=0.3,0.1

Type RM Length L Ch R = 1 ,341     ,205,205,205
BEGIN DESCRIPTION:
Mapping XS 6bf01391
END DESCRIPTION:
XS GIS Cut Line= 2
      3577419.64     10225904.51      3577714.76     10226032.54
#Sta/Elev= 30
    4823  272.36  4825.7  272.36  4836.6  271.51  4853.2  271.28  4858.7  270.51
  4876.7  269.38  4891.1  265.55  4902.6  264.25  4905.3  263.75  4908.6  264.25
  4912.9  264.72  4952.5  265.18    4976  265.79  4981.4  265.42  4989.2  265.27
  4999.4   264.5  5004.9  264.91    5011  265.97  5028.4  266.52  5033.8  266.38
  5043.7  266.88  5051.8  267.59  5057.3  267.51  5075.3  269.14  5080.7  269.23
  5087.3  270.29  5104.2  270.49  5109.7  271.13  5117.8   270.7  5144.7  271.05
#Mann= 4 ,-1 , 0
    4823     .16       0  4902.6     .07       0  4908.6     .16       0
  5117.8      .1       0
Bank Sta=4902.6,4908.6
XS Rating Curve= 0 ,0
Exp/Cntr=0.3,0.1

Type RM Length L Ch R = 1 ,136     ,0,0,0
BEGIN DESCRIPTION:
UNT113 IN WICK 1.0
END DESCRIPTION:
XS GIS Cut Line= 4
      3577384.88      10225972.9      3577382.72      10226042.3
      3577480.37     10226094.38      3577625.78     10226143.21
#Sta/Elev= 30
  4891.8  268.87  4900.5  267.96  4920.6   267.4  4950.6  265.63  4958.4  264.53
  4968.3   264.5    4974  263.44  4983.2  261.94  4990.3   262.4  4995.7   261.2
    4999   261.7  5012.3  262.54  5028.5  262.48 5047.98  263.44  5062.5  263.89
  5070.1  264.46  5084.3  264.65  5105.3   265.3  5110.5  265.22  5115.9  265.83
  5142.1  266.84  5147.6  267.23  5158.1  267.37  5168.3  266.95  5173.6  266.37
  5179.2  267.08  5199.9  267.89  5210.9  269.33  5220.7  270.07  5225.3  270.07
#Mann= 3 , 0 , 0
  4891.8     .16       0    4974     .04       0 5047.98     .16       0
Bank Sta=4974,5047.98
XS Rating Curve= 0 ,0
Exp/Cntr=0.3,0.1

Chan Stop Cuts=-1
Use User Specified Reach Order=0
Composite Channel Slope=5