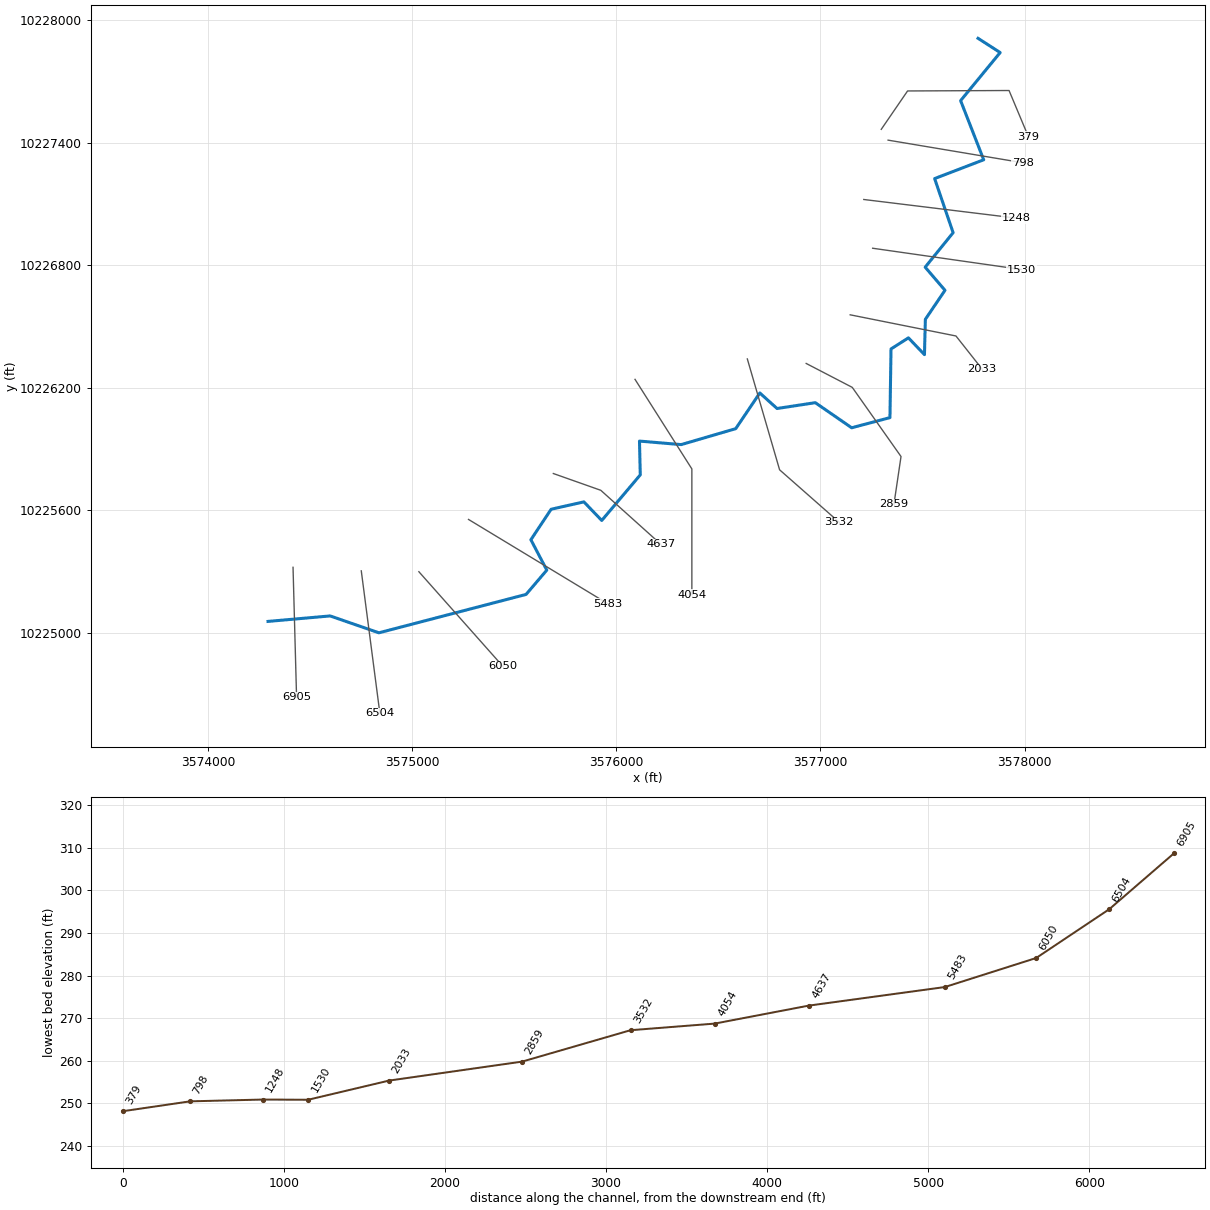
--- BRUSHYCREEKTRIB1.prj (project) ---

Proj Title=BRUSHY CREEK TRIB 11
Current Plan=p01
Default Exp/Contr=0.3,0.1
English Units
Geom File=g01
Flow File=f01
Plan File=p01
Y Axis Title=Elevation
X Axis Title(PF)=Main Channel Distance
X Axis Title(XS)=Station
BEGIN DESCRIPTION:
UNT05302 IN WICK
END DESCRIPTION:
DSS Export Rating Curves= 0
DSS Export Rating Curve Sorted= 0
DSS Export Volume Flow Curves= 0
DXF Filename=UNT05302 IN WICK.
DXF OffsetX= 0
DXF OffsetY= 0
DXF ScaleX= 1
DXF ScaleY= 10

--- BRUSHYCREEKTRIB1.p01 (plan) ---

Plan Title=Multiple Run
Short Identifier=Multiple
Geom File=g01
Flow File=f01
Subcritical Flow
K Sum by GR= 0
Std Step Tol= 0.01
Critical Tol= 0.01
Num of Std Step Trials= 20
Max Error Tol= 0.3
Flow Tol Ratio= 0.001
Split Flow NTrial= 30
Split Flow Tol= 0.02
Split Flow Ratio= 0.02
Log Output Level= 0
Friction Slope Method= 1
Unsteady Friction Slope Method= 2
Unsteady Bridges Friction Slope Method= 1
Parabolic Critical Depth
Global Vel Dist=  1 , 1 , 1
Global Log Level= 0
CheckData=True
Encroach Param= -1, 0, 0, 0
BEGIN DESCRIPTION:
Multiple Run
END DESCRIPTION:

--- BRUSHYCREEKTRIB1.f01 (steady flow) ---

Flow Title=Multiple
Program Version=4.10
Number of Profiles= 7
Profile Names=10-year,25-year,50-year,1pct_min,100-year,1pct_plu,500-year
River Rch & RM=UNT05302 IN WICK,Reach-1         ,6905
     172     215     248     210     284     384     374
River Rch & RM=UNT05302 IN WICK,Reach-1         ,4054
     227     289     337     289     391     529     527
River Rch & RM=UNT05302 IN WICK,Reach-1         ,3532
     227     289     337     289     391     529     527
River Rch & RM=UNT05302 IN WICK,Reach-1         ,2033
     307     398     469     407     551     745     758
River Rch & RM=BRUSHYCRTR11,Reach-1         ,6905
     172     215     248     210     284     384     374
River Rch & RM=BRUSHYCRTR11,Reach-1         ,4054
     227     289     337     289     391     529     527
River Rch & RM=BRUSHYCRTR11,Reach-1         ,3532
     227     289     337     289     391     529     527
River Rch & RM=BRUSHYCRTR11,Reach-1         ,2033
     307     398     469     407     551     745     758
Boundary for River Rch & Prof#=BRUSHYCRTR11,Reach-1         , 1
Up Type= 0
Dn Type= 3
Dn Slope=0.005
Boundary for River Rch & Prof#=BRUSHYCRTR11,Reach-1         , 2
Up Type= 0
Dn Type= 3
Dn Slope=0.005
Boundary for River Rch & Prof#=BRUSHYCRTR11,Reach-1         , 3
Up Type= 0
Dn Type= 3
Dn Slope=0.005
Boundary for River Rch & Prof#=BRUSHYCRTR11,Reach-1         , 4
Up Type= 0
Dn Type= 3
Dn Slope=0.005
Boundary for River Rch & Prof#=BRUSHYCRTR11,Reach-1         , 5
Up Type= 0
Dn Type= 3
Dn Slope=0.005
Boundary for River Rch & Prof#=BRUSHYCRTR11,Reach-1         , 6
Up Type= 0
Dn Type= 3
Dn Slope=0.005
Boundary for River Rch & Prof#=BRUSHYCRTR11,Reach-1         , 7
Up Type= 0
Dn Type= 3
Dn Slope=0.005
DSS Import GetInterval= 0
DSS Import GetPeak= 0
DSS Import FillOption= 0

--- BRUSHYCREEKTRIB1.g01 (geometry) ---

Geom Title=Existing Conditions
Program Version=4.10

River Reach=BRUSHYCRTR11    ,Reach-1
Reach XY= 30
      3574294.87     10225056.19      3574599.03     10225083.03
      3574837.92     10225000.39      3575558.64     10225188.39
      3575660.08     10225307.38      3575582.16     10225456.12
       3575681.2     10225605.43      3575841.77     10225641.57
      3575929.23     10225550.59      3576117.84     10225773.83
      3576113.99     10225939.29      3576318.12     10225922.04
      3576585.35     10226000.11      3576703.26     10226174.87
      3576787.69     10226098.81      3576974.98     10226127.39
      3577153.13     10226004.46      3577340.57     10226054.19
      3577345.83     10226390.51      3577430.98      10226444.8
      3577509.56     10226362.69      3577514.01     10226535.63
      3577610.07     10226677.73      3577513.08     10226791.04
      3577649.91     10226959.88      3577559.39     10227224.81
      3577799.69     10227316.93      3577686.64     10227606.51
      3577880.25       10227842.      3577772.11     10227911.64

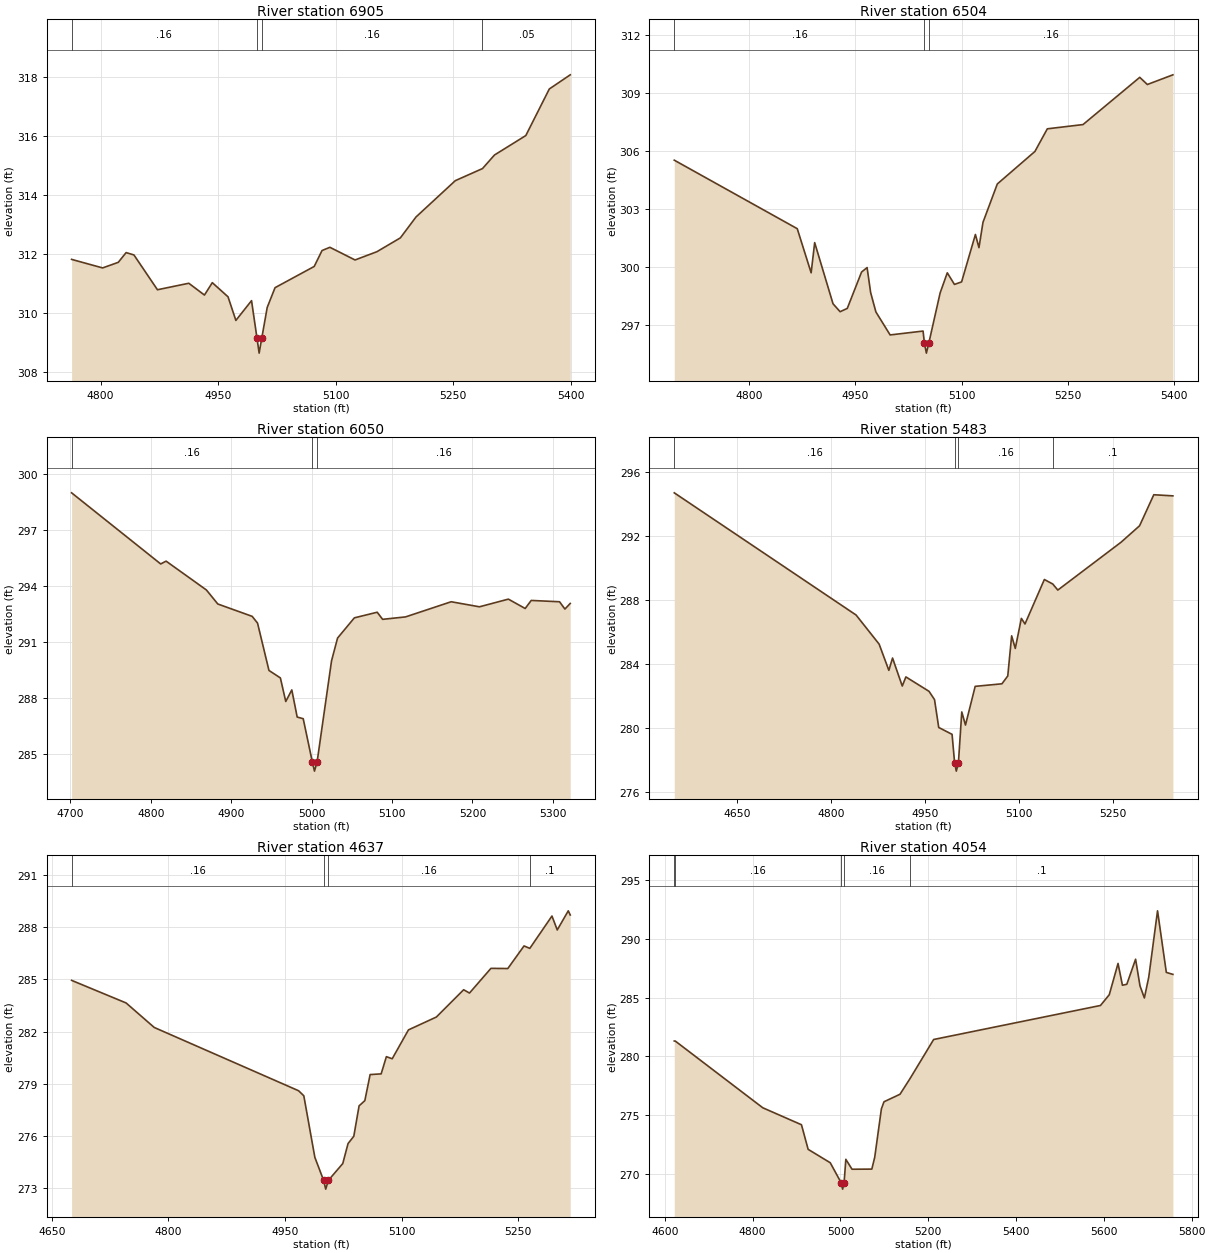
Type RM Length L Ch R = 1 ,6905    ,401,401,401
BEGIN DESCRIPTION:
UNT05302 IN WICK 12.0
END DESCRIPTION:
XS GIS Cut Line= 2
      3574417.35     10225321.23      3574434.66     10224684.96
#Sta/Elev= 30
  4763.1  311.82  4802.7  311.53  4822.7  311.72  4832.7  312.05  4842.7  311.97
  4872.7  310.79  4912.7  311.01  4932.7  310.61  4942.7  311.03  4962.8  310.55
  4972.8  309.75  4992.8  310.42  4999.8  309.14  5002.5  308.64  5005.8  309.14
  5012.8  310.19  5022.8  310.86  5072.8  311.58  5082.8  312.12  5092.8  312.23
  5124.9   311.8  5152.8  312.08  5182.8  312.55  5202.8  313.26  5252.9  314.49
  5287.6   314.9  5302.9  315.36  5342.9  316.02  5372.9   317.6  5399.6  318.08
#Mann= 4 ,-1 , 0
  4763.1     .16       0  4999.8     .07       0  5005.8     .16       0
  5287.6     .05       0
Bank Sta=4999.8,5005.8
XS Rating Curve= 0 ,0
Exp/Cntr=0.3,0.1

Type RM Length L Ch R = 1 ,6504    ,454,454,454
BEGIN DESCRIPTION:
UNT05302 IN WICK 11.0
END DESCRIPTION:
XS GIS Cut Line= 2
      3574751.55     10225303.81      3574842.59     10224605.82
#Sta/Elev= 30
  4694.5  305.53  4868.1  301.99  4887.7  299.71  4892.7  301.27  4918.6  298.11
  4928.6   297.7  4938.7  297.87  4958.9  299.75  4966.7  299.98  4971.7  298.69
  4979.1  297.69  4999.2   296.5  5045.7   296.7  5047.7  296.06  5050.4  295.56
  5053.7  296.06  5069.8  298.67  5079.9  299.71    5090  299.11  5100.1  299.24
  5119.6  301.69  5124.6  301.01  5130.3  302.32  5150.5   304.3  5203.6  305.98
  5221.1  307.15  5271.5  307.37  5351.6  309.81  5362.3  309.44  5398.4  309.94
#Mann= 3 ,-1 , 0
  4694.5     .16       0  5047.7     .07       0  5053.7     .16       0
Bank Sta=5047.7,5053.7
XS Rating Curve= 0 ,0
Exp/Cntr=0.3,0.1

Type RM Length L Ch R = 1 ,6050    ,567,567,567
BEGIN DESCRIPTION:
UNT05302 IN WICK 10.0
END DESCRIPTION:
XS GIS Cut Line= 2
      3575033.64     10225299.53      3575445.27      10224835.9
#Sta/Elev= 30
  4701.6  298.98  4812.4  295.18  4819.1  295.33  4869.2  293.79  4883.4  293.04
  4926.1  292.38  4932.8  292.02    4947  289.49  4961.2  289.09  4967.9  287.83
  4975.4  288.45  4982.1     287  4989.6  286.91  5000.9  284.61  5003.6  284.11
  5006.9  284.61  5024.8     290  5032.3  291.22  5053.2   292.3  5081.6   292.6
  5088.3  292.22  5116.8  292.35  5173.6  293.16  5208.7  292.89  5244.7   293.3
  5265.6   292.8  5273.1  293.23  5308.3  293.16    5315  292.77  5321.6  293.07
#Mann= 3 ,-1 , 0
  4701.6     .16       0  5000.9     .07       0  5006.9     .16       0
Bank Sta=5000.9,5006.9
XS Rating Curve= 0 ,0
Exp/Cntr=0.3,0.1

Type RM Length L Ch R = 1 ,5483    ,846,846,846
BEGIN DESCRIPTION:
UNT05302 IN WICK 9.0
END DESCRIPTION:
XS GIS Cut Line= 2
       3575276.7     10225555.59      3575957.65     10225143.55
#Sta/Elev= 30
  4549.9   294.7  4840.1  287.06  4876.9  285.24  4892.4   283.6  4898.3  284.37
  4913.8  282.62  4919.6  283.19  4956.5  282.29  4965.3  281.77    4972  280.03
  4993.3   279.6  4997.4   277.8  5000.1   277.3  5003.4   277.8  5008.8     281
  5014.7  280.18  5030.2   282.6  5072.9  282.76  5082.2  283.25  5088.4  285.76
  5094.2  284.97  5103.9  286.85  5109.7   286.5  5140.6  289.28    5154     289
  5162.1  288.62    5263  291.61  5292.6  292.64  5315.3  294.58  5345.8  294.51
#Mann= 4 ,-1 , 0
  4549.9     .16       0  4997.4     .07       0  5003.4     .16       0
    5154      .1       0
Bank Sta=4997.4,5003.4
XS Rating Curve= 0 ,0
Exp/Cntr=0.3,0.1

Type RM Length L Ch R = 1 ,4637    ,583,583,583
BEGIN DESCRIPTION:
UNT05302 IN WICK 8.0
END DESCRIPTION:
XS GIS Cut Line= 3
      3575692.15     10225780.41      3575924.51     10225698.27
      3576218.28     10225434.29
#Sta/Elev= 30
  4675.5  284.95  4745.6  283.65  4781.8  282.24  4967.5   278.6  4974.2  278.31
  4988.4  274.77  4999.7  273.44  5002.4  272.94  5005.7  273.44  5024.3  274.41
  5031.1  275.56  5038.5  275.98  5045.3  277.73  5052.7  278.03  5059.5  279.53
  5073.7  279.57  5080.4  280.56  5087.9  280.44  5108.8   282.1  5144.7  282.84
  5179.8  284.41  5187.3  284.22  5214.9  285.64  5236.6  285.63  5257.5  286.93
  5264.9  286.79  5293.4  288.65  5300.2  287.85  5314.4  288.95  5316.9  288.71
#Mann= 4 ,-1 , 0
  4675.5     .16       0  4999.7     .07       0  5005.7     .16       0
  5264.9      .1       0
Bank Sta=4999.7,5005.7
XS Rating Curve= 0 ,0
Exp/Cntr=0.3,0.1

Type RM Length L Ch R = 1 ,4054    ,522,522,522
BEGIN DESCRIPTION:
UNT05302 IN WICK 7.0
END DESCRIPTION:
XS GIS Cut Line= 3
      3576092.13      10226241.6      3576370.47     10225802.97
      3576370.47     10225186.67
#Sta/Elev= 30
  4621.5  281.31  4623.7  281.31  4823.1  275.64  4911.2   274.2  4926.4  272.11
  4976.8  270.97  5002.2  269.23    5005  268.73  5008.2  269.23  5012.3  271.26
  5026.4  270.42  5071.5  270.43  5078.1  271.44  5093.3  275.55  5099.2  276.15
  5135.7  276.79    5159  278.15  5212.3  281.44  5592.3  284.33  5612.3  285.24
  5632.3   287.9  5642.3  286.05  5652.3  286.13  5672.3  288.26  5682.3     286
  5692.3  284.97  5702.3  286.74  5722.3  292.37  5742.3  287.14  5757.3  286.97
#Mann= 5 ,-1 , 0
  4621.5     .05       0  4623.7     .16       0  5002.2     .07       0
  5008.2     .16       0    5159      .1       0
Bank Sta=5002.2,5008.2
XS Rating Curve= 0 ,0
Exp/Cntr=0.3,0.1

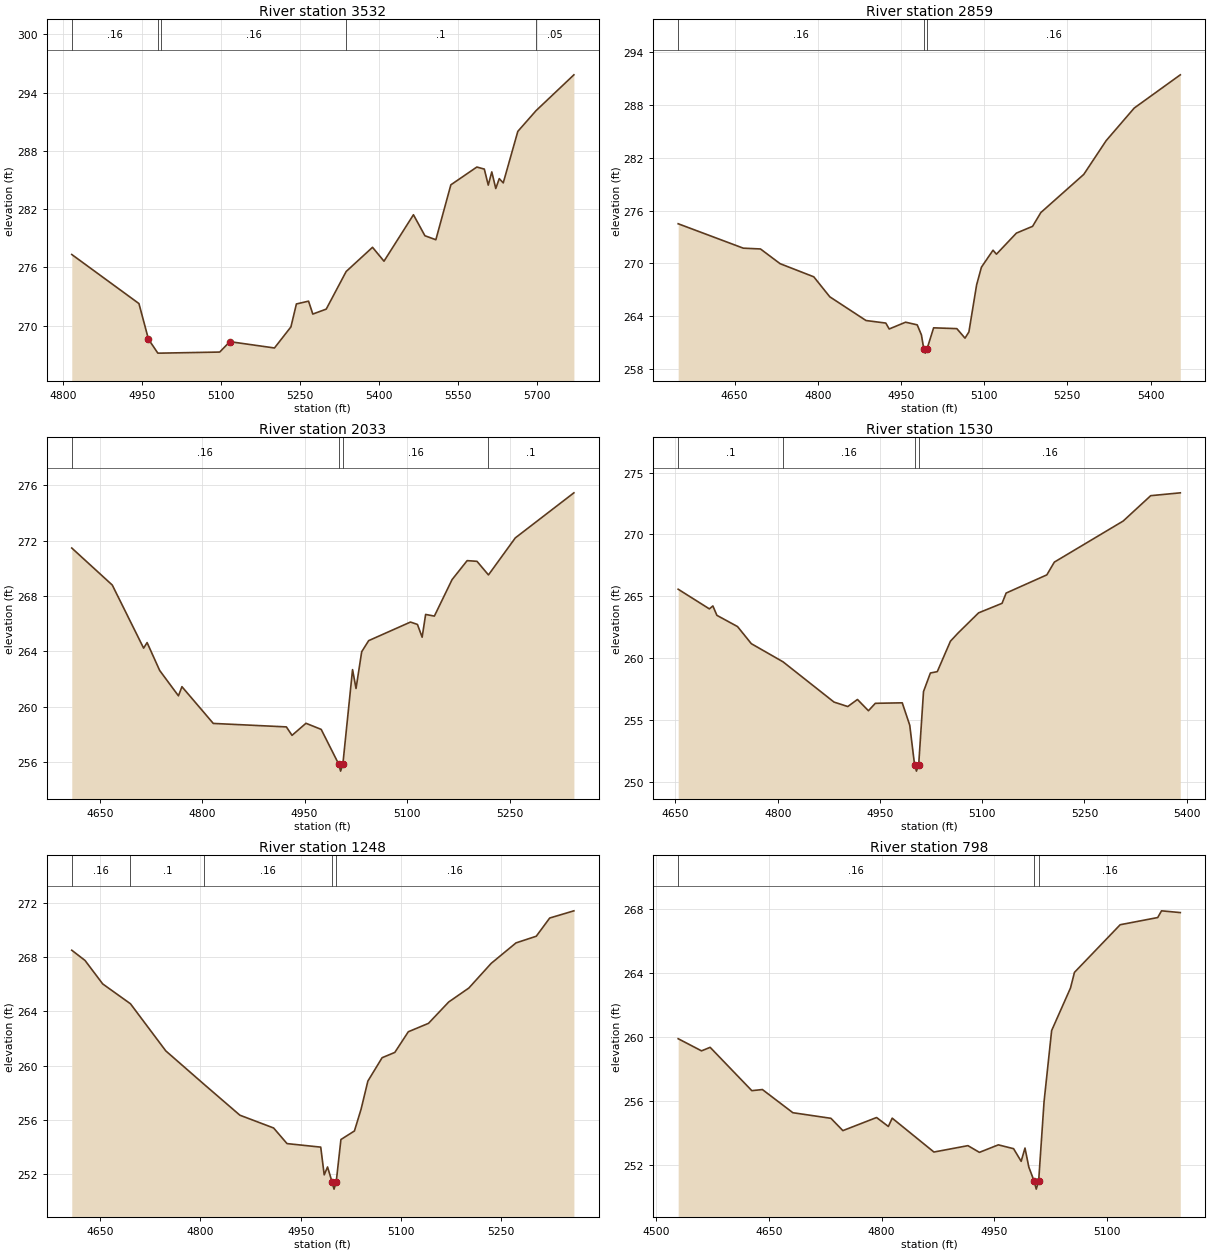
Type RM Length L Ch R = 1 ,3532    ,673,673,673
BEGIN DESCRIPTION:
UNT05302 IN WICK 6.0
END DESCRIPTION:
XS GIS Cut Line= 3
      3576642.11     10226341.62      3576800.16     10225798.63
      3577092.13     10225541.62
#Sta/Elev= 30
  4816.5  277.33  4944.2  272.28  4962.3  268.61  4980.1  267.18  4986.1  267.18
  5097.7  267.29    5117  268.36  5201.8  267.71  5233.1  269.88  5243.5  272.24
  5266.6  272.53  5274.7   271.2  5300.2  271.71  5338.1  275.58  5388.2  278.07
    5410  276.64    5466  281.42  5487.8  279.26  5508.6  278.85  5537.1   284.5
  5586.5  286.33  5600.7  286.12  5608.2  284.47  5614.9  285.83  5622.5  284.12
  5629.1  285.14  5636.7   284.7  5664.4     290    5699  292.13    5771  295.82
#Mann= 5 ,-1 , 0
  4816.5     .16       0  4980.1     .07       0  4986.1     .16       0
  5338.1      .1       0    5699     .05       0
Bank Sta=4962.3,5117
XS Rating Curve= 0 ,0
Exp/Cntr=0.3,0.1

Type RM Length L Ch R = 1 ,2859    ,826,826,826
BEGIN DESCRIPTION:
UNT05302 IN WICK 5.0
END DESCRIPTION:
XS GIS Cut Line= 4
      3576930.41     10226319.44      3577156.06     10226202.28
      3577394.78     10225863.74      3577360.06     10225629.39
#Sta/Elev= 30
  4548.3   274.5  4665.7  271.73  4696.7  271.64  4732.1  269.97  4792.8  268.48
  4821.7  266.21    4887  263.52  4922.7  263.23  4928.8  262.56  4958.4  263.33
  4979.3  263.03  4986.9  261.89  4991.1  260.32  4993.9  259.82  4997.1  260.32
  5008.9  262.69  5050.7   262.6  5065.5  261.52  5072.5  262.22  5086.4  267.56
  5095.1  269.57    5116   271.5  5122.2  271.05  5158.2  273.44  5187.4  274.21
  5202.2  275.77  5279.6   280.1    5320  283.93  5370.6  287.63  5453.7   291.4
#Mann= 3 ,-1 , 0
  4548.3     .16       0  4991.1     .07       0  4997.1     .16       0
Bank Sta=4991.1,4997.1
XS Rating Curve= 0 ,0
Exp/Cntr=0.3,0.1

Type RM Length L Ch R = 1 ,2033    ,503,503,503
BEGIN DESCRIPTION:
UNT05302 IN WICK 4.0
END DESCRIPTION:
XS GIS Cut Line= 3
      3577145.87     10226557.68      3577663.88     10226454.01
      3577792.12     10226291.62
#Sta/Elev= 30
  4609.1  271.46  4668.4  268.79  4714.3  264.24  4719.4  264.64  4737.8  262.63
  4765.3   260.8  4770.4  261.46  4816.3  258.81  4923.3  258.56  4931.6  257.95
    4952  258.82  4974.3  258.38    5000  255.87  5002.7  255.37    5006  255.87
  5020.2  262.69  5025.3  261.33  5033.6  263.98  5043.8  264.78    5105  266.12
  5115.2  265.95  5122.1  265.03  5127.2  266.67    5140  266.55  5165.9  269.18
    5188  270.55  5202.4   270.5  5219.2  269.52  5258.5  272.19  5344.3  275.44
#Mann= 4 ,-1 , 0
  4609.1     .16       0    5000     .07       0    5006     .16       0
  5219.2      .1       0
Bank Sta=5000,5006
XS Rating Curve= 0 ,0
Exp/Cntr=0.3,0.1

Type RM Length L Ch R = 1 ,1530    ,282,282,282
BEGIN DESCRIPTION:
UNT05302 IN WICK 3.0
END DESCRIPTION:
XS GIS Cut Line= 2
      3577255.85     10226883.71      3577985.05     10226779.54
#Sta/Elev= 30
    4654  265.57  4699.8  263.98  4704.9  264.22  4710.8  263.46  4741.1  262.55
  4761.3  261.17  4807.9   259.7  4882.6  256.45  4902.8  256.09    4917  256.66
  4933.1  255.75  4943.2  256.35  4982.7  256.39  4993.7  254.58  5000.8  251.37
  5003.5  250.87  5006.8  251.37  5013.9   257.3    5024   258.8  5034.1  258.91
  5053.4  261.37  5064.4  262.02  5094.7  263.66  5129.1  264.43  5135.1  265.26
  5194.8  266.73  5205.8  267.76  5306.8  271.08  5347.2  273.13  5390.6  273.36
#Mann= 4 ,-1 , 0
    4654      .1       0  4807.9     .16       0  5000.8     .07       0
  5006.8     .16       0
Bank Sta=5000.8,5006.8
XS Rating Curve= 0 ,0
Exp/Cntr=0.3,0.1

Type RM Length L Ch R = 1 ,1248    ,450,450,450
BEGIN DESCRIPTION:
UNT05302 IN WICK 2.0
END DESCRIPTION:
XS GIS Cut Line= 2
      3577212.47     10227122.42      3577958.03     10227031.39
#Sta/Elev= 30
  4607.5   268.5  4627.3  267.75  4653.8  266.02  4695.3  264.56  4748.2  261.09
  4805.7  258.62    4859  256.36  4909.4  255.42  4929.5  254.27  4979.9  254.01
  4985.1  251.97  4990.1  252.55    4997  251.42  4999.8  250.92    5003  251.42
  5010.1  254.57  5030.3   255.2  5040.3  256.81  5050.4  258.87  5071.7  260.59
  5090.7  260.98  5110.9   262.5  5141.1  263.12  5171.3  264.69  5201.5  265.72
  5234.8  267.53    5272  269.04  5302.3  269.53  5322.4  270.87  5358.6   271.4
#Mann= 5 ,-1 , 0
  4607.5     .16       0  4695.3      .1       0  4805.7     .16       0
    4997     .07       0    5003     .16       0
Bank Sta=4997,5003
XS Rating Curve= 0 ,0
Exp/Cntr=0.3,0.1

Type RM Length L Ch R = 1 ,798     ,419,419,419
BEGIN DESCRIPTION:
Mapping XS 1174ab29
END DESCRIPTION:
XS GIS Cut Line= 2
      3577331.44     10227413.06      3577991.12     10227302.39
#Sta/Elev= 30
    4529  259.91  4560.1  259.15  4571.6  259.37  4627.1  256.66  4641.2  256.73
  4681.8  255.28  4732.5  254.93  4748.4  254.16  4793.3  254.98    4809  254.42
  4814.1  254.94  4869.7  252.82    4915  253.22  4930.3   252.8  4955.5  253.27
  4975.8  253.03  4985.9  252.24    4991  253.07  4996.1  251.88  5003.2     251
    5006   250.5  5009.2     251  5016.4  255.97  5026.5  260.42  5051.6  263.08
  5056.9  264.06  5117.8  267.04  5167.8  267.49  5172.9  267.91  5197.9   267.8
#Mann= 3 ,-1 , 0
    4529     .16       0  5003.2     .07       0  5009.2     .16       0
Bank Sta=5003.2,5009.2
XS Rating Curve= 0 ,0
Exp/Cntr=0.3,0.1

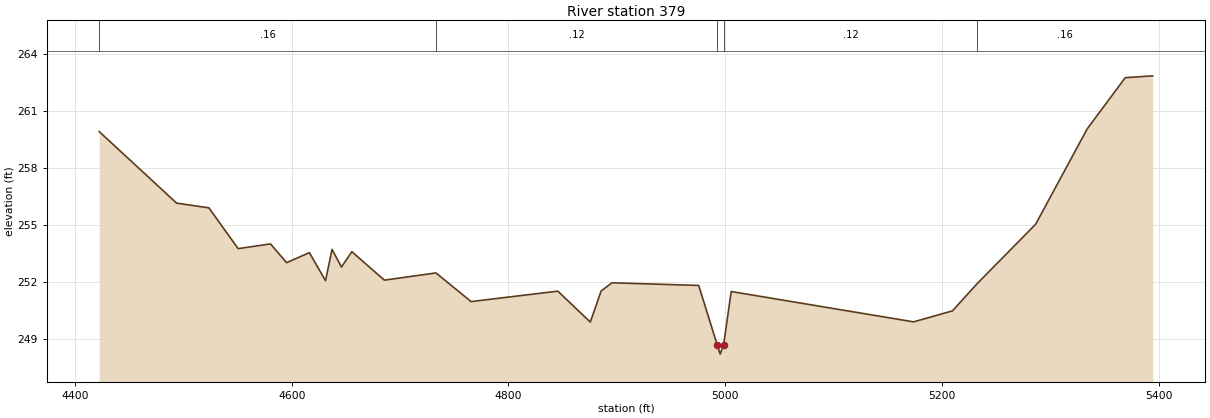
Type RM Length L Ch R = 1 ,379     ,0,0,0
BEGIN DESCRIPTION:
UNT05302 IN WICK 1.0
END DESCRIPTION:
XS GIS Cut Line= 4
      3577297.97     10227465.99      3577426.89     10227653.96
      3577923.85     10227656.13      3578019.36     10227428.23
#Sta/Elev= 30
  4422.4  259.91  4493.8  256.14  4523.6  255.89  4550.6  253.74  4580.4  253.99
  4595.3     253  4616.3  253.53  4631.2  252.05  4637.2   253.7  4645.9  252.77
  4655.5  253.58  4685.5  252.08  4733.1  252.46  4765.5  250.95  4845.5   251.5
  4875.5  249.87  4885.5  251.51  4895.5  251.94  4975.5   251.8  4992.5  248.68
  4995.3  248.18  4998.5  248.68  5005.5  251.48  5173.8  249.88  5209.6  250.46
  5232.5   251.9  5286.4  255.03  5333.9  260.05    5369  262.75  5394.4  262.85
#Mann= 5 ,-1 , 0
  4422.4     .16       0  4733.1     .12       0  4992.5     .07       0
  4998.5     .12       0  5232.5     .16       0
Bank Sta=4992.5,4998.5
XS Rating Curve= 0 ,0
Exp/Cntr=0.3,0.1

Chan Stop Cuts=-1
Use User Specified Reach Order=0
Composite Channel Slope=5