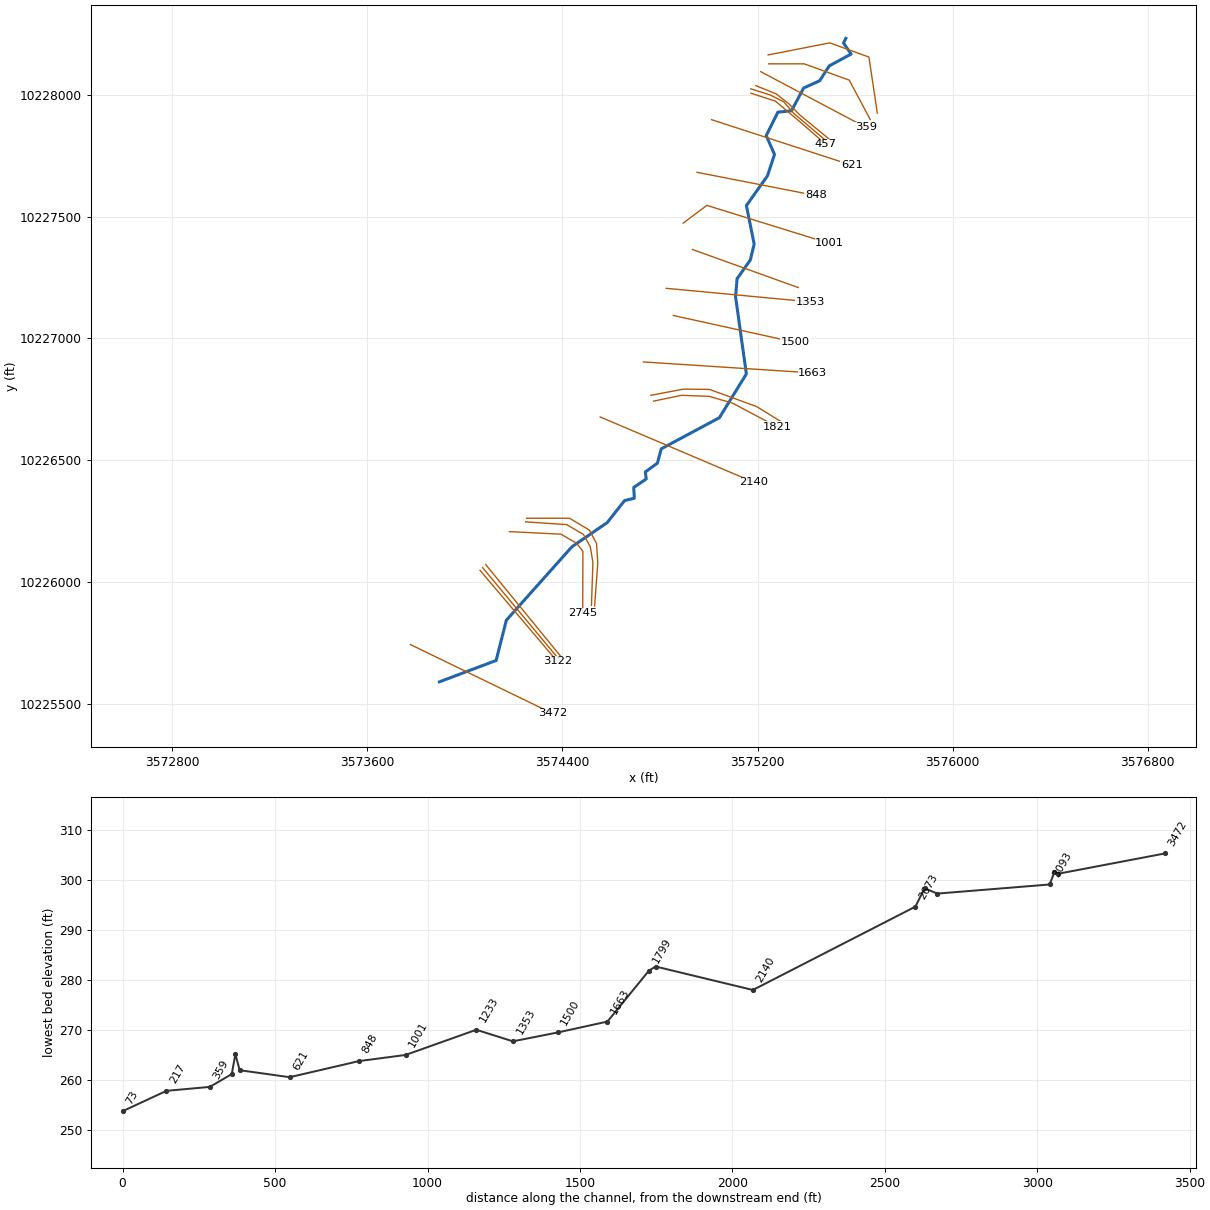
--- BRUSHYCREEKTRIB1.prj (project) ---

Proj Title=BRUSHY CREEK TRIB 12
Current Plan=p01
Default Exp/Contr=0.3,0.1
English Units
Geom File=g01
Flow File=f01
Plan File=p01
Y Axis Title=Elevation
X Axis Title(PF)=Main Channel Distance
X Axis Title(XS)=Station
BEGIN DESCRIPTION:
UNT05301 IN WICK
END DESCRIPTION:
DSS Export Rating Curves= 0
DSS Export Rating Curve Sorted= 0
DSS Export Volume Flow Curves= 0
DXF Filename=UNT05301 IN WICK.
DXF OffsetX= 0
DXF OffsetY= 0
DXF ScaleX= 1
DXF ScaleY= 10

--- BRUSHYCREEKTRIB1.p01 (plan) ---

Plan Title=Multiple Run
Short Identifier=Multiple
Geom File=g01
Flow File=f01
Subcritical Flow
K Sum by GR= 0
Std Step Tol= 0.01
Critical Tol= 0.01
Num of Std Step Trials= 20
Max Error Tol= 0.3
Flow Tol Ratio= 0.001
Split Flow NTrial= 30
Split Flow Tol= 0.02
Split Flow Ratio= 0.02
Log Output Level= 0
Friction Slope Method= 1
Unsteady Friction Slope Method= 2
Unsteady Bridges Friction Slope Method= 1
Parabolic Critical Depth
Global Vel Dist=  1 , 1 , 1
Global Log Level= 0
CheckData=True
Encroach Param= -1, 0, 0, 0
BEGIN DESCRIPTION:
Multiple Run
END DESCRIPTION:

--- BRUSHYCREEKTRIB1.f01 (steady flow) ---

Flow Title=Multiple
Program Version=4.10
Number of Profiles= 7
Profile Names=10-year,25-year,50-year,1pct_min,100-year,1pct_plu,500-year
River Rch & RM=UNT05301 IN WICK,Reach-1         ,3472
     138     169     193     163     220     297     284
River Rch & RM=UNT05301 IN WICK,Reach-1         ,73
     936    1288    1578    1415    1914    2589    2822
River Rch & RM=BRUSHYCRTR12,Reach-1         ,3472
     138     169     193     163     220     297     284
River Rch & RM=BRUSHYCRTR12,Reach-1         ,73
     936    1288    1578    1415    1914    2589    2822
Boundary for River Rch & Prof#=BRUSHYCRTR12,Reach-1         , 1
Up Type= 0
Dn Type= 3
Dn Slope=0.005
Boundary for River Rch & Prof#=BRUSHYCRTR12,Reach-1         , 2
Up Type= 0
Dn Type= 3
Dn Slope=0.005
Boundary for River Rch & Prof#=BRUSHYCRTR12,Reach-1         , 3
Up Type= 0
Dn Type= 3
Dn Slope=0.005
Boundary for River Rch & Prof#=BRUSHYCRTR12,Reach-1         , 4
Up Type= 0
Dn Type= 3
Dn Slope=0.005
Boundary for River Rch & Prof#=BRUSHYCRTR12,Reach-1         , 5
Up Type= 0
Dn Type= 3
Dn Slope=0.005
Boundary for River Rch & Prof#=BRUSHYCRTR12,Reach-1         , 6
Up Type= 0
Dn Type= 3
Dn Slope=0.005
Boundary for River Rch & Prof#=BRUSHYCRTR12,Reach-1         , 7
Up Type= 0
Dn Type= 3
Dn Slope=0.005
DSS Import GetInterval= 0
DSS Import GetPeak= 0
DSS Import FillOption= 0

--- BRUSHYCREEKTRIB1.g01 (geometry) ---

Geom Title=Existing Conditions
Program Version=4.10

River Reach=BRUSHYCRTR12    ,Reach-1
Reach XY= 30
      3573895.73     10225591.23      3574128.36      10225678.9
      3574170.03     10225843.83      3574439.19     10226145.65
      3574583.72     10226244.61      3574654.99     10226335.06
      3574694.92     10226344.61      3574692.31     10226388.88
      3574743.53      10226423.6      3574740.06     10226452.25
      3574789.53     10226488.71      3574805.16      10226547.3
      3575043.44      10226674.9      3575154.12     10226854.59
      3575109.85       10227171.      3575116.12     10227245.49
      3575170.52     10227322.39       3575186.1     10227387.94
      3575154.27     10227545.51      3575240.78     10227667.59
      3575269.43     10227755.26      3575235.57     10227832.52
      3575283.32     10227928.87      3575338.87     10227934.08
      3575389.05     10228027.88      3575454.35     10228057.37
       3575494.1     10228118.67      3575583.66     10228167.25
      3575552.33     10228212.31      3575562.11     10228231.64

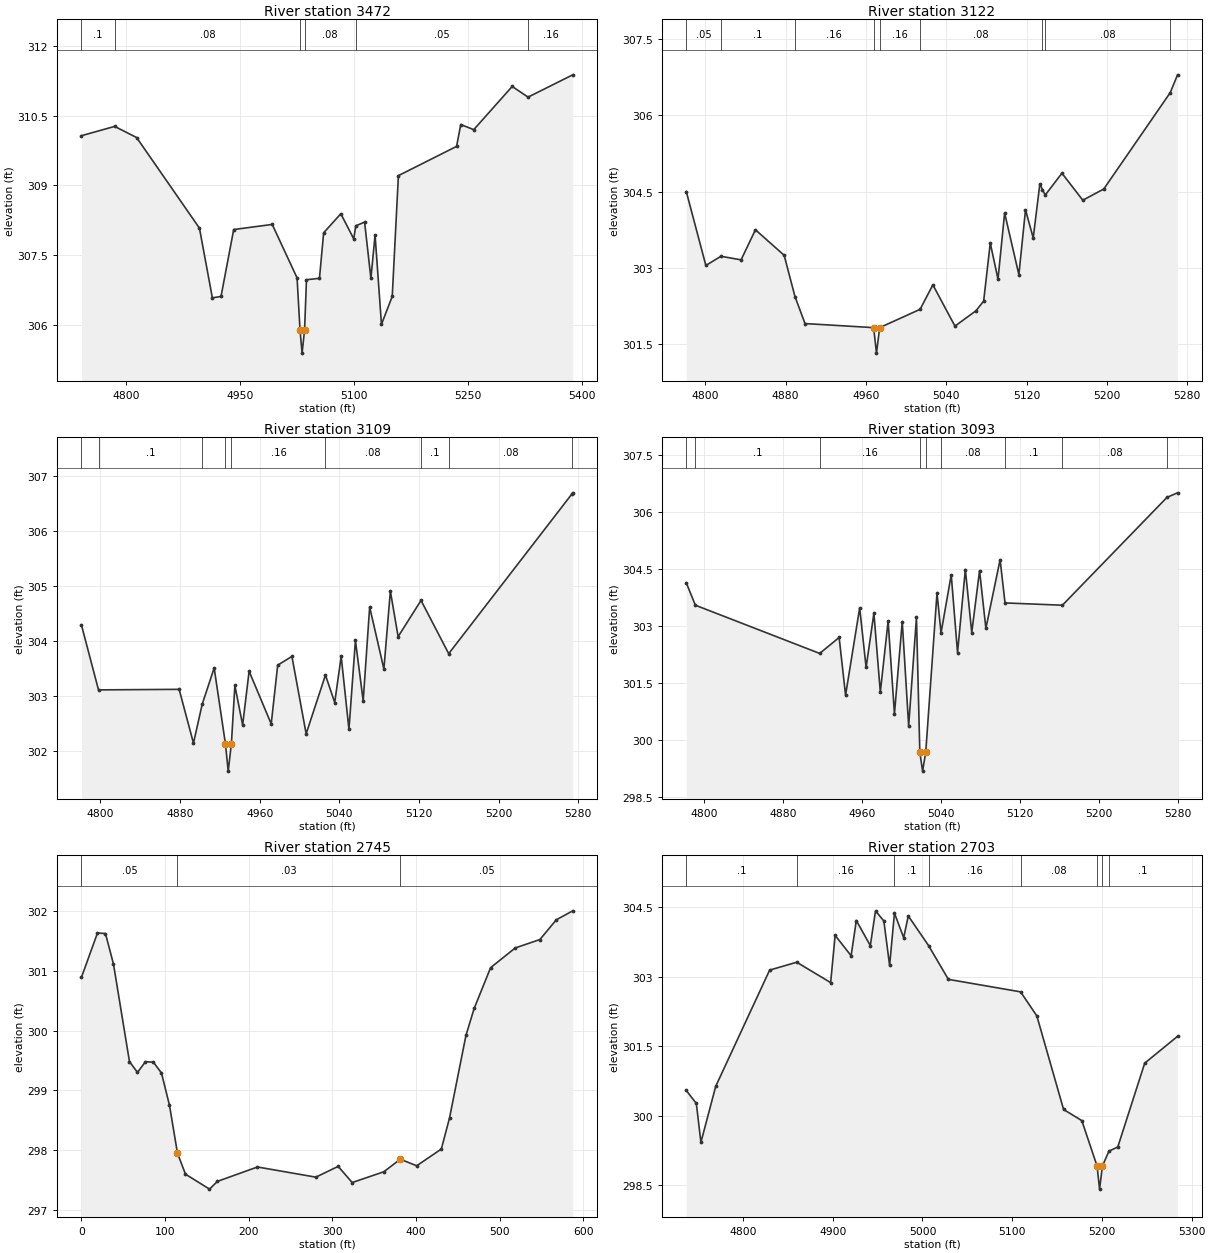
Type RM Length L Ch R = 1 ,3472    ,350,350,350
BEGIN DESCRIPTION:
UNT05301 IN WICK 7.0
END DESCRIPTION:
XS GIS Cut Line= 2
      3573776.81     10225744.16      3574358.61     10225461.79
#Sta/Elev= 30
  4741.1  310.07  4784.8  310.27  4813.7  310.03  4896.4  308.08  4913.4  306.58
  4924.8  306.61  4941.5  308.05  4992.2  308.16  5024.9  307.01  5028.8  305.89
  5031.5  305.39  5034.8  305.89  5037.3  306.97  5054.4     307  5059.9  307.98
  5082.5  308.39  5099.5  307.85  5102.2  308.13  5113.8  308.21  5122.1     307
  5127.6  307.93    5136  306.01  5150.2  306.61  5158.3  309.21  5234.9  309.84
  5240.4  310.31  5257.5   310.2  5308.1  311.13    5329   310.9  5387.8  311.38
#Mann= 6 ,-1 , 0
  4741.1      .1       0  4784.8     .08       0  5028.8     .07       0
  5034.8     .08       0  5102.2     .05       0    5329     .16       0
Bank Sta=5028.8,5034.8
XS Rating Curve= 0 ,0
Exp/Cntr=0.3,0.1

Type RM Length L Ch R = 1 ,3122    ,13,13,13
BEGIN DESCRIPTION:
Mapping XS 5348994c
END DESCRIPTION:
XS GIS Cut Line= 2
      3574062.18     10226048.73       3574378.6     10225675.25
#Sta/Elev= 30
    4781   304.5  4800.5  303.05  4815.5  303.23  4835.6  303.16  4849.9  303.75
  4878.5  303.25  4889.3  302.44  4899.3  301.91  4967.7  301.83  4970.5  301.33
  4973.7  301.83    5014  302.19  5026.7  302.67  5048.7  301.86  5069.6  302.16
  5077.3  302.35  5083.9  303.49  5091.6  302.78  5098.2  304.08  5112.4  302.87
    5119  304.14  5126.7  303.59  5133.3  304.65  5135.9  304.54  5138.6  304.43
  5155.3  304.86  5176.1  304.33    5197  304.55  5263.2  306.44  5270.5  306.79
#Mann= 9 ,-1 , 0
    4781     .05       0  4815.5      .1       0  4889.3     .16       0
  4967.7     .07       0  4973.7     .16       0    5014     .08       0
  5135.9      .1       0  5138.6     .08       0  5263.2     .05       0
Bank Sta=4967.7,4973.7
XS Rating Curve= 0 ,0
Exp/Cntr=0.3,0.1

Type RM Length L Ch R = 1 ,3109    ,16,16,16
BEGIN DESCRIPTION:
Mapping XS 90a5e90e
END DESCRIPTION:
XS GIS Cut Line= 2
       3574072.6     10226060.01      3574388.34     10225680.73
#Sta/Elev= 30
    4781  304.29  4798.1  303.11  4879.1  303.12  4893.5  302.14  4902.3  302.85
  4914.3  303.51  4925.6  302.13  4928.4  301.63  4931.6  302.13  4935.1  303.19
  4942.9  302.47  4949.4  303.45  4971.6  302.49  4978.1  303.56  4992.4  303.72
  5006.7  302.31  5026.1  303.38  5035.4  302.88  5041.9  303.72  5049.7  302.39
  5056.2  304.01    5064  302.91  5070.5  304.62  5084.8  303.49  5091.3  304.91
  5099.1  304.08  5122.1  304.74  5149.9  303.77  5273.7  306.68  5274.5   306.7
#Mann= 9 ,-1 , 0
    4781     .05       0  4798.1      .1       0  4902.3     .16       0
  4925.6     .07       0  4931.6     .16       0  5026.1     .08       0
  5122.1      .1       0  5149.9     .08       0  5273.7     .05       0
Bank Sta=4925.6,4931.6
XS Rating Curve= 0 ,0
Exp/Cntr=0.3,0.1

Type RM Length L Ch R = 1 ,3093    ,368,368,368
BEGIN DESCRIPTION:
Mapping XS dd801f8c
END DESCRIPTION:
XS GIS Cut Line= 2
       3574085.6     10226072.19      3574400.36     10225686.92
#Sta/Elev= 30
  4782.3  304.13  4791.5  303.54  4917.4  302.27  4937.1  302.69  4943.6  301.17
  4957.9  303.47  4964.4   301.9  4972.3  303.33  4978.8  301.25  4986.7  303.12
  4993.1  300.68    5001  303.11  5007.5  300.36  5015.4  303.22  5018.8  299.67
  5021.6  299.17  5024.8  299.67  5036.2  303.86  5040.3  302.81  5050.6  304.34
    5057  302.29  5064.9  304.48  5071.4  302.82  5079.3  304.45  5085.7  302.93
  5100.1  304.74  5105.1   303.6  5163.2  303.54  5269.1  306.38  5279.8   306.5
#Mann= 9 ,-1 , 0
  4782.3     .05       0  4791.5      .1       0  4917.4     .16       0
  5018.8     .07       0  5024.8     .16       0  5040.3     .08       0
  5105.1      .1       0  5163.2     .08       0  5269.1     .05       0
Bank Sta=5018.8,5024.8
XS Rating Curve= 0 ,0
Exp/Cntr=0.3,0.1

Type RM Length L Ch R = 1 ,2745    ,42,42,42
XS GIS Cut Line= 5
     3574182.843    10226207.556      3574393.78    10226197.139
     3574457.148    10226160.681     3574484.058    10226126.827
      3574483.19    10225871.618
#Sta/Elev= 30
       0  300.89   19.12  301.63   28.69  301.62   38.25  301.11   57.37  299.48
   66.94   299.3    76.5  299.48   86.06  299.47   95.62  299.29  105.19  298.75
  114.75  297.95  124.31   297.6     153  297.35  162.56  297.48  210.37  297.72
  280.09  297.55  306.81  297.73  323.57  297.46   361.4  297.64  381.03  297.85
  400.66  297.74  430.11  298.02  439.92  298.54  459.56  299.92  469.37  300.37
     489  301.05  518.45  301.38   547.9  301.52  567.53  301.85  587.16     302
#Mann= 3 , 0 , 0
       0     .05       0  114.75     .03       0  381.03     .05       0
Bank Sta=114.75,381.03
XS Rating Curve= 0 ,0
Exp/Cntr=0.3,0.1

Type RM Length L Ch R = 1 ,2703    ,30,30,30
BEGIN DESCRIPTION:
Mapping XS 354ee174
END DESCRIPTION:
XS GIS Cut Line= 6
      3574249.37     10226247.63      3574417.59     10226236.32
      3574485.95     10226196.17      3574514.16     10226146.26
      3574525.01     10226081.15      3574519.06     10225905.12
#Sta/Elev= 30
  4736.8  300.54    4748  300.26  4753.1  299.42  4769.6  300.63  4829.7  303.14
  4859.9  303.31  4897.7  302.87  4902.7  303.89  4920.5  303.45  4926.3  304.21
  4941.9  303.67  4947.7  304.42    4957   304.2  4963.4  303.24  4968.8  304.37
  4979.1  303.84  4984.2  304.31  5006.8  303.67  5028.9  302.94  5109.4  302.67
  5127.5  302.15  5157.3  300.13  5177.6  299.89  5194.6  298.91  5197.4  298.41
  5200.6  298.91  5207.8  299.23  5217.7  299.32  5247.7  301.13  5284.3  301.71
#Mann= 8 ,-1 , 0
  4736.8      .1       0  4859.9     .16       0  4968.8      .1       0
  5006.8     .16       0  5109.4     .08       0  5194.6     .07       0
  5200.6     .08       0  5207.8      .1       0
Bank Sta=5194.6,5200.6
XS Rating Curve= 0 ,0
Exp/Cntr=0.3,0.1

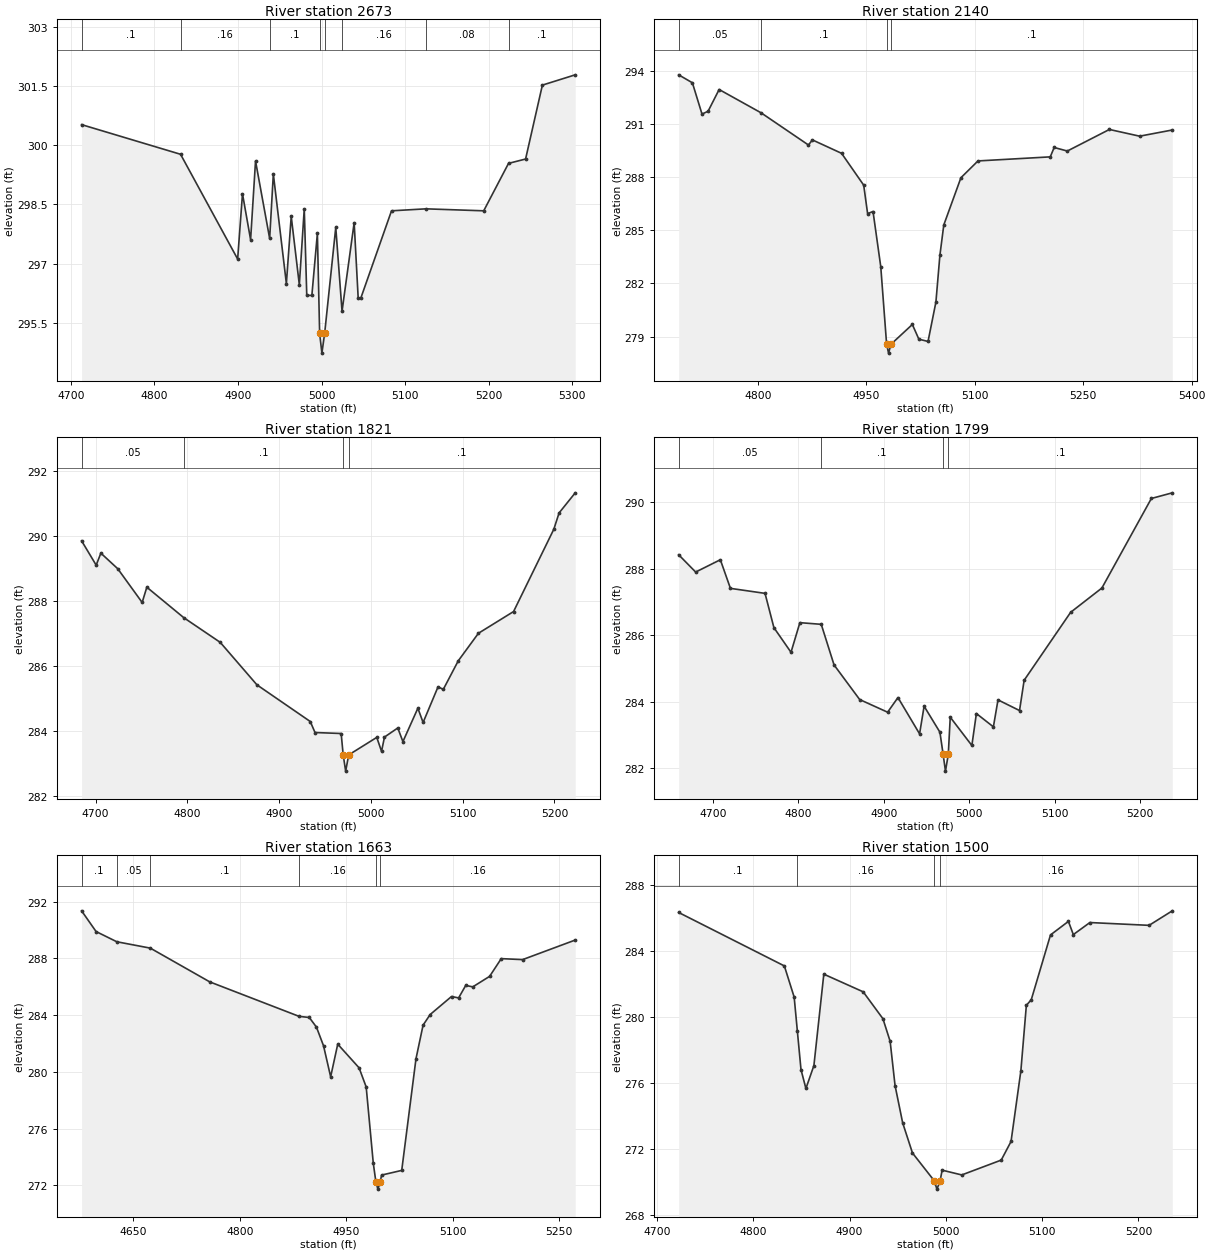
Type RM Length L Ch R = 1 ,2673    ,533,533,533
BEGIN DESCRIPTION:
UNT05301 IN WICK 6.0
END DESCRIPTION:
XS GIS Cut Line= 6
      3574252.82     10226262.39      3574429.53     10226262.36
      3574510.91     10226213.53       3574540.2     10226158.19
      3574545.02     10226077.23      3574531.98     10225902.45
#Sta/Elev= 30
  4712.8  300.52  4831.2  299.77  4899.5  297.12  4905.3  298.77    4915  297.61
  4920.9   299.6  4937.8  297.64  4942.2  299.27  4957.8   296.5  4963.6   298.2
  4973.3  296.47  4979.2  298.39  4982.2   296.2  4988.3   296.2  4994.9  297.77
  4997.6  295.24  5000.3  294.74  5003.6  295.24  5016.9  297.92  5024.4   295.8
  5038.9  298.04  5043.7  296.14    5047  296.14  5083.6  298.34  5124.8  298.39
  5193.9  298.34  5223.6  299.54    5244  299.65  5264.1  301.52  5303.4  301.78
#Mann= 8 ,-1 , 0
  4712.8      .1       0  4831.2     .16       0  4937.8      .1       0
  4997.6     .07       0  5003.6      .1       0  5024.4     .16       0
  5124.8     .08       0  5223.6      .1       0
Bank Sta=4997.6,5003.6
XS Rating Curve= 0 ,0
Exp/Cntr=0.3,0.1

Type RM Length L Ch R = 1 ,2140    ,319,319,319
BEGIN DESCRIPTION:
UNT05301 IN WICK 5.0
END DESCRIPTION:
XS GIS Cut Line= 2
      3574554.65     10226678.16      3575183.05     10226410.83
#Sta/Elev= 30
  4690.3   293.8  4709.3  293.35  4722.6  291.58    4731  291.74  4746.3  292.97
  4804.4  291.65  4869.9  289.83  4875.3  290.12  4915.7  289.36  4946.3  287.56
  4951.7  285.95  4959.2  286.07  4969.9  282.95    4978  278.56  4980.7  278.06
    4984  278.56  5013.6  279.68  5022.6  278.85  5035.3  278.72  5046.2  280.95
  5051.7  283.59  5057.1  285.31  5080.8  287.98  5104.4  288.93  5204.4  289.16
  5209.8  289.69    5228  289.49  5286.2  290.71    5328  290.33  5373.2  290.68
#Mann= 4 ,-1 , 0
  4690.3     .05       0  4804.4      .1       0    4978     .07       0
    4984      .1       0
Bank Sta=4978,4984
XS Rating Curve= 0 ,0
Exp/Cntr=0.3,0.1

Type RM Length L Ch R = 1 ,1821    ,22,22,22
BEGIN DESCRIPTION:
Mapping XS b3c191c1
END DESCRIPTION:
XS GIS Cut Line= 5
       3574773.5     10226743.01      3574888.76     10226766.92
      3575001.11     10226762.62       3575097.2     10226734.89
      3575280.75     10226637.38
#Sta/Elev= 30
  4684.7  289.86  4700.6  289.11  4705.7  289.48  4724.1     289  4750.7  287.96
  4755.8  288.43  4796.1  287.49  4835.8  286.73  4875.8  285.42  4933.9  284.29
  4939.1  283.95  4967.6  283.92  4969.8  283.26  4972.5  282.76  4975.8  283.26
  5006.4   283.8  5011.6  283.37  5014.8  283.81  5029.3  284.09  5034.9  283.67
  5051.2   284.7  5056.9  284.26  5073.2  285.36  5078.9  285.28  5095.2  286.16
  5117.2  287.01  5155.5  287.68  5199.4  290.22  5205.1  290.72  5222.7  291.34
#Mann= 4 ,-1 , 0
  4684.7     .05       0  4796.1      .1       0  4969.8     .07       0
  4975.8      .1       0
Bank Sta=4969.8,4975.8
XS Rating Curve= 0 ,0
Exp/Cntr=0.3,0.1

Type RM Length L Ch R = 1 ,1799    ,136,136,136
BEGIN DESCRIPTION:
Mapping XS 7fbe5035
END DESCRIPTION:
XS GIS Cut Line= 5
      3574762.54     10226766.92      3574896.41     10226792.26
      3575002.06      10226791.3      3575196.64     10226720.55
      3575306.15     10226652.64
#Sta/Elev= 30
  4659.8  288.42  4679.7   287.9  4708.6  288.27  4720.4  287.41  4760.9  287.26
  4771.3  286.23  4791.3  285.49  4801.7  286.38  4826.7  286.33  4841.7  285.11
  4871.7  284.07  4904.4  283.69  4916.5  284.13  4941.8  283.04  4947.1  283.87
  4965.6  283.09  4969.4  282.42  4972.1  281.92  4975.4  282.42  4977.7  283.54
    5003  282.69  5008.3  283.65  5028.2  283.25  5033.6  284.06  5058.8  283.74
  5064.2  284.65  5118.6  286.69  5155.2  287.42  5213.1  290.11  5237.6  290.28
#Mann= 4 ,-1 , 0
  4659.8     .05       0  4826.7      .1       0  4969.4     .07       0
  4975.4      .1       0
Bank Sta=4969.4,4975.4
XS Rating Curve= 0 ,0
Exp/Cntr=0.3,0.1

Type RM Length L Ch R = 1 ,1663    ,163,163,163
BEGIN DESCRIPTION:
UNT05301 IN WICK 4.0
END DESCRIPTION:
XS GIS Cut Line= 2
      3574731.74     10226903.86      3575426.18     10226858.72
#Sta/Elev= 30
    4577  291.36  4597.4   289.9  4626.6  289.18  4673.9  288.73  4757.7  286.35
  4883.6  283.92    4898  283.84  4908.1  283.16  4918.1  281.84  4928.1  279.66
  4938.1  281.96  4968.2  280.29  4978.2  278.94  4988.2  273.57  4991.9  272.24
  4994.7  271.74  4997.9  272.24  4999.9  272.73  5028.3  273.06  5048.4  280.93
  5058.4   283.3  5068.4  284.05  5098.5  285.32  5108.5  285.22  5118.5   286.1
  5128.5     286  5152.2  286.74  5168.6  287.99  5198.7  287.92  5272.9   289.3
#Mann= 6 ,-1 , 0
    4577      .1       0  4626.6     .05       0  4673.9      .1       0
  4883.6     .16       0  4991.9     .07       0  4997.9     .16       0
Bank Sta=4991.9,4997.9
XS Rating Curve= 0 ,0
Exp/Cntr=0.3,0.1

Type RM Length L Ch R = 1 ,1500    ,147,147,147
BEGIN DESCRIPTION:
Mapping XS 4524f28c
END DESCRIPTION:
XS GIS Cut Line= 2
      3574854.87     10227094.39      3575355.68     10226984.16
#Sta/Elev= 30
  4722.4  286.33  4832.2  283.09  4842.4   281.2  4845.7  279.15  4849.5   276.8
  4854.6  275.66  4862.9  277.05  4873.2  282.59  4914.1  281.52  4934.6  279.89
  4942.1  278.52  4947.2  275.84  4955.1  273.58  4965.3  271.75    4988  270.06
  4990.7  269.56    4994  270.06  4996.1  270.71  5016.5  270.42  5057.5  271.32
  5067.7  272.45  5077.9  276.73  5083.6   280.7  5088.7  281.04  5108.7  284.97
  5127.3  285.79  5132.4  284.99  5149.6  285.72  5211.1  285.55  5235.2  286.43
#Mann= 4 ,-1 , 0
  4722.4      .1       0  4845.7     .16       0    4988     .07       0
    4994     .16       0
Bank Sta=4988,4994
XS Rating Curve= 0 ,0
Exp/Cntr=0.3,0.1

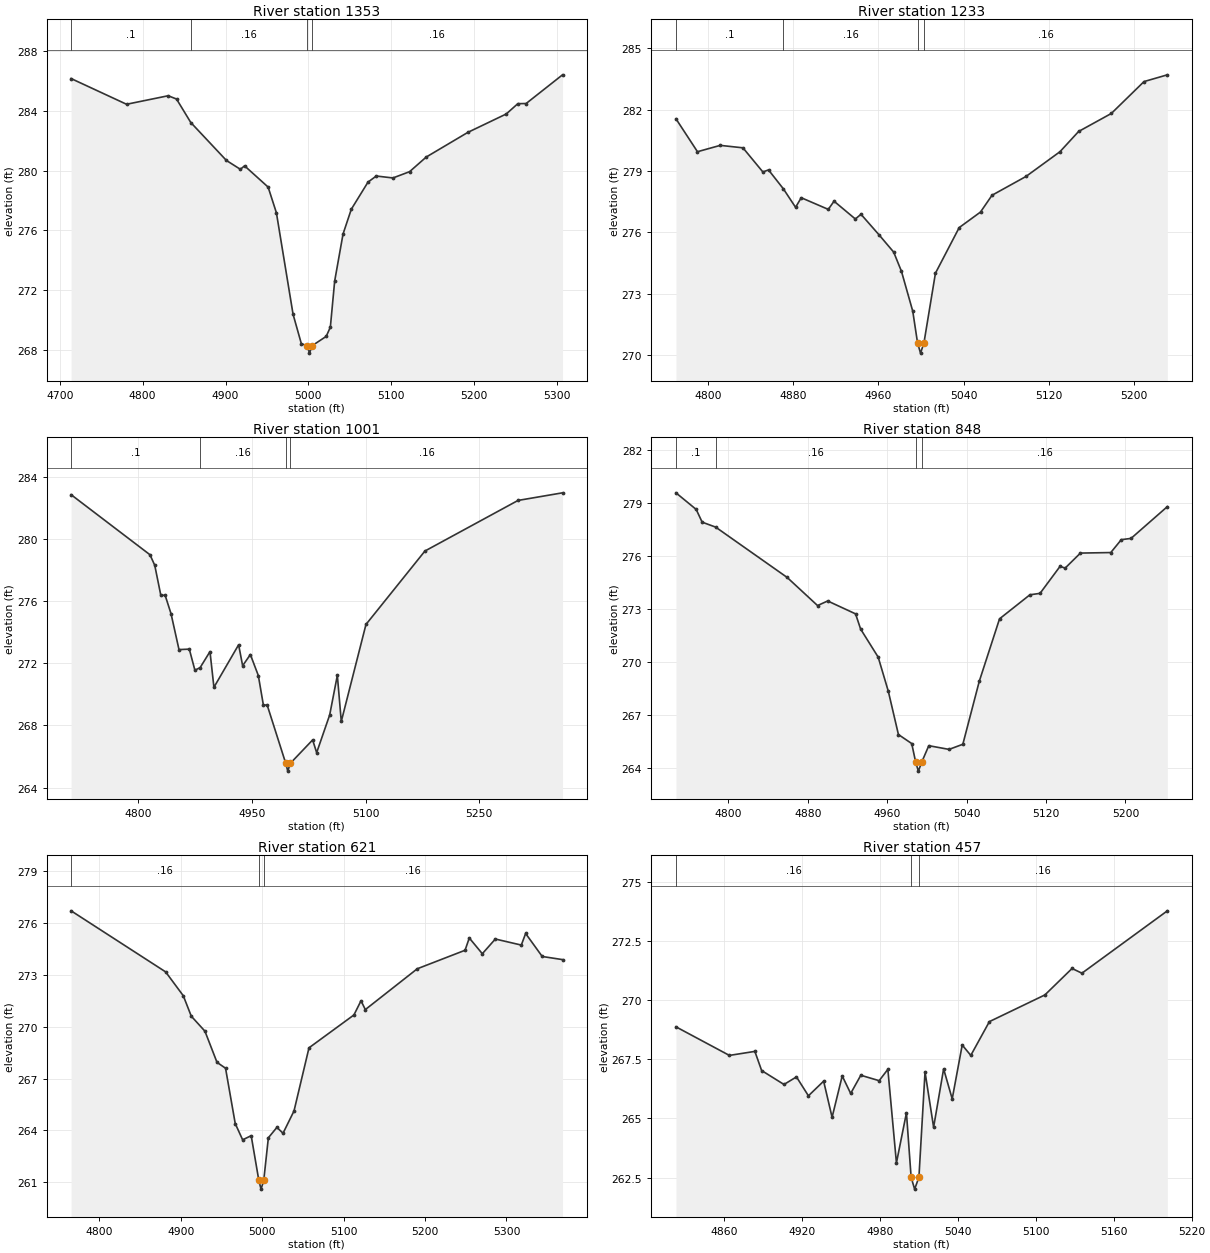
Type RM Length L Ch R = 1 ,1353    ,120,120,120
BEGIN DESCRIPTION:
UNT05301 IN WICK 3.0
END DESCRIPTION:
XS GIS Cut Line= 2
      3574825.49     10227205.94      3575415.78     10227150.39
#Sta/Elev= 30
  4713.7  286.16  4780.6  284.44  4830.8  285.01  4840.9  284.79  4858.1  283.22
  4901.1  280.68  4917.9  280.09    4923  280.32  4951.4   278.9  4961.4  277.18
  4981.5  270.39  4991.5  268.42  4998.6  268.29  5001.3  267.79  5004.6  268.29
  5021.5  268.91  5026.5  269.53  5031.7  272.61  5041.8  275.76  5051.8  277.42
  5071.9  279.23  5081.9  279.64    5102  279.51  5122.1  279.93  5142.2  280.91
  5192.4  282.56  5238.7  283.79  5252.7  284.48  5262.7  284.49  5306.6  286.41
#Mann= 4 ,-1 , 0
  4713.7      .1       0  4858.1     .16       0  4998.6     .07       0
  5004.6     .16       0
Bank Sta=4998.6,5004.6
XS Rating Curve= 0 ,0
Exp/Cntr=0.3,0.1

Type RM Length L Ch R = 1 ,1233    ,232,232,232
BEGIN DESCRIPTION:
Mapping XS 574c4efa
END DESCRIPTION:
XS GIS Cut Line= 2
      3574932.93     10227365.24      3575366.96     10227208.99
#Sta/Elev= 30
  4769.9  281.56  4790.1  279.95  4811.5  280.26  4832.8  280.14  4851.5  278.96
  4856.8  279.06  4870.8  278.13  4882.2  277.23  4887.5   277.7  4912.9  277.13
  4918.3  277.53  4938.3  276.66  4943.6  276.89  4960.3   275.9  4974.3  275.04
  4981.6   274.1  4992.2  272.15  4996.7   270.6  4999.5   270.1  5002.7   270.6
  5013.5  274.01  5035.8  276.24  5055.8     277  5066.6  277.82  5098.5  278.74
  5130.4  279.95  5147.9  280.94  5178.6  281.82  5209.3  283.38  5231.2  283.71
#Mann= 4 ,-1 , 0
  4769.9      .1       0  4870.8     .16       0  4996.7     .07       0
  5002.7     .16       0
Bank Sta=4996.7,5002.7
XS Rating Curve= 0 ,0
Exp/Cntr=0.3,0.1

Type RM Length L Ch R = 1 ,1001    ,153,153,153
BEGIN DESCRIPTION:
UNT05301 IN WICK 2.0
END DESCRIPTION:
XS GIS Cut Line= 3
      3574894.93     10227473.33      3574992.12     10227546.22
      3575495.55     10227389.99
#Sta/Elev= 30
  4711.4  282.87  4815.5     279  4821.8  278.32  4829.8  276.39  4835.5  276.39
  4843.3   275.2  4853.8  272.89  4867.4  272.92  4874.8  271.56  4881.7  271.73
  4894.7  272.76  4899.9  270.46  4932.5   273.2  4937.8  271.85    4948  272.57
  4958.5  271.22  4965.1  269.34  4970.3   269.3  4994.7  265.56  4997.4  265.06
  5000.7  265.56  5030.2  267.07  5035.5  266.25  5052.7  268.68  5062.8  271.23
    5068  268.26  5100.6  274.51  5178.4  279.24  5301.3   282.5    5360  282.99
#Mann= 4 ,-1 , 0
  4711.4      .1       0  4881.7     .16       0  4994.7     .07       0
  5000.7     .16       0
Bank Sta=4994.7,5000.7
XS Rating Curve= 0 ,0
Exp/Cntr=0.3,0.1

Type RM Length L Ch R = 1 ,848     ,227,227,227
BEGIN DESCRIPTION:
Mapping XS a975aaa6
END DESCRIPTION:
XS GIS Cut Line= 2
      3574952.07     10227681.87      3575438.06     10227586.84
#Sta/Elev= 30
  4747.1  279.58  4767.5  278.64  4773.5  277.92  4787.1  277.64  4859.2  274.79
  4889.8   273.2    4900  273.46  4928.1  272.73  4933.2  271.87  4950.9  270.28
  4961.1  268.35  4971.3   265.9  4984.7  265.39  4988.7  264.33  4991.4  263.83
  4994.7  264.33  5001.9  265.27  5022.3  265.06  5036.2  265.35  5052.8  268.92
  5073.2  272.45  5103.8  273.81    5114  273.89  5134.2  275.42  5139.3  275.32
  5154.7  276.17  5185.3   276.2  5195.9  276.93  5205.7     277  5242.3   278.8
#Mann= 4 ,-1 , 0
  4747.1      .1       0  4787.1     .16       0  4988.7     .07       0
  4994.7     .16       0
Bank Sta=4988.7,4994.7
XS Rating Curve= 0 ,0
Exp/Cntr=0.3,0.1

Type RM Length L Ch R = 1 ,621     ,164,164,164
BEGIN DESCRIPTION:
Mapping XS 55235f8f
END DESCRIPTION:
XS GIS Cut Line= 2
      3575011.72     10227897.81      3575585.74     10227711.18
#Sta/Elev= 30
  4765.2   276.7  4881.3  273.17    4903  271.79  4912.8  270.61  4929.6  269.74
  4944.4  267.94  4954.9   267.6  4966.8   264.4  4975.9  263.46  4986.4   263.7
  4995.8  261.11  4998.5  260.61  5001.8  261.11  5007.5  263.58    5018  264.18
  5025.5  263.84    5039  265.13  5057.4  268.78  5112.6  270.68  5121.3   271.5
  5126.6  270.99  5190.4  273.35  5249.1  274.42  5254.3  275.13  5270.3  274.22
  5286.3  275.07  5318.2  274.72  5323.5  275.39  5343.9  274.06  5368.8  273.88
#Mann= 3 ,-1 , 0
  4765.2     .16       0  4995.8     .07       0  5001.8     .16       0
Bank Sta=4995.8,5001.8
XS Rating Curve= 0 ,0
Exp/Cntr=0.3,0.1

Type RM Length L Ch R = 1 ,457     ,14,14,14
BEGIN DESCRIPTION:
Mapping XS d17a9d77
END DESCRIPTION:
XS GIS Cut Line= 4
      3575172.99     10228006.39      3575272.83     10227974.27
      3575377.87     10227885.72      3575480.13     10227796.46
#Sta/Elev= 30
  4823.2  268.88  4864.3  267.67  4883.9  267.84  4889.1  267.03  4906.3  266.44
  4915.9  266.76  4925.1  265.96  4936.8  266.58  4943.3  265.05  4951.1   266.8
  4957.6  266.06  4965.4  266.83  4979.5   266.6  4986.2  267.08  4992.8  263.12
  5000.5  265.24  5004.1  262.51  5006.8  262.01  5010.1  262.51  5014.8  266.97
  5021.4  264.63  5029.1   267.1  5035.7  265.83  5043.4  268.11    5050  267.67
  5064.3   269.1    5107  270.23  5127.9  271.35  5135.5  271.15  5201.2  273.79
#Mann= 3 ,-1 , 0
  4823.2     .16       0  5004.1     .07       0  5010.1     .16       0
Bank Sta=5004.1,5010.1
XS Rating Curve= 0 ,0
Exp/Cntr=0.3,0.1

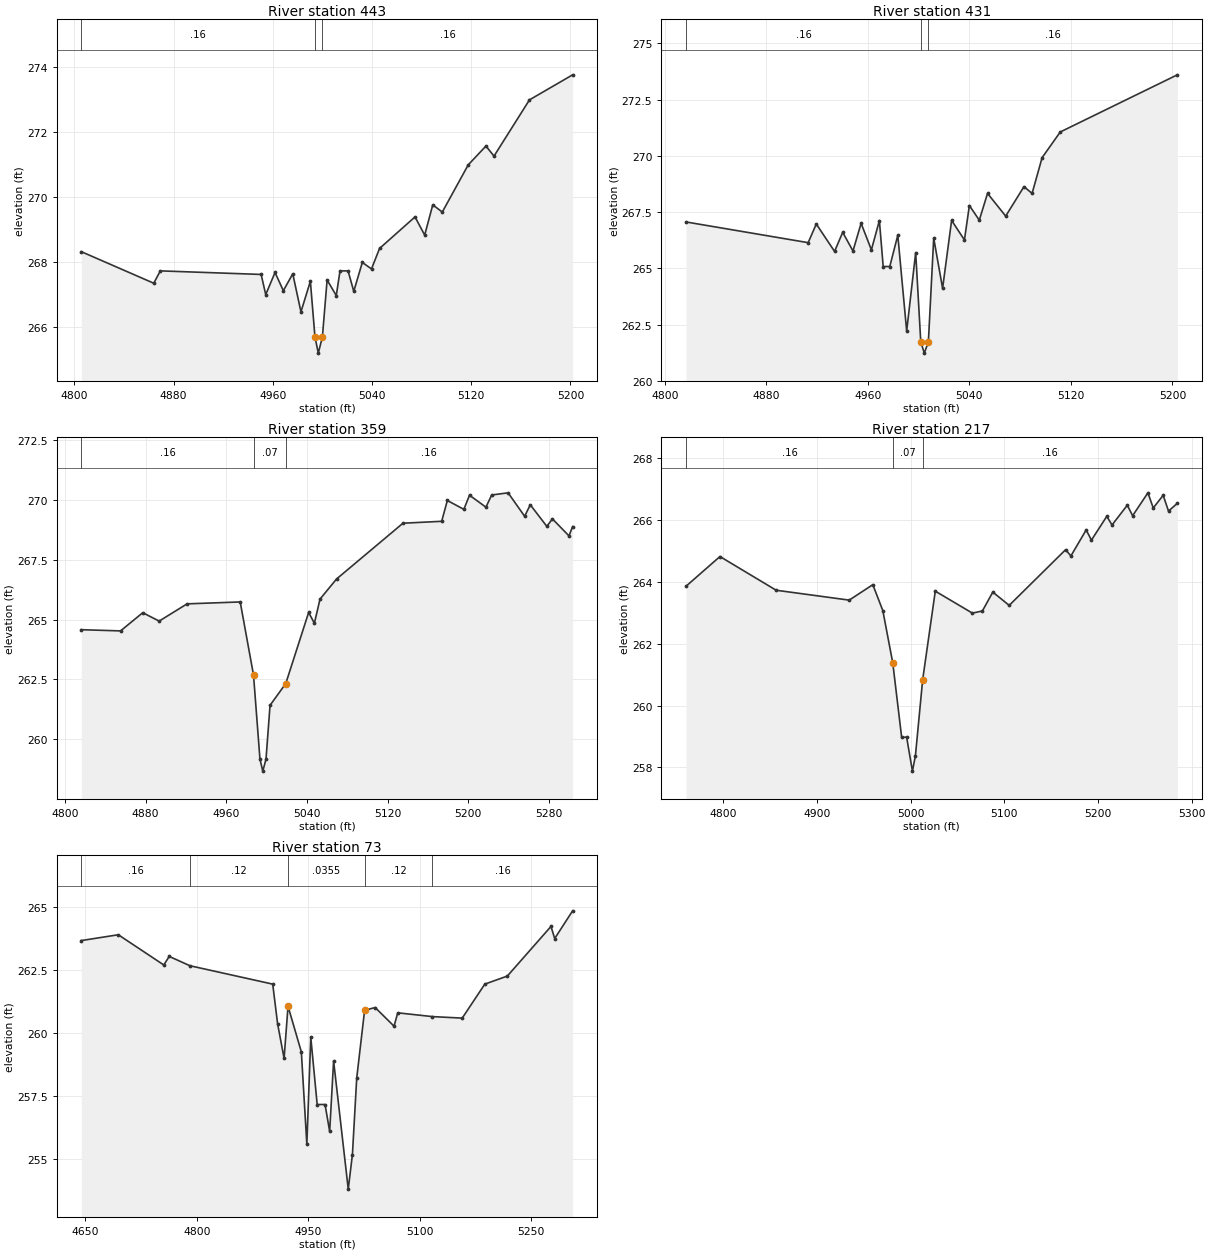
Type RM Length L Ch R = 1 ,443     ,12,12,12
BEGIN DESCRIPTION:
Mapping XS 9c16b87b
END DESCRIPTION:
XS GIS Cut Line= 5
      3575172.16     10228024.61      3575251.13     10227999.44
      3575306.69     10227971.66      3575350.09     10227922.18
      3575491.58      10227802.4
#Sta/Elev= 30
  4805.6  268.32    4864  267.35  4869.3  267.73  4950.6  267.62  4954.3     267
  4961.8  267.68  4968.5  267.12  4976.1  267.64  4982.7  266.47  4990.3  267.41
    4994   265.7  4996.7   265.2    5000   265.7  5003.8  267.45  5011.2  266.97
  5014.2  267.73  5020.7  267.73  5025.3   267.1  5032.2  267.99  5039.6  267.79
  5046.1  268.42  5074.7  269.39  5082.5  268.83    5089  269.76  5096.7  269.54
  5117.6  270.99  5131.9  271.57  5138.4  271.26    5167  272.99  5201.8  273.76
#Mann= 3 ,-1 , 0
  4805.6     .16       0    4994     .07       0    5000     .16       0
Bank Sta=4994,5000
XS Rating Curve= 0 ,0
Exp/Cntr=0.3,0.1

Type RM Length L Ch R = 1 ,431     ,72,72,72
BEGIN DESCRIPTION:
Mapping XS d2a85d42
END DESCRIPTION:
XS GIS Cut Line= 5
      3575192.98     10228037.63       3575276.3     10228003.78
      3575328.39     10227962.98      3575372.66     10227917.84
      3575501.97      10227811.1
#Sta/Elev= 30
  4816.8  267.06    4913  266.14  4919.4  266.97  4933.8  265.75  4940.2   266.6
  4948.3  265.77  4954.7     267  4962.8  265.82  4969.1  267.12  4972.1  265.08
  4977.3  265.08  4983.6  266.47  4990.6  262.21  4997.7   265.7  5001.7  261.73
  5004.5  261.23  5007.7  261.73  5011.9  266.34  5018.9  264.11    5026  267.13
  5036.1  266.26    5040  267.79  5047.8  267.14  5054.3  268.33  5068.6  267.32
    5083  268.63  5089.4  268.33  5097.3  269.92  5111.6  271.06  5203.8   273.6
#Mann= 3 ,-1 , 0
  4816.8     .16       0  5001.7     .07       0  5007.7     .16       0
Bank Sta=5001.7,5007.7
XS Rating Curve= 0 ,0
Exp/Cntr=0.3,0.1

Type RM Length L Ch R = 1 ,359     ,142,142,142
BEGIN DESCRIPTION:
Mapping XS e6331fbd
END DESCRIPTION:
XS GIS Cut Line= 2
       3575212.9     10228094.95      3575643.51     10227866.62
#Sta/Elev= 30
  4816.2  264.58  4855.1  264.53  4877.1  265.29  4893.4  264.94  4921.1  265.66
  4973.8  265.74    4987  262.69  4993.4  259.17  4996.2  258.67  4999.4  259.17
  5003.4  261.42    5019  262.33  5041.7   265.3  5047.4  264.85    5053  265.86
  5069.4   266.7  5135.3  269.03  5173.7  269.11  5179.3  269.98  5195.7  269.61
  5201.3   270.2  5217.6   269.7  5223.3  270.21  5239.6   270.3    5256  269.32
  5261.6   269.8    5278   268.9  5283.6  269.21    5300   268.5  5303.6  268.89
#Mann= 3 , 0 , 0
  4816.2     .16       0    4987     .07       0    5019     .16       0
Bank Sta=4987,5019
XS Rating Curve= 0 ,0
Exp/Cntr=0.3,0.1

Type RM Length L Ch R = 1 ,217     ,144,144,144
BEGIN DESCRIPTION:
Mapping XS d9aa38f8
END DESCRIPTION:
XS GIS Cut Line= 4
      3575245.95     10228127.04      3575390.89     10228127.04
      3575575.78      10228060.2      3575661.74      10227898.7
#Sta/Elev= 30
  4760.2  263.86  4796.4  264.82  4856.4  263.73  4934.4  263.41  4959.6  263.91
  4970.3  263.07  4980.9  261.38  4990.4  258.97  4995.7  258.98  5001.9  257.88
  5005.1  258.38  5012.8  260.83  5026.3   263.7  5065.9  262.99  5076.6  263.06
  5087.7  263.67  5105.2  263.24  5165.4  265.04  5171.1  264.84  5187.4  265.68
    5193  265.35  5209.4  266.12    5215  265.84  5231.3  266.48    5237  266.14
  5253.3  266.88    5259  266.39  5269.6   266.8  5275.3  266.29  5284.7  266.54
#Mann= 3 , 0 , 0
  4760.2     .16       0  4980.9     .07       0  5012.8     .16       0
Bank Sta=4980.9,5012.8
XS Rating Curve= 0 ,0
Exp/Cntr=0.3,0.1

Type RM Length L Ch R = 1 ,73      ,0,0,0
BEGIN DESCRIPTION:
UNT05301 IN WICK 1.0
END DESCRIPTION:
XS GIS Cut Line= 4
      3575243.29      10228163.5      3575495.92     10228212.98
      3575656.51     10228154.82      3575690.97     10227924.82
#Sta/Elev= 30
  4644.8  263.67  4694.5   263.9  4755.7   262.7    4763  263.04  4790.8  262.67
  4902.2  261.94  4908.8  260.36  4917.5  258.99  4922.8  261.06  4940.7  259.25
  4948.1  255.58  4953.4  259.83    4962  257.16  4972.6  257.16  4978.8  256.09
  4984.1  258.89  5003.8   253.8  5009.4  255.17  5015.2  258.21  5025.8   260.9
    5040  261.01  5065.4  260.27  5070.4   260.8  5117.1  260.65  5157.1  260.59
  5187.5  261.94  5217.8  262.26  5276.5  264.23  5281.5  263.75  5305.6  264.85
#Mann= 5 ,-1 , 0
  4644.8     .16       0  4790.8     .12       0  4922.8   .0355       0
  5025.8     .12       0  5117.1     .16       0
Bank Sta=4922.8,5025.8
XS Rating Curve= 0 ,0
Exp/Cntr=0.3,0.1

Chan Stop Cuts=-1
Use User Specified Reach Order=0
Composite Channel Slope=5