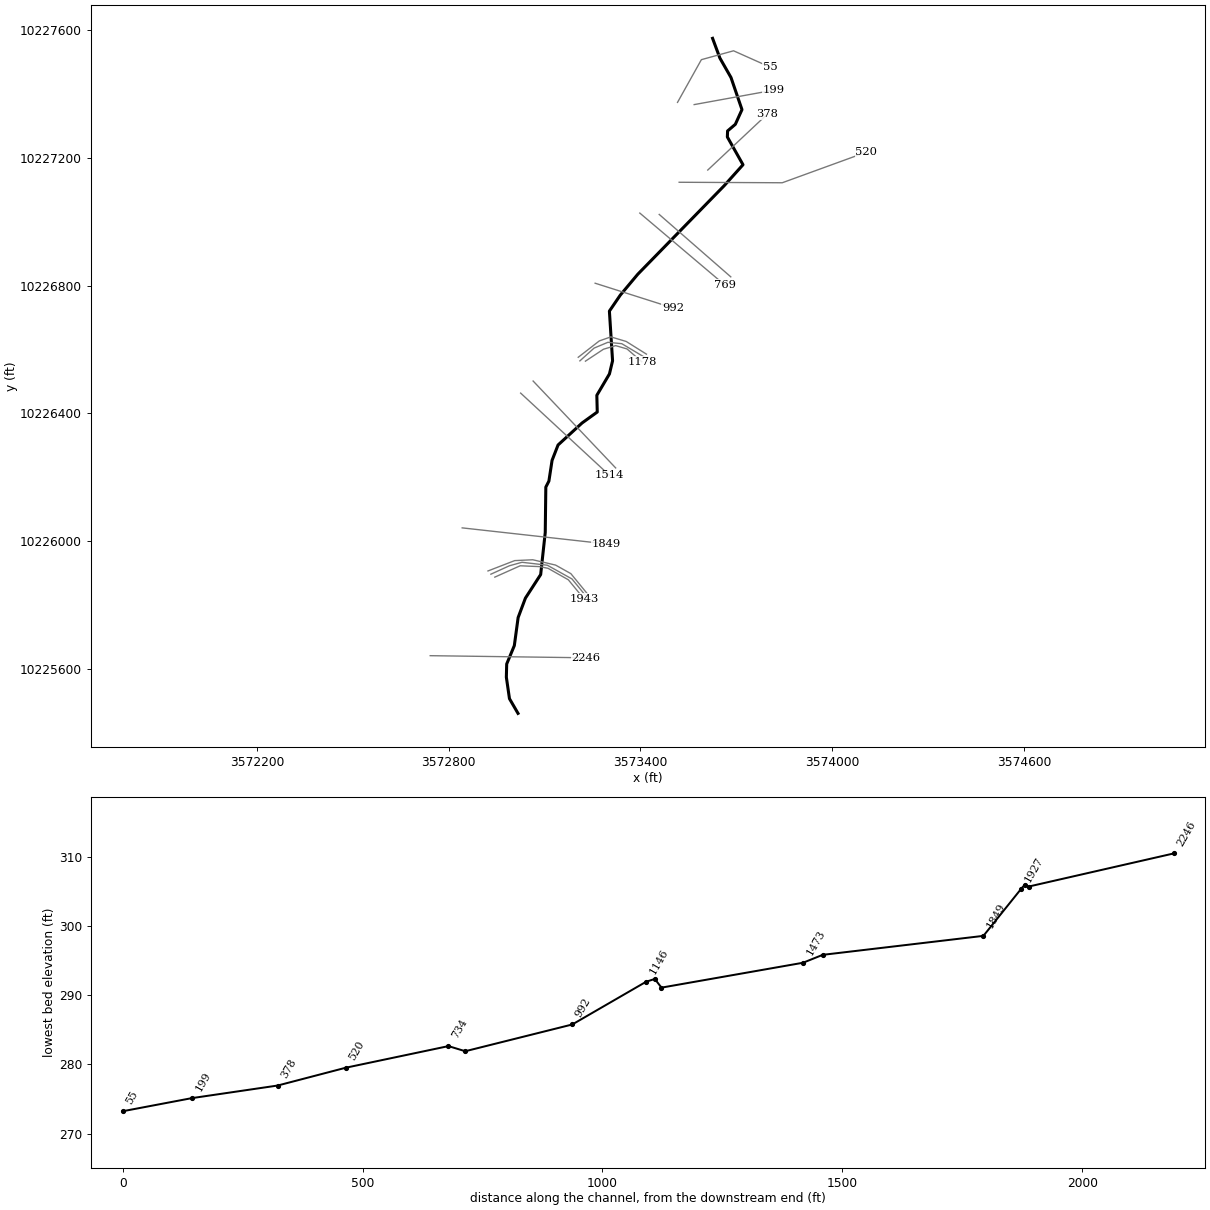
--- BRUSHYCREEKTRIB1.prj (project) ---

Proj Title=BRUSHY CREEK TRIB 13 1
Current Plan=p01
Default Exp/Contr=0.3,0.1
English Units
Geom File=g01
Flow File=f01
Plan File=p01
Y Axis Title=Elevation
X Axis Title(PF)=Main Channel Distance
X Axis Title(XS)=Station
BEGIN DESCRIPTION:
UNT116 IN WICK
END DESCRIPTION:
DSS Export Rating Curves= 0
DSS Export Rating Curve Sorted= 0
DSS Export Volume Flow Curves= 0
DXF Filename=UNT116 IN WICK.
DXF OffsetX= 0
DXF OffsetY= 0
DXF ScaleX= 1
DXF ScaleY= 10

--- BRUSHYCREEKTRIB1.p01 (plan) ---

Plan Title=Multiple Run
Program Version=4.10
Short Identifier=Multiple Run
Geom File=g01
Flow File=f01
Subcritical Flow
K Sum by GR= 0
Std Step Tol= 0.01
Critical Tol= 0.01
Num of Std Step Trials= 20
Max Error Tol= 0.3
Flow Tol Ratio= 0.001
Split Flow NTrial= 30
Split Flow Tol= 0.02
Split Flow Ratio= 0.02
Log Output Level= 0
Friction Slope Method= 1
Unsteady Friction Slope Method= 2
Unsteady Bridges Friction Slope Method= 1
Parabolic Critical Depth
Global Vel Dist= 1 , 1 , 1
Global Log Level= 0
CheckData=True
Encroach Param=-1 ,0,0, 0
BEGIN DESCRIPTION:
Multiple Run
END DESCRIPTION:
Computation Interval=1HOUR
Output Interval=1HOUR
Run HTab= 0
Run UNet= 0
Run PostProcess= 0
Run WQNet= 0
UNET Theta= 1
UNET Theta Warmup= 1
UNET ZTol= 0.02
UNET ZSATol= 0.05
UNET MxIter= 20
UNET MaxInSteps= 0
UNET DtIC= 0
UNET DtMin= 0
UNET MaxCRTS= 20
UNET WFStab= 2
UNET SFStab= 1
UNET WFX= 1
UNET SFX= 1
UNET DSS MLevel= 4
UNET DZMax Abort= 100
UNET Convert EG Bridges= 0
UNET Use Existing IB Tables=-1
UNET Froude Reduction=False
UNET Froude Limit= 1
UNET Froude Power= 10
UNET Time Slicing=0,0, 5
UNET Junction Losses=0
Instantaneous Interval=1HOUR
DSS File=dss
Write IC File= 0
Write IC File at Sim End=0
Echo Input=False
Echo Parameters=False
Echo Output=False
Write Detailed= 0
WQ AD Non Conservative
WQ ULTIMATE=-1
WQ Max Comp Step=1HOUR
WQ Output Interval=15MIN
WQ Output Selected Increments= 0
WQ Output face flow=0
WQ Output face velocity=0
WQ Output face area=0
WQ Output face dispersion=0
WQ Output cell volume=0
WQ Output cell surface area=0
WQ Output cell continuity=0
WQ Output cumulative cell continuity=0
WQ Output face conc=0
WQ Output face dconc_dx=0
WQ Output face courant=0
WQ Output face peclet=0
WQ Output face adv mass=0
WQ Output face disp mass=0
WQ Output cell mass=0
WQ Output cell source sink temp=0
WQ Output cell source sink nsm=0
WQ Output MaxMinRange=-1
WQ Daily Max Min Mean=-1
WQ Daily Range=0
WQ Daily Time=0
WQ Create Restart=0
WQ Fixed Restart=0
WQ System Summary=0
WQ Use Fixed Temperature=0
Sorting and Armoring Iterations= 10
XS Update Threshold= 0.02
Hydraulics Update Threshold= 0.02
Energy Slope Method= 1
Volume Change Method= 0
XS Weighting Method= 0
Number of US Weighted Cross Sections= 1
Number of DS Weighted Cross Sections= 1
Upstream XS Weight=0.25
Main XS Weight=0.5
Downstream XS Weight=0.25
Number of DS XS's Weighted with US Boundary= 1
Upstream Boundary Weight= 1
Weight of XSs Associated with US Boundary= 0
Number of US XS's Weighted with DS Boundary= 1
Downstream Boundary Weight= 0.5
Weight of XSs Associated with DS Boundary= 0.5
Sediment Output Level= 4
Mass or Volume Output= 0
Output Increment Type= 1
Profile and TS Output Increment= 10
XS Output Flag= 0
XS Output Increment= 10
Disregard all LS=0
Disregard all Conn=0
Disregard all Breaches=0
Disregard all Pumps=0

--- BRUSHYCREEKTRIB1.f01 (steady flow) ---

Flow Title=Multiple
Program Version=4.10
Number of Profiles= 7
Profile Names=10-year,25-year,50-year,1pct_min,100-year,1pct_plu,500-year
River Rch & RM=UNT116 IN WICK,Reach-1         ,2246
     114     139     157     131     177     240     226
River Rch & RM=BRUSHYCRTR131,Reach-1         ,2246
     114     139     157     131     177     240     226
Boundary for River Rch & Prof#=BRUSHYCRTR131,Reach-1         , 1
Up Type= 0
Dn Type= 3
Dn Slope=0.0106
Boundary for River Rch & Prof#=BRUSHYCRTR131,Reach-1         , 2
Up Type= 0
Dn Type= 3
Dn Slope=0.0106
Boundary for River Rch & Prof#=BRUSHYCRTR131,Reach-1         , 3
Up Type= 0
Dn Type= 3
Dn Slope=0.0106
Boundary for River Rch & Prof#=BRUSHYCRTR131,Reach-1         , 4
Up Type= 0
Dn Type= 3
Dn Slope=0.0106
Boundary for River Rch & Prof#=BRUSHYCRTR131,Reach-1         , 5
Up Type= 0
Dn Type= 3
Dn Slope=0.0106
Boundary for River Rch & Prof#=BRUSHYCRTR131,Reach-1         , 6
Up Type= 0
Dn Type= 3
Dn Slope=0.0106
Boundary for River Rch & Prof#=BRUSHYCRTR131,Reach-1         , 7
Up Type= 0
Dn Type= 3
Dn Slope=0.0106
DSS Import GetInterval= 0
DSS Import GetPeak= 0
DSS Import FillOption= 0

--- BRUSHYCREEKTRIB1.g01 (geometry) ---

Geom Title=Existing Conditions
Program Version=4.10

River Reach=BRUSHYCRTR131   ,Reach-1
Reach XY= 30
      3573016.84     10225461.07      3572990.11     10225507.09
      3572980.35     10225574.37      3572981.43      10225615.6
       3573005.3     10225673.11      3573017.24       10225761.
      3573040.03     10225821.76      3573087.77     10225895.55
      3573102.08      10226027.1       3573103.9     10226169.29
      3573113.53     10226188.04      3573123.43     10226252.88
      3573142.18     10226301.06      3573217.18     10226369.81
      3573264.87     10226404.18      3573263.53     10226456.53
      3573303.02     10226523.48      3573312.79     10226564.57
      3573302.86     10226720.07      3573336.97     10226770.07
      3573391.66     10226835.43      3573662.15     10227112.56
        3573721.     10227178.18      3573672.04     10227264.99
      3573672.74     10227283.91      3573696.97     10227304.61
       3573717.8     10227350.61      3573683.43     10227451.13
       3573648.7      10227511.9      3573625.77     10227573.74

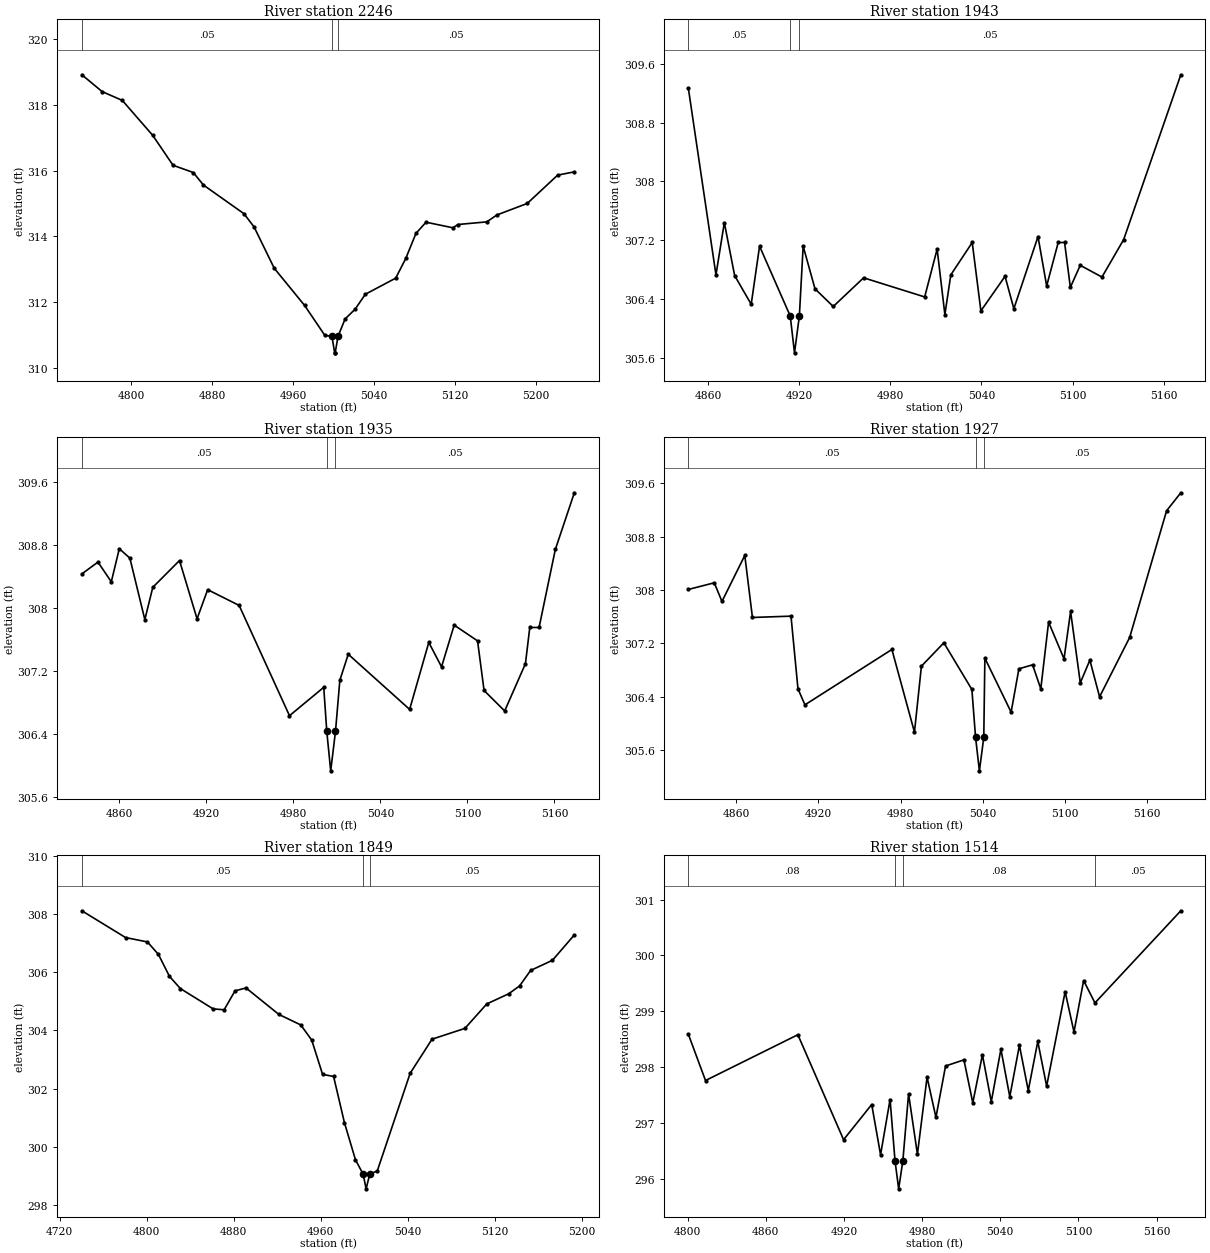
Type RM Length L Ch R = 1 ,2246    ,303,303,303
BEGIN DESCRIPTION:
UNT116 IN WICK 4.0
END DESCRIPTION:
XS GIS Cut Line= 2
      3572742.06     10225641.64      3573228.62     10225635.03
#Sta/Elev= 30
  4751.2  318.91  4771.2   318.4  4791.2  318.13  4821.2  317.07  4841.3  316.16
  4861.3  315.94  4871.3  315.56  4911.3  314.69  4921.3  314.29  4941.3  313.03
  4971.3   311.9  4991.3  310.99  4998.3  310.96    5001  310.46  5001.5  310.46
  5004.3  310.96  5011.3  311.49  5021.3  311.79  5031.3  312.24  5061.3  312.73
  5071.3  313.33  5081.3  314.09  5091.3  314.43  5117.8  314.26  5122.8  314.36
  5151.3  314.44  5161.3  314.65  5191.3     315  5221.3  315.86  5237.8  315.96
#Mann= 3 ,-1 , 0
  4751.2     .05       0  4998.3     .03       0  5004.3     .05       0
Bank Sta=4998.3,5004.3
XS Rating Curve= 0 ,0
Exp/Cntr=0.3,0.1

Type RM Length L Ch R = 1 ,1943    ,8,8,8
BEGIN DESCRIPTION:
Mapping XS 05d71e7f
END DESCRIPTION:
XS GIS Cut Line= 6
      3572944.27     10225887.48       3573023.6     10225922.99
       3573084.5     10225920.36      3573110.79      10225915.1
      3573174.32     10225879.17      3573222.92     10225820.06
#Sta/Elev= 30
    4847  309.27  4865.2  306.73  4870.7  307.44  4877.5  306.72  4888.4  306.33
  4893.9  307.12  4914.1  306.17  4916.9  305.67  4920.1  306.17  4922.6  307.12
  4930.4  306.54  4942.4   306.3  4962.4  306.69  5002.6  306.43  5010.8  307.08
  5015.9  306.19  5019.8  306.73  5033.9  307.17  5039.6  306.24  5055.5  306.71
  5061.3  306.27  5077.2  307.25  5082.9  306.58  5090.5  307.17  5094.7  307.17
  5098.5  306.56    5105  306.86  5119.3   306.7  5133.6  307.21  5171.2  309.45
#Mann= 3 ,-1 , 0
    4847     .05       0  4914.1     .04       0  4920.1     .05       0
Bank Sta=4914.1,4920.1
XS Rating Curve= 0 ,0
Exp/Cntr=0.3,0.1

Type RM Length L Ch R = 1 ,1935    ,8,8,8
BEGIN DESCRIPTION:
Mapping XS 3c162600
END DESCRIPTION:
XS GIS Cut Line= 6
      3572931.99     10225896.68      3572989.86     10225922.99
       3573029.3     10225933.94       3573108.6     10225924.74
      3573185.71      10225881.8       3573227.9     10225830.24
#Sta/Elev= 30
  4834.3  308.43  4845.4  308.58  4854.6  308.33  4860.1  308.75  4867.4  308.63
  4877.7  307.85  4883.2  308.26  4901.6   308.6  4913.7  307.86    4921  308.23
  4942.7  308.03  4977.4  306.63    5001  306.99  5003.1  306.43  5005.8  305.93
  5009.1  306.43  5012.1  307.08  5017.9  307.41  5060.2  306.71  5073.4  307.56
  5082.2  307.25  5090.9  307.78    5107  307.58  5111.5  306.95  5125.7  306.69
    5140  307.29    5143  307.75  5149.4  307.75  5160.6  308.74  5173.7  309.46
#Mann= 3 ,-1 , 0
  4834.3     .05       0  5003.1     .04       0  5009.1     .05       0
Bank Sta=5003.1,5009.1
XS Rating Curve= 0 ,0
Exp/Cntr=0.3,0.1

Type RM Length L Ch R = 1 ,1927    ,78,78,78
BEGIN DESCRIPTION:
Mapping XS 0a79ed16
END DESCRIPTION:
XS GIS Cut Line= 6
      3572922.87      10225906.8      3573006.51      10225939.2
      3573063.03     10225941.83      3573134.45     10225925.18
       3573182.2     10225898.45      3573236.07     10225832.77
#Sta/Elev= 30
  4824.8  308.01  4843.8  308.11  4849.4  307.83  4866.1  308.52  4871.7  307.59
  4899.9  307.61    4905  306.52  4910.1  306.28  4973.7  307.11  4990.2  305.87
  4995.3  306.86  5011.7  307.21  5032.2  306.51  5034.9  305.79  5037.7  305.29
  5040.9  305.79  5041.7  306.98  5060.9  306.17  5066.6  306.82  5076.6  306.88
  5082.6  306.52  5088.3  307.52  5099.6  306.97  5104.4  307.68  5111.5  306.61
  5118.5  306.95  5125.6   306.4  5147.6  307.29  5174.6  309.19    5185  309.46
#Mann= 3 ,-1 , 0
  4824.8     .05       0  5034.9     .04       0  5040.9     .05       0
Bank Sta=5034.9,5040.9
XS Rating Curve= 0 ,0
Exp/Cntr=0.3,0.1

Type RM Length L Ch R = 1 ,1849    ,335,335,335
BEGIN DESCRIPTION:
UNT116 IN WICK 3.0
END DESCRIPTION:
XS GIS Cut Line= 2
      3572842.13     10226041.64      3573292.06     10225991.65
#Sta/Elev= 30
  4740.4  308.11  4780.6  307.19  4800.7  307.04  4810.8  306.61  4820.9  305.86
  4830.9  305.44  4861.1  304.74  4871.2  304.71  4881.2  305.36  4891.3  305.46
  4921.5  304.55  4941.6  304.19  4951.7  303.67  4961.7  302.49  4971.8  302.42
  4981.8  300.83  4991.9  299.56    4999  299.06  5001.7  298.56    5005  299.06
    5012  299.18  5042.2  302.53  5062.3   303.7  5092.5  304.07  5112.6  304.91
  5132.8  305.26  5142.8  305.53  5152.9  306.06    5173  306.41  5193.1  307.28
#Mann= 3 ,-1 , 0
  4740.4     .05       0    4999     .03       0    5005     .05       0
Bank Sta=4999,5005
XS Rating Curve= 0 ,0
Exp/Cntr=0.3,0.1

Type RM Length L Ch R = 1 ,1514    ,41,41,41
BEGIN DESCRIPTION:
Mapping XS 2f620e1f
END DESCRIPTION:
XS GIS Cut Line= 2
      3573025.09     10226463.45      3573302.56      10226206.6
#Sta/Elev= 30
  4800.5  298.59  4813.7  297.76  4884.6  298.58  4919.7   296.7  4941.3  297.33
  4948.1  296.43  4955.4  297.42  4959.2  296.32    4962  295.82  4965.2  296.32
  4969.6  297.52  4976.4  296.44  4983.8  297.82  4990.6   297.1    4998  298.02
  5012.1  298.13  5018.9  297.36  5026.3  298.22  5033.1  297.38  5040.5  298.32
  5047.3  297.47  5054.7  298.39  5061.5  297.58  5068.8  298.46  5075.6  297.66
  5089.8  299.35  5096.6  298.63    5104  299.55  5112.7  299.15  5178.6   300.8
#Mann= 4 ,-1 , 0
  4800.5     .08       0  4959.2     .07       0  4965.2     .08       0
  5112.7     .05       0
Bank Sta=4959.2,4965.2
XS Rating Curve= 0 ,0
Exp/Cntr=0.3,0.1

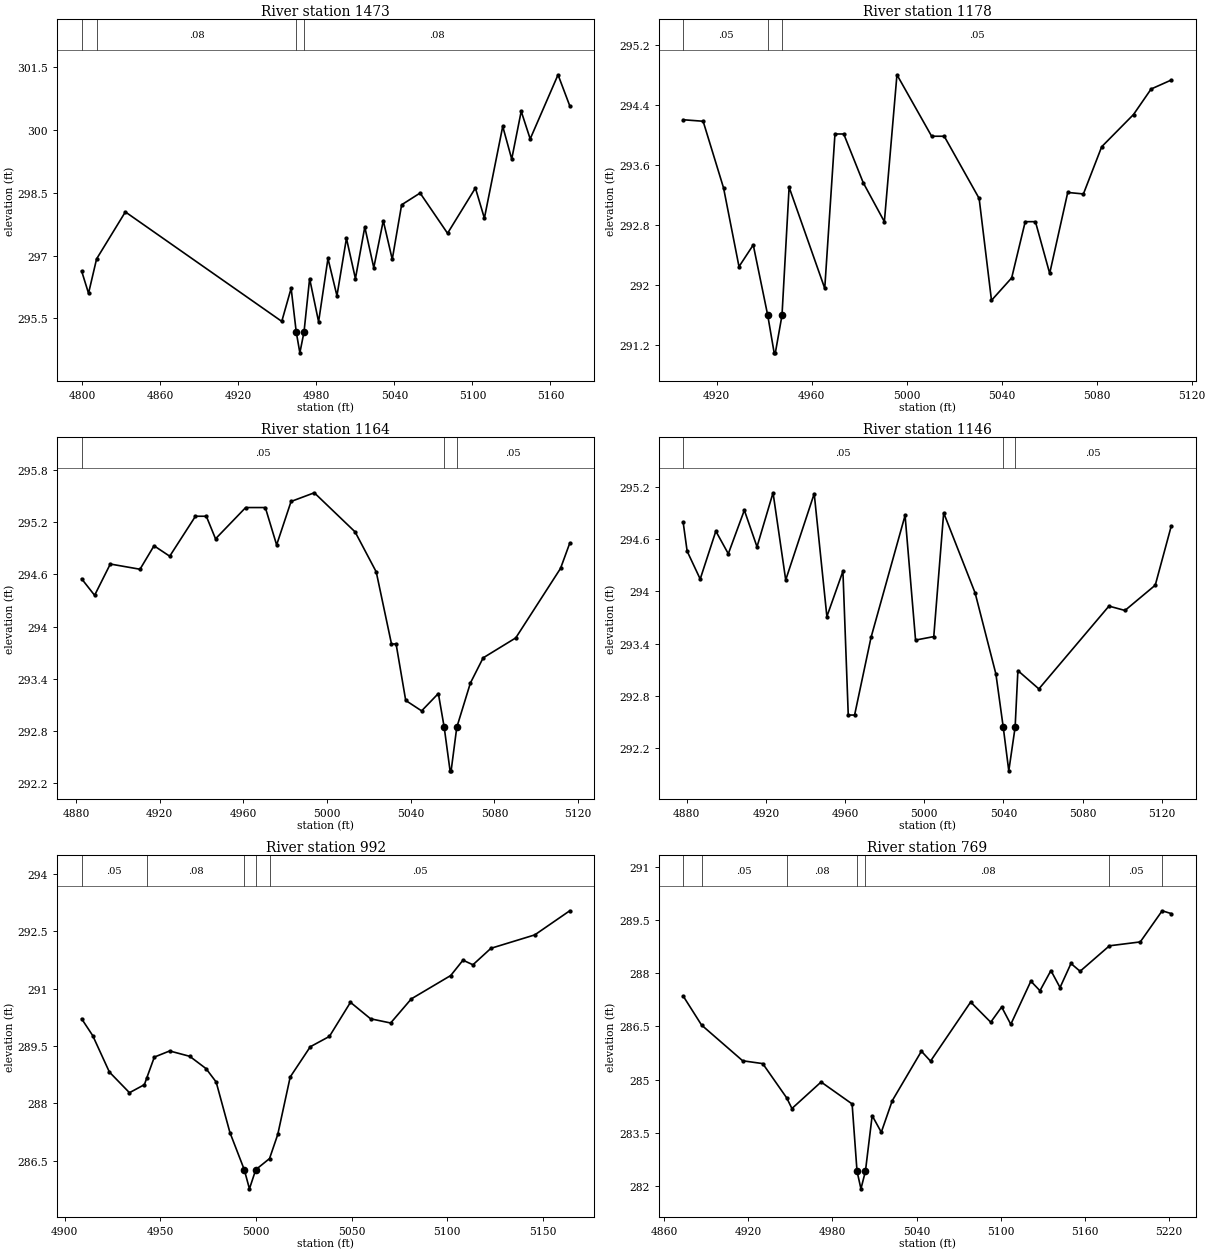
Type RM Length L Ch R = 1 ,1473    ,295,295,295
BEGIN DESCRIPTION:
Mapping XS 0d9de924
END DESCRIPTION:
XS GIS Cut Line= 2
      3573064.15     10226501.21      3573322.47     10226229.23
#Sta/Elev= 30
  4799.7  296.63    4805   296.1  4811.2  296.92  4833.3  298.04  4953.5  295.43
  4960.7  296.22  4964.6  295.18  4967.4  294.68  4970.6  295.18  4974.9  296.45
  4981.8  295.42    4989  296.93  4995.9  296.04  5003.2  297.41  5010.1  296.45
  5017.3  297.68  5024.2  296.71  5031.5  297.83  5038.4  296.91  5045.6  298.21
  5059.8  298.49  5080.9  297.53  5102.3  298.61  5109.2  297.89  5123.3  300.08
  5130.2   299.3  5137.5  300.44  5144.4  299.78  5165.8  301.31  5174.8  300.57
#Mann= 4 ,-1 , 0
  4799.7     .05       0  4811.2     .08       0  4964.6     .07       0
  4970.6     .08       0
Bank Sta=4964.6,4970.6
XS Rating Curve= 0 ,0
Exp/Cntr=0.3,0.1

Type RM Length L Ch R = 1 ,1178    ,14,14,14
BEGIN DESCRIPTION:
Mapping XS 393c72fc
END DESCRIPTION:
XS GIS Cut Line= 5
       3573227.9     10226563.41       3573284.3     10226600.73
       3573322.5     10226612.01      3573358.09      10226601.6
      3573404.12     10226561.64
#Sta/Elev= 30
  4905.9   294.2  4914.3  294.18  4922.9  293.29  4929.4  292.24  4935.4  292.53
  4941.5  291.59  4944.2  291.09  4944.7  291.09  4947.5  291.59  4950.5   293.3
  4965.5  291.95  4969.8  294.01  4973.5  294.01  4981.7  293.36  4990.6  292.84
  4995.9   294.8  5010.5  293.98  5015.8  293.98  5030.5  293.15  5035.7  291.79
  5044.2  292.09  5049.9  292.84  5054.2  292.84  5060.2  292.15  5067.8  293.23
  5074.4  293.21  5082.1  293.84  5095.5  294.27  5102.9  294.61  5111.4  294.73
#Mann= 3 ,-1 , 0
  4905.9     .05       0  4941.5     .04       0  4947.5     .05       0
Bank Sta=4941.5,4947.5
XS Rating Curve= 0 ,0
Exp/Cntr=0.3,0.1

Type RM Length L Ch R = 1 ,1164    ,18,18,18
BEGIN DESCRIPTION:
Mapping XS 71c94bb4
END DESCRIPTION:
XS GIS Cut Line= 5
      3573210.52     10226564.27      3573254.79      10226604.2
      3573298.19     10226622.43       3573341.6     10226618.09
      3573412.91     10226575.64
#Sta/Elev= 30
  4882.7  294.55  4888.9  294.36  4896.4  294.72  4910.6  294.66  4917.3  294.93
  4924.8  294.81  4937.1  295.27  4942.3  295.27  4946.7  295.01  4961.1  295.37
  4970.5  295.37  4975.9  294.94  4982.8  295.44  4993.9  295.54  5013.4  295.09
  5023.5  294.63  5030.8   293.8    5033   293.8  5037.6  293.15  5045.2  293.03
  5053.2  293.23    5056  292.84  5058.8  292.34  5059.3  292.34    5062  292.84
  5068.5  293.35  5074.6  293.64  5090.2  293.87  5111.6  294.67    5116  294.96
#Mann= 3 ,-1 , 0
  4882.7     .05       0    5056     .04       0    5062     .05       0
Bank Sta=5056,5062
XS Rating Curve= 0 ,0
Exp/Cntr=0.3,0.1

Type RM Length L Ch R = 1 ,1146    ,154,154,154
BEGIN DESCRIPTION:
UNT116 IN WICK 2.0
END DESCRIPTION:
XS GIS Cut Line= 5
      3573205.35     10226575.58      3573271.28     10226626.77
      3573307.47      10226639.4      3573355.49     10226625.03
      3573418.76     10226585.37
#Sta/Elev= 30
  4878.2  294.79  4880.2  294.46  4886.8  294.14  4894.7  294.69    4901  294.43
  4909.1  294.93  4915.5  294.51  4923.6  295.13    4930  294.13  4944.4  295.12
  4950.8  293.71  4958.9  294.23  4961.6  292.58  4964.8  292.58  4973.1  293.47
  4990.3  294.87  4995.6  293.44  5004.8  293.48  5009.8   294.9  5025.7  293.98
  5036.2  293.05  5039.9  292.44  5042.7  291.94  5045.9  292.44  5047.3  293.09
  5057.9  292.88  5093.3  293.83  5101.4  293.78  5116.7  294.07  5124.8  294.75
#Mann= 3 ,-1 , 0
  4878.2     .05       0  5039.9     .04       0  5045.9     .05       0
Bank Sta=5039.9,5045.9
XS Rating Curve= 0 ,0
Exp/Cntr=0.3,0.1

Type RM Length L Ch R = 1 ,992     ,223,223,223
BEGIN DESCRIPTION:
Mapping XS 62525c02
END DESCRIPTION:
XS GIS Cut Line= 2
      3573258.24     10226807.33      3573501.35     10226730.06
#Sta/Elev= 30
  4908.9  290.21  4914.7  289.77  4923.4  288.82  4933.9  288.28  4941.7  288.49
  4942.9  288.66  4946.9  289.21  4954.9  289.37  4965.4  289.23  4973.9  288.91
  4979.2  288.56  4986.4  287.24  4993.9  286.27  4996.6  285.77  4999.9  286.27
  5007.1  286.56  5011.4  287.19  5017.9  288.69  5028.4  289.48  5038.4  289.75
  5049.4  290.64  5059.9  290.21  5070.4   290.1  5081.2  290.73  5101.8  291.34
  5108.2  291.74  5113.4  291.62  5122.8  292.05  5145.7   292.4    5164  293.03
#Mann= 5 ,-1 , 0
  4908.9     .05       0  4942.9     .08       0  4993.9     .07       0
  4999.9     .08       0  5007.1     .05       0
Bank Sta=4993.9,4999.9
XS Rating Curve= 0 ,0
Exp/Cntr=0.3,0.1

Type RM Length L Ch R = 1 ,769     ,35,35,35
BEGIN DESCRIPTION:
Mapping XS 006e1e91
END DESCRIPTION:
XS GIS Cut Line= 2
      3573398.09     10227026.83      3573663.66      10226802.1
#Sta/Elev= 30
  4873.6  287.36  4886.7  286.54    4916  285.53  4930.3  285.45  4947.4  284.48
  4951.1  284.18  4971.9  284.93    4994  284.31  4997.5  282.41  5000.3  281.91
  5003.5  282.41  5008.3  283.98  5014.8  283.51  5022.6   284.4  5043.4   285.8
  5049.9  285.52  5078.5  287.19  5092.8  286.62  5100.6  287.05  5107.1  286.56
  5121.4  287.78  5127.9  287.51  5135.7  288.08  5142.2   287.6    5150  288.28
  5156.5  288.06  5177.4  288.78  5199.4  288.89    5215  289.77  5221.5  289.69
#Mann= 7 ,-1 , 0
  4873.6     .16       0  4886.7     .05       0  4947.4     .08       0
  4997.5     .07       0  5003.5     .08       0  5177.4     .05       0
    5215     .08       0
Bank Sta=4997.5,5003.5
XS Rating Curve= 0 ,0
Exp/Cntr=0.3,0.1

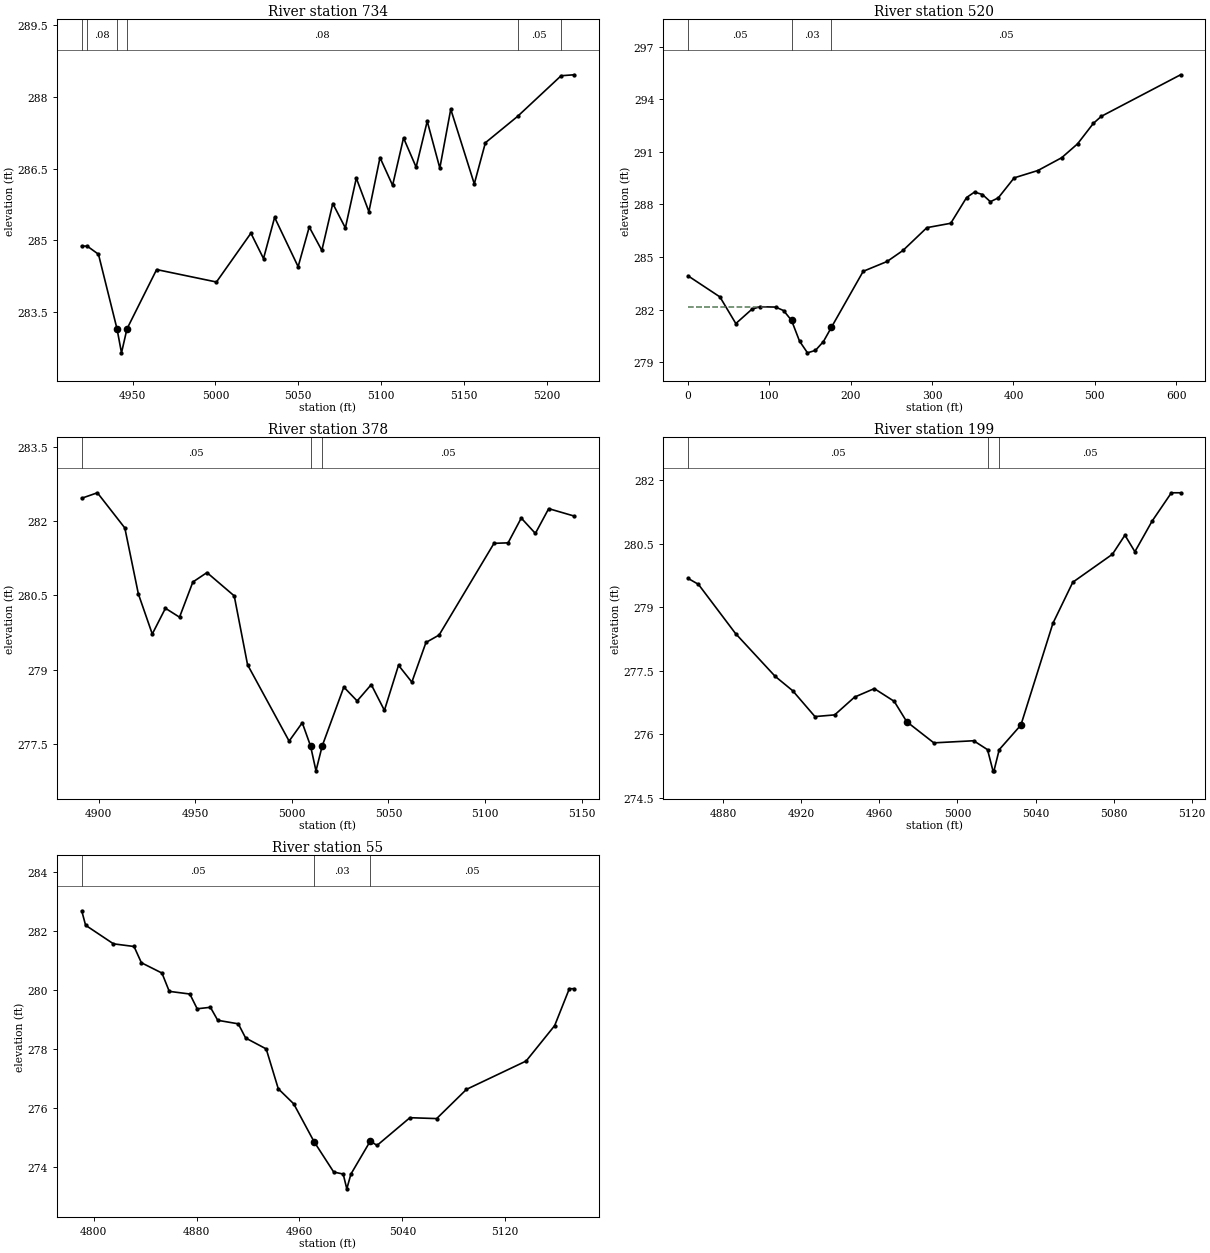
Type RM Length L Ch R = 1 ,734     ,214,214,214
BEGIN DESCRIPTION:
Mapping XS f07af0a5
END DESCRIPTION:
XS GIS Cut Line= 2
      3573458.79      10227022.6      3573682.77     10226827.26
#Sta/Elev= 30
  4919.3  284.88  4922.6  284.88  4929.4  284.71  4940.6  283.15  4943.3  282.65
  4946.6  283.15  4964.5  284.39  5000.6  284.13  5021.4  285.15    5029  284.62
  5035.7  285.48  5049.9  284.45  5056.6  285.28  5064.2  284.79  5070.8  285.77
  5078.4  285.26    5085   286.3  5092.6   285.6  5099.3  286.73  5106.9  286.15
  5113.5  287.14  5121.1  286.53  5127.8  287.49  5135.4  286.51    5142  287.74
  5156.2  286.18  5162.9  287.04  5182.3  287.59  5208.6  288.44  5216.5  288.46
#Mann= 6 ,-1 , 0
  4919.3     .05       0  4922.6     .08       0  4940.6     .07       0
  4946.6     .08       0  5182.3     .05       0  5208.6     .08       0
Bank Sta=4940.6,4946.6
XS Rating Curve= 0 ,0
Exp/Cntr=0.3,0.1

Type RM Length L Ch R = 1 ,520     ,142,142,142
XS GIS Cut Line= 3
      3573521.17     10227123.29     3573843.898    10227121.738
     3574107.111    10227217.514
#Sta/Elev= 30
       0  283.92   39.14  282.72   58.71   281.2   78.29  282.01   88.07  282.16
  107.64  282.14  117.43  281.94  127.21  281.38     137   280.2  146.79  279.53
  156.57  279.67  166.36  280.17  176.14  280.98  215.29  284.18  244.64  284.74
  264.21  285.37  293.57  286.67  322.93  286.92  342.41  288.39  352.16   288.7
   361.9  288.56  371.64  288.15  381.38  288.37  400.87  289.51   430.1  289.93
  459.32  290.66  478.81  291.45  498.29  292.62  508.04  293.02  605.46  295.39
#Mann= 3 , 0 , 0
       0     .05       0  127.21     .03       0  176.14     .05       0
#XS Ineff= 2 , 0
           97.32  282.17
Permanent Ineff=
       F       F
Bank Sta=127.21,176.14
XS Rating Curve= 0 ,0
Exp/Cntr=0.3,0.1

Type RM Length L Ch R = 1 ,378     ,179,179,179
BEGIN DESCRIPTION:
Mapping XS 05e3f213
END DESCRIPTION:
XS GIS Cut Line= 2
      3573610.72     10227161.51      3573796.44     10227335.95
#Sta/Elev= 30
  4891.3  282.46  4899.4  282.57  4913.6  281.86  4920.6  280.53  4927.8  279.72
  4934.6  280.24  4941.9  280.06  4948.8  280.77  4956.1  280.96  4970.2  280.49
  4977.1   279.1  4998.6  277.56  5005.4  277.93  5009.7  277.46  5012.5  276.96
  5015.7  277.46  5026.9  278.65  5033.8  278.37  5041.1   278.7  5047.9  278.18
  5055.2  279.09  5062.1  278.75  5069.4  279.55  5076.2   279.7  5104.6  281.55
  5111.9  281.56  5118.7  282.06    5126  281.75  5132.9  282.25  5146.1   282.1
#Mann= 3 ,-1 , 0
  4891.3     .05       0  5009.7     .03       0  5015.7     .05       0
Bank Sta=5009.7,5015.7
XS Rating Curve= 0 ,0
Exp/Cntr=0.3,0.1

Type RM Length L Ch R = 1 ,199     ,144,144,144
BEGIN DESCRIPTION:
Mapping XS 8c56ec5e
END DESCRIPTION:
XS GIS Cut Line= 2
       3573568.2     10227366.36      3573816.43     10227411.49
#Sta/Elev= 26
    4862  279.68  4867.3  279.54  4886.3  278.38  4906.6  277.37  4915.6  277.03
    4927  276.42  4937.1  276.46  4947.3  276.88  4957.4  277.08  4967.6  276.78
    4974   276.3  4987.9   275.8  5008.3  275.85  5015.4  275.64  5018.2  275.14
  5018.7  275.14  5021.4  275.64  5032.5  276.22  5048.9  278.62  5059.1  279.59
  5079.4  280.25  5085.8   280.7  5090.9  280.31  5099.7  281.03  5109.6   281.7
  5114.3   281.7
#Mann= 3 ,-1 , 0
    4862     .05       0  5015.4     .04       0  5021.4     .05       0
Bank Sta=4974,5032.5
XS Rating Curve= 0 ,0
Exp/Cntr=0.3,0.1

Type RM Length L Ch R = 1 ,55      ,0,0,0
BEGIN DESCRIPTION:
UNT116 IN WICK 1.0
END DESCRIPTION:
XS GIS Cut Line= 4
      3573516.07     10227373.29      3573590.73     10227506.98
      3573691.42     10227534.75      3573806.02     10227483.53
#Sta/Elev= 30
  4790.6  282.67  4793.6  282.18  4815.3  281.55  4831.3  281.46    4837  280.91
    4853  280.56  4858.7  279.94  4874.7  279.85  4880.4  279.35  4890.7   279.4
  4896.4  278.96  4912.4  278.84  4918.1  278.36  4934.1  277.99  4943.5  276.64
  4955.5  276.13 4971.31  274.85  4986.6  273.82    4994  273.75  4996.8  273.25
    5000  273.75  5015.1  274.87  5020.3  274.72  5045.9  275.66  5066.7  275.63
  5089.9  276.62  5136.3  277.58  5158.5  278.78  5169.9  280.03  5173.7  280.03
#Mann= 3 , 0 , 0
  4790.6     .05       0 4971.31     .03       0  5015.1     .05       0
Bank Sta=4971.31,5015.1
XS Rating Curve= 0 ,0
Exp/Cntr=0.3,0.1

Chan Stop Cuts=-1
Use User Specified Reach Order=0
Composite Channel Slope=5