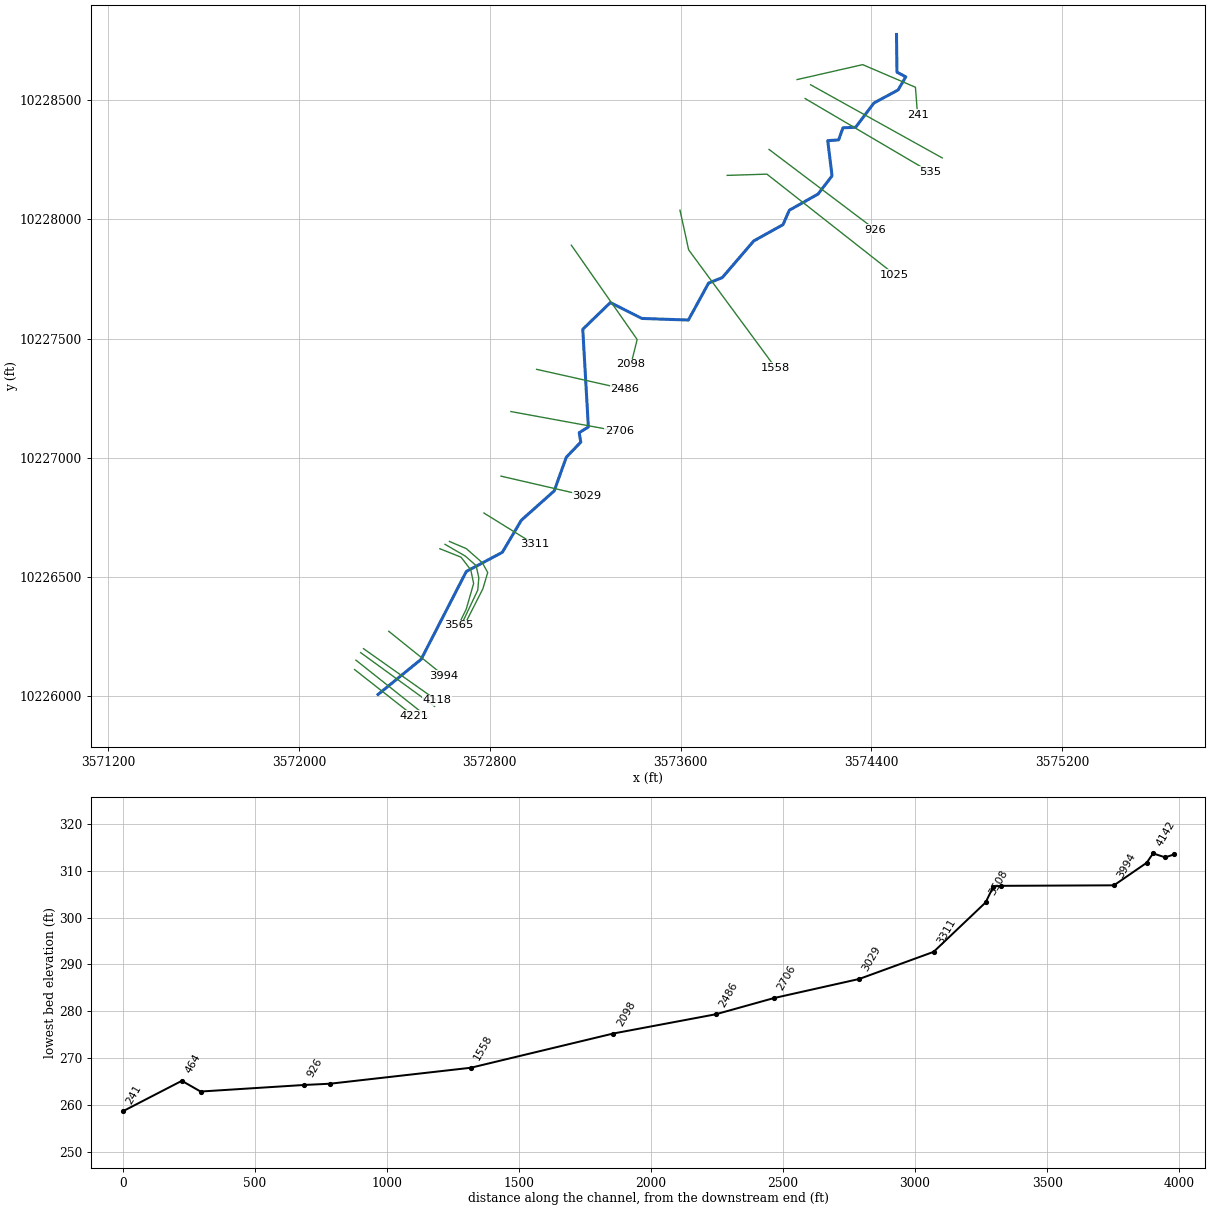
--- BRUSHYCREEKTRIB1.prj (project) ---

Proj Title=BRUSHY CREEK TRIB 13
Current Plan=p01
Default Exp/Contr=0.3,0.1
English Units
Geom File=g01
Flow File=f01
Plan File=p01
Y Axis Title=Elevation
X Axis Title(PF)=Main Channel Distance
X Axis Title(XS)=Station
BEGIN DESCRIPTION:
UNT05299 IN WICK
END DESCRIPTION:
DSS File=dss
DSS Export Rating Curves= 0
DSS Export Rating Curve Sorted= 0
DSS Export Volume Flow Curves= 0
DXF Filename=UNT05299 IN WICK.
DXF OffsetX= 0
DXF OffsetY= 0
DXF ScaleX= 1
DXF ScaleY= 10

--- BRUSHYCREEKTRIB1.p01 (plan) ---

Plan Title=Multiple Run
Program Version=4.10
Short Identifier=Multiple Run
Geom File=g01
Flow File=f01
Subcritical Flow
K Sum by GR= 0
Std Step Tol= 0.01
Critical Tol= 0.01
Num of Std Step Trials= 20
Max Error Tol= 0.3
Flow Tol Ratio= 0.001
Split Flow NTrial= 30
Split Flow Tol= 0.02
Split Flow Ratio= 0.02
Log Output Level= 0
Friction Slope Method= 1
Unsteady Friction Slope Method= 2
Unsteady Bridges Friction Slope Method= 1
Parabolic Critical Depth
Global Vel Dist= 1 , 1 , 1
Global Log Level= 0
CheckData=True
Encroach Param=-1 ,0,0, 0
BEGIN DESCRIPTION:
Multiple Run
END DESCRIPTION:
Computation Interval=1HOUR
Output Interval=1HOUR
Run HTab= 0
Run UNet= 0
Run PostProcess= 0
Run WQNet= 0
UNET Theta= 1
UNET Theta Warmup= 1
UNET ZTol= 0.02
UNET ZSATol= 0.05
UNET MxIter= 20
UNET MaxInSteps= 0
UNET DtIC= 0
UNET DtMin= 0
UNET MaxCRTS= 20
UNET WFStab= 2
UNET SFStab= 1
UNET WFX= 1
UNET SFX= 1
UNET DSS MLevel= 4
UNET DZMax Abort= 100
UNET Convert EG Bridges= 0
UNET Use Existing IB Tables=-1
UNET Froude Reduction=False
UNET Froude Limit= 1
UNET Froude Power= 10
UNET Time Slicing=0,0, 5
UNET Junction Losses=0
Instantaneous Interval=1HOUR
DSS File=dss
Write IC File= 0
Write IC File at Sim End=0
Echo Input=False
Echo Parameters=False
Echo Output=False
Write Detailed= 0
WQ AD Non Conservative
WQ ULTIMATE=-1
WQ Max Comp Step=1HOUR
WQ Output Interval=15MIN
WQ Output Selected Increments= 0
WQ Output face flow=0
WQ Output face velocity=0
WQ Output face area=0
WQ Output face dispersion=0
WQ Output cell volume=0
WQ Output cell surface area=0
WQ Output cell continuity=0
WQ Output cumulative cell continuity=0
WQ Output face conc=0
WQ Output face dconc_dx=0
WQ Output face courant=0
WQ Output face peclet=0
WQ Output face adv mass=0
WQ Output face disp mass=0
WQ Output cell mass=0
WQ Output cell source sink temp=0
WQ Output cell source sink nsm=0
WQ Output MaxMinRange=-1
WQ Daily Max Min Mean=-1
WQ Daily Range=0
WQ Daily Time=0
WQ Create Restart=0
WQ Fixed Restart=0
WQ System Summary=0
WQ Use Fixed Temperature=0
Sorting and Armoring Iterations= 10
XS Update Threshold= 0.02
Hydraulics Update Threshold= 0.02
Energy Slope Method= 1
Volume Change Method= 0
XS Weighting Method= 0
Number of US Weighted Cross Sections= 1
Number of DS Weighted Cross Sections= 1
Upstream XS Weight=0.25
Main XS Weight=0.5
Downstream XS Weight=0.25
Number of DS XS's Weighted with US Boundary= 1
Upstream Boundary Weight= 1
Weight of XSs Associated with US Boundary= 0
Number of US XS's Weighted with DS Boundary= 1
Downstream Boundary Weight= 0.5
Weight of XSs Associated with DS Boundary= 0.5
Sediment Output Level= 4
Mass or Volume Output= 0
Output Increment Type= 1
Profile and TS Output Increment= 10
XS Output Flag= 0
XS Output Increment= 10
Disregard all LS=0
Disregard all Conn=0
Disregard all Breaches=0
Disregard all Pumps=0

--- BRUSHYCREEKTRIB1.f01 (steady flow) ---

Flow Title=Multiple
Program Version=4.10
Number of Profiles= 7
Profile Names=10-year,25-year,50-year,1pct_min,100-year,1pct_plu,500-year
River Rch & RM=UNT05299 IN WICK,Reach-1         ,4221
      55      62      68      54      73      99      86
River Rch & RM=UNT05299 IN WICK,Reach-1         ,2098
     168     210     242     206     279     377     368
River Rch & RM=UNT05299 IN WICK,Reach-1         ,1558
     260     335     393     341     461     623     631
River Rch & RM=BRUSHYCRTR13,Reach-1         ,4221
      55      62      68      54      73      99      86
River Rch & RM=BRUSHYCRTR13,Reach-1         ,2098
     168     210     242     206     279     377     368
River Rch & RM=BRUSHYCRTR13,Reach-1         ,1558
     260     335     393     341     461     623     631
Boundary for River Rch & Prof#=BRUSHYCRTR13,Reach-1         , 1
Up Type= 0
Dn Type= 3
Dn Slope=0.005
Boundary for River Rch & Prof#=BRUSHYCRTR13,Reach-1         , 2
Up Type= 0
Dn Type= 3
Dn Slope=0.005
Boundary for River Rch & Prof#=BRUSHYCRTR13,Reach-1         , 3
Up Type= 0
Dn Type= 3
Dn Slope=0.005
Boundary for River Rch & Prof#=BRUSHYCRTR13,Reach-1         , 4
Up Type= 0
Dn Type= 3
Dn Slope=0.005
Boundary for River Rch & Prof#=BRUSHYCRTR13,Reach-1         , 5
Up Type= 0
Dn Type= 3
Dn Slope=0.005
Boundary for River Rch & Prof#=BRUSHYCRTR13,Reach-1         , 6
Up Type= 0
Dn Type= 3
Dn Slope=0.005
Boundary for River Rch & Prof#=BRUSHYCRTR13,Reach-1         , 7
Up Type= 0
Dn Type= 3
Dn Slope=0.005
DSS Import GetInterval= 0
DSS Import GetPeak= 0
DSS Import FillOption= 0

--- BRUSHYCREEKTRIB1.g01 (geometry) ---

Geom Title=Existing Conditions
Program Version=4.10

River Reach=BRUSHYCRTR13    ,Reach-1
Reach XY= 30
      3572331.68     10226007.68      3572512.41     10226155.15
      3572701.81     10226523.48      3572852.79     10226603.67
      3572932.43     10226738.22      3573070.24     10226861.05
      3573121.01     10227002.34      3573181.78     10227065.88
      3573175.18     10227105.29      3573213.55     10227129.25
      3573190.11     10227538.97      3573305.81     10227650.88
      3573438.04     10227584.34      3573632.91     10227577.62
      3573717.72     10227732.72        3573775.     10227755.52
      3573906.75     10227909.15      3574029.75     10227977.64
      3574056.14     10228038.05      3574176.97     10228106.11
      3574235.31      10228182.5      3574217.25     10228329.72
      3574263.09     10228333.19      3574281.05     10228383.76
      3574334.22     10228385.93      3574411.26     10228487.92
      3574512.17     10228542.18      3574544.47     10228597.47
      3574507.66     10228616.92      3574505.58     10228775.25

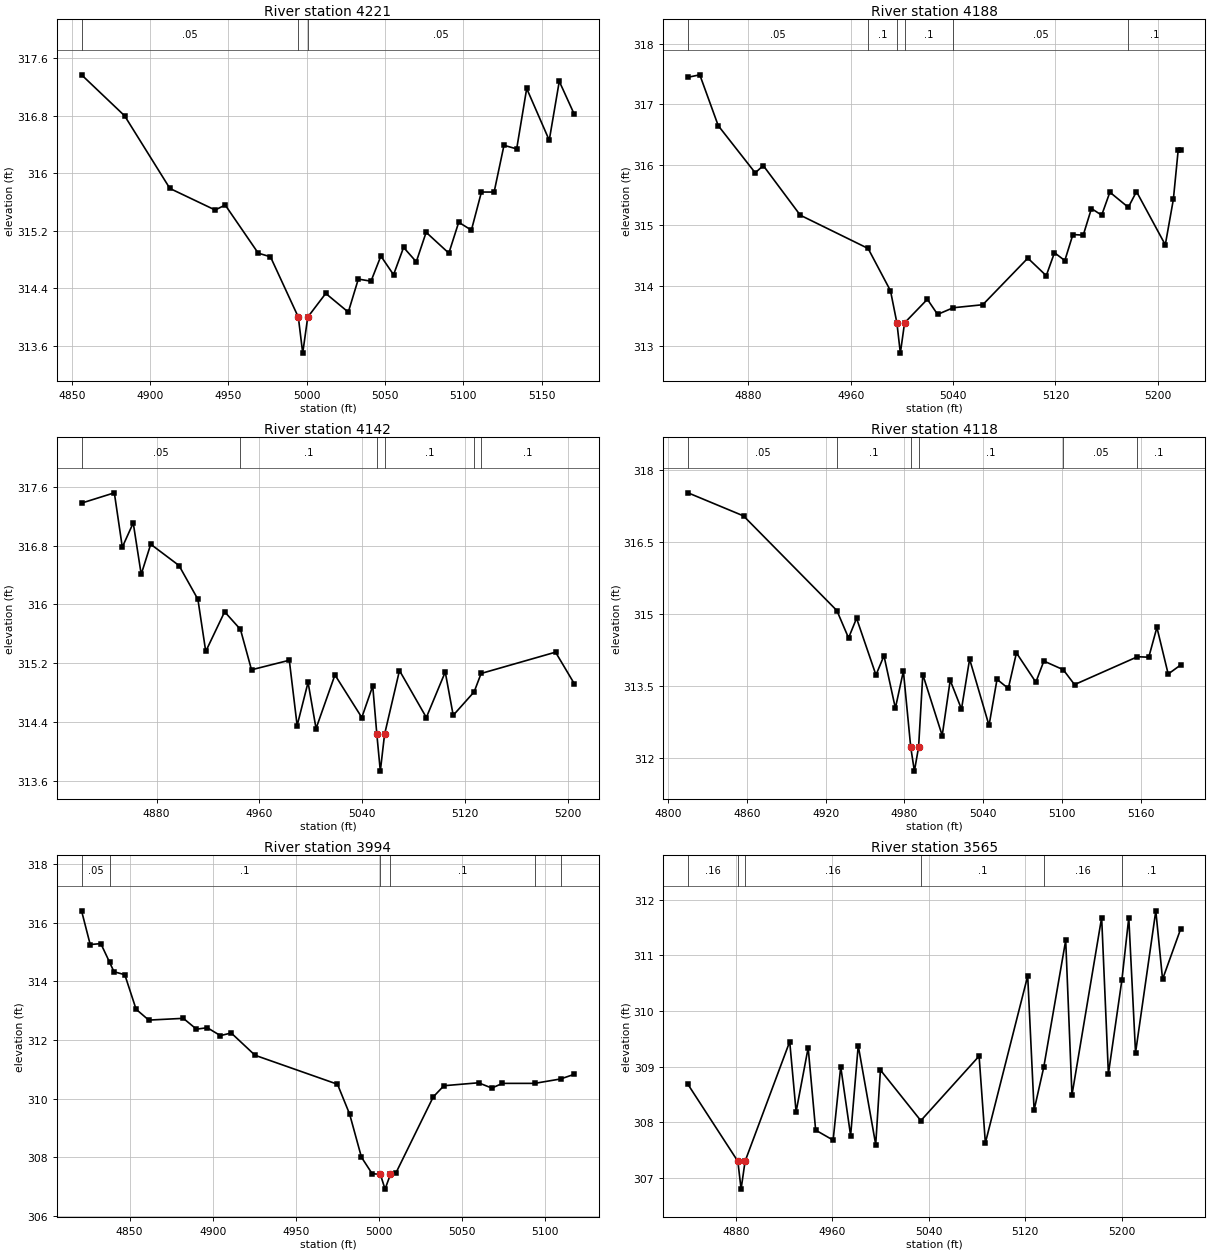
Type RM Length L Ch R = 1 ,4221    ,33,33,33
BEGIN DESCRIPTION:
UNT05299 IN WICK 8.0
END DESCRIPTION:
XS GIS Cut Line= 2
      3572233.39     10226112.04      3572480.74     10225917.63
#Sta/Elev= 30
  4856.2  317.37  4883.7   316.8  4912.6  315.79  4941.5  315.49  4947.9  315.56
    4969  314.89  4976.8  314.84  4994.6     314  4997.4   313.5  5000.6     314
  5012.1  314.33  5026.5  314.07  5032.9  314.53    5041   314.5  5047.3  314.85
  5055.4  314.59  5061.8  314.97  5069.9  314.77  5076.2  315.18  5090.7  314.89
    5097  315.32  5105.1  315.21  5111.5  315.74  5119.6  315.74  5125.9  316.39
    5134  316.34  5140.4  317.18  5154.8  316.46  5161.2  317.28  5170.8  316.82
#Mann= 3 ,-1 , 0
  4856.2     .05       0  4994.6     .04       0  5000.6     .05       0
Bank Sta=4994.6,5000.6
XS Rating Curve= 0 ,0
Exp/Cntr=0.3,0.1

Type RM Length L Ch R = 1 ,4188    ,46,46,46
BEGIN DESCRIPTION:
Mapping XS fd67eb0a
END DESCRIPTION:
XS GIS Cut Line= 2
      3572238.88     10226151.54      3572540.31     10225912.03
#Sta/Elev= 30
  4832.9  317.45  4842.1  317.49  4856.5  316.65  4885.4  315.87  4891.7  315.99
  4920.6  315.17  4973.6  314.62  4991.1  313.92  4996.1  313.39  4998.8  312.89
  5002.1  313.39  5019.9  313.78  5027.9  313.53  5040.1  313.64  5063.2  313.69
  5098.4  314.46  5112.8  314.17  5119.2  314.55  5127.3  314.42  5133.6  314.85
  5141.7  314.84  5148.1  315.28  5156.1  315.17  5162.5  315.55  5176.9   315.3
  5183.3  315.56  5205.8  314.68  5212.1  315.43  5215.9  316.25  5217.9  316.25
#Mann= 6 ,-1 , 0
  4832.9     .05       0  4973.6      .1       0  4996.1     .07       0
  5002.1      .1       0  5040.1     .05       0  5176.9      .1       0
Bank Sta=4996.1,5002.1
XS Rating Curve= 0 ,0
Exp/Cntr=0.3,0.1

Type RM Length L Ch R = 1 ,4142    ,24,24,24
BEGIN DESCRIPTION:
Mapping XS 7e04bef3
END DESCRIPTION:
XS GIS Cut Line= 2
      3572258.58     10226183.21       3572568.6     10225957.81
#Sta/Elev= 30
  4821.6  317.38  4847.1  317.52  4853.3  316.78  4861.8  317.11    4868  316.41
  4875.4  316.82  4897.4  316.53  4912.1  316.07  4918.2  315.36  4932.9   315.9
  4945.2  315.66  4953.8  315.11  4983.2  315.24  4989.3  314.35  4997.8  314.94
    5004  314.31  5018.7  315.04  5039.6  314.46  5048.1  314.89  5051.3  314.23
    5054  313.73  5057.3  314.23  5068.9   315.1  5089.8  314.46  5104.5  315.08
  5110.7  314.49    5127  314.81  5132.4  315.06  5190.3  315.35  5204.9  314.92
#Mann= 6 ,-1 , 0
  4821.6     .05       0  4945.2      .1       0  5051.3     .07       0
  5057.3      .1       0    5127     .05       0  5132.4      .1       0
Bank Sta=5051.3,5057.3
XS Rating Curve= 0 ,0
Exp/Cntr=0.3,0.1

Type RM Length L Ch R = 1 ,4118    ,124,124,124
BEGIN DESCRIPTION:
Mapping XS 2308b186
END DESCRIPTION:
XS GIS Cut Line= 2
       3572270.7     10226199.72      3572577.59       10225983.
#Sta/Elev= 30
    4815  317.52  4857.3  317.04  4928.5  315.07  4937.4   314.5  4943.5  314.91
  4958.3  313.73  4964.4  314.13  4973.1  313.04  4979.2  313.81  4984.8  312.23
  4987.6  311.73  4990.8  312.23    4994  313.74  5008.8  312.47  5014.9  313.62
  5023.5  313.02  5029.7  314.06  5044.5  312.68  5050.6  313.64  5059.2  313.45
  5065.4  314.19  5080.2  313.58  5086.3  314.02  5101.1  313.84  5109.7  313.53
  5157.7  314.11  5166.3   314.1  5172.5  314.72  5181.1  313.75  5190.7  313.94
#Mann= 6 ,-1 , 0
    4815     .05       0  4928.5      .1       0  4984.8     .07       0
  4990.8      .1       0  5101.1     .05       0  5157.7      .1       0
Bank Sta=4984.8,4990.8
XS Rating Curve= 0 ,0
Exp/Cntr=0.3,0.1

Type RM Length L Ch R = 1 ,3994    ,429,429,429
BEGIN DESCRIPTION:
Mapping XS 890dd4ee
END DESCRIPTION:
XS GIS Cut Line= 2
      3572376.57     10226272.67      3572607.35     10226086.84
#Sta/Elev= 30
  4821.1  316.41  4826.3  315.26  4832.7  315.29    4838  314.65  4840.6  314.33
  4847.1  314.23  4853.9  313.05  4861.5  312.68  4882.3  312.74  4890.2  312.37
  4896.7  312.42  4904.6  312.15  4911.1  312.24  4925.4  311.48    4975  310.49
  4982.3  309.47  4989.4     308  4995.8  307.44  5000.8  307.41  5003.6  306.91
  5006.8  307.41  5010.2  307.47  5032.6  310.06    5039  310.44  5059.8  310.54
  5067.8  310.36  5074.2  310.52  5093.5  310.52  5109.1  310.67  5117.4  310.83
#Mann= 6 ,-1 , 0
  4821.1     .05       0    4838      .1       0  5000.8     .07       0
  5006.8      .1       0  5093.5     .05       0  5109.1      .1       0
Bank Sta=5000.8,5006.8
XS Rating Curve= 0 ,0
Exp/Cntr=0.3,0.1

Type RM Length L Ch R = 1 ,3565    ,28,28,28
BEGIN DESCRIPTION:
Mapping XS 2e82bdd0
END DESCRIPTION:
XS GIS Cut Line= 6
      3572590.98     10226618.65      3572679.55     10226583.41
      3572720.35     10226530.46       3572732.5     10226473.16
      3572701.25     10226364.66      3572668.11     10226297.71
#Sta/Elev= 30
  4840.4  308.68  4881.7   307.3  4884.4   306.8  4887.7   307.3  4924.7  309.45
    4930  308.19    4940  309.34  4946.2  307.86  4960.7  307.68    4967     309
  4975.2  307.76  4981.5  309.38    4996   307.6  4999.9  308.94  5033.4  308.03
  5081.7  309.19  5086.9  307.63    5122  310.63  5127.3  308.22  5135.3  308.99
  5153.5  311.27  5158.7  308.49  5183.3  311.68  5188.9  308.87  5200.1  310.56
  5205.8  311.68  5211.4  309.25  5228.2   311.8  5233.8  310.57  5248.9  311.48
#Mann= 6 ,-1 , 0
  4840.4     .16       0  4881.7     .07       0  4887.7     .16       0
  5033.4      .1       0  5135.3     .16       0  5200.1      .1       0
Bank Sta=4881.7,4887.7
XS Rating Curve= 0 ,0
Exp/Cntr=0.3,0.1

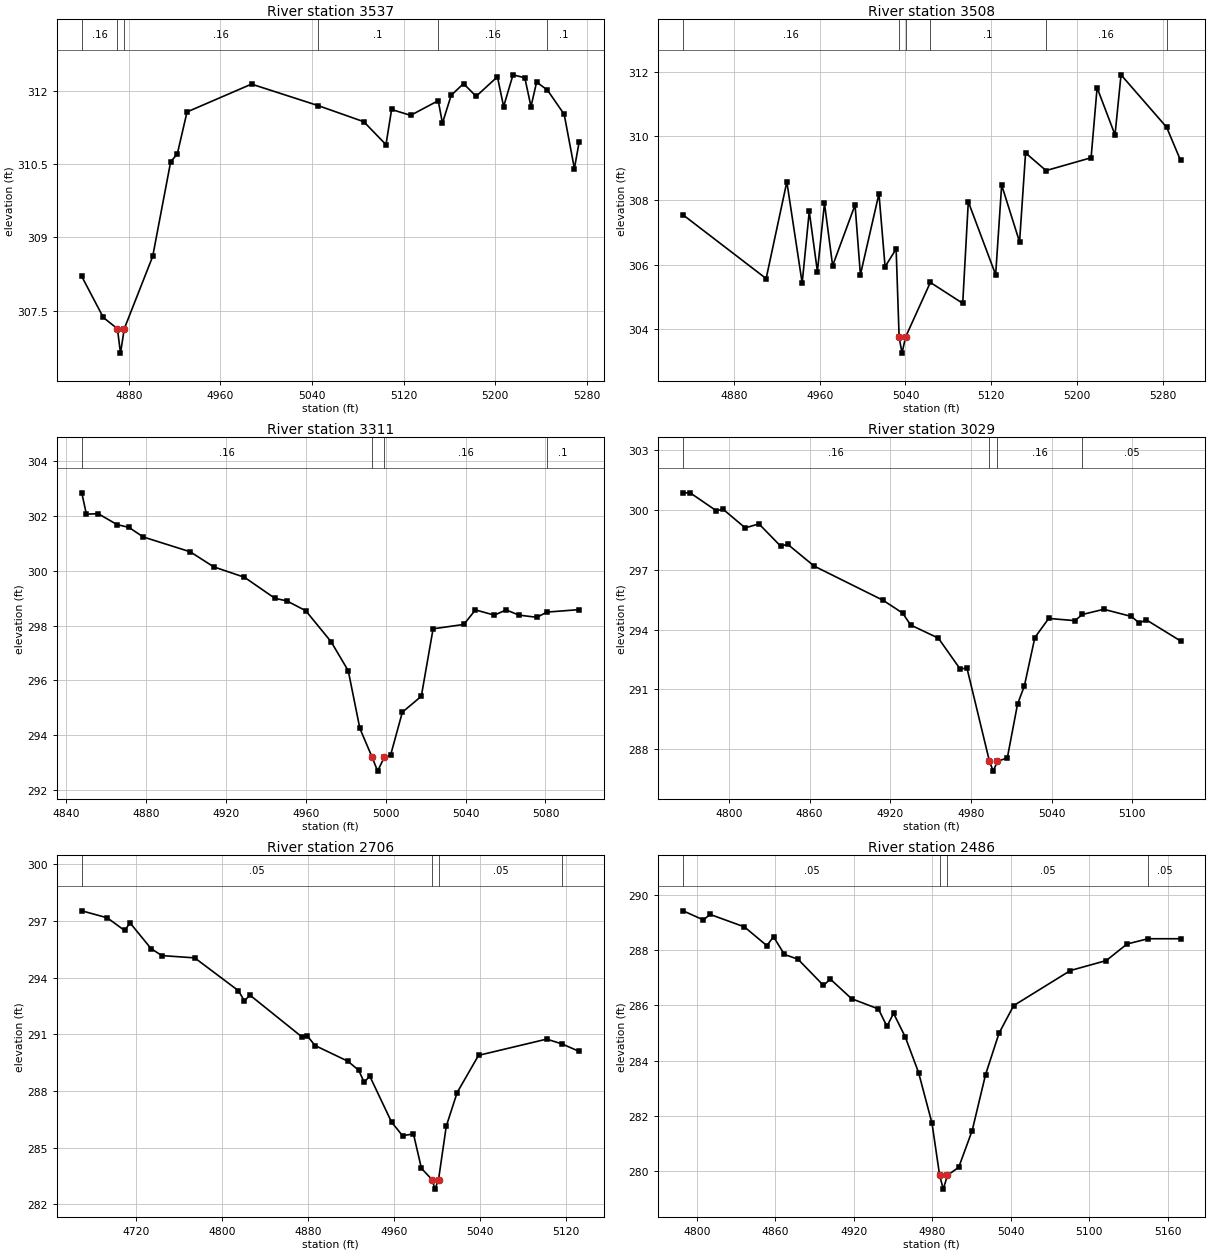
Type RM Length L Ch R = 1 ,3537    ,29,29,29
BEGIN DESCRIPTION:
Mapping XS 86f89649
END DESCRIPTION:
XS GIS Cut Line= 6
      3572612.61     10226637.12      3572697.78     10226587.75
      3572742.92     10226547.82       3572754.2      10226496.6
      3572749.86     10226445.39      3572676.54     10226290.41
#Sta/Elev= 30
    4839   308.2  4857.8  307.36  4870.1  307.13  4872.8  306.63  4876.1  307.13
  4900.9  308.61  4916.6  310.55  4922.4  310.71  4930.9  311.57  4987.2  312.14
  5045.3   311.7  5085.2  311.37  5104.6   310.9  5109.5  311.62  5126.1   311.5
  5150.2   311.8  5153.9  311.34  5161.5  311.91  5172.3  312.15  5183.3  311.89
  5201.9  312.29  5207.3  311.68  5215.5  312.33  5225.8  312.27  5231.2  311.68
  5236.1  312.18  5245.5  312.02  5260.2  311.52  5269.1  310.41  5273.3  310.96
#Mann= 6 ,-1 , 0
    4839     .16       0  4870.1     .07       0  4876.1     .16       0
  5045.3      .1       0  5150.2     .16       0  5245.5      .1       0
Bank Sta=4870.1,4876.1
XS Rating Curve= 0 ,0
Exp/Cntr=0.3,0.1

Type RM Length L Ch R = 1 ,3508    ,197,197,197
BEGIN DESCRIPTION:
Mapping XS bc0e6090
END DESCRIPTION:
XS GIS Cut Line= 6
      3572630.93     10226649.38      3572702.12       10226619.
      3572768.96     10226559.97      3572791.53     10226519.17
      3572771.22     10226450.77      3572690.01     10226290.97
#Sta/Elev= 30
  4832.7  307.55  4910.1  305.57  4929.4  308.58  4943.7  305.43  4950.3  307.66
  4957.9  305.79  4964.5  307.91  4972.1  305.97    4993  307.86    4998  305.69
  5015.3  308.21    5021  305.94  5031.3  306.49  5034.1  303.75  5036.8  303.25
  5040.1  303.75  5063.2  305.45  5093.4   304.8  5098.6  307.96  5124.1  305.69
  5129.7  308.48  5146.4  306.71    5152  309.48  5171.1  308.93  5213.1  309.33
  5218.7  311.51  5235.4  310.04    5241  311.91  5283.5  310.28  5296.5  309.25
#Mann= 6 ,-1 , 0
  4832.7     .16       0  5034.1     .07       0  5040.1     .16       0
  5063.2      .1       0  5171.1     .16       0  5283.5      .1       0
Bank Sta=5034.1,5040.1
XS Rating Curve= 0 ,0
Exp/Cntr=0.3,0.1

Type RM Length L Ch R = 1 ,3311    ,282,282,282
BEGIN DESCRIPTION:
UNT05299 IN WICK 7.0
END DESCRIPTION:
XS GIS Cut Line= 2
      3572775.89     10226768.31      3572987.74     10226637.09
#Sta/Elev= 30
  4847.7  302.84    4850  302.06  4855.9  302.08  4865.4  301.68  4871.3  301.58
  4878.5  301.23    4902  300.69  4913.8  300.14  4929.2  299.76  4944.5  298.99
  4950.4   298.9  4959.9  298.54  4972.6  297.41  4981.2  296.35    4987  294.25
  4993.2  293.19  4995.9  292.69  4999.2  293.19  5002.4  293.27  5008.3  294.84
  5017.8  295.42  5023.7  297.88  5039.1  298.04  5044.9  298.57  5054.4  298.38
  5060.3  298.57  5066.7  298.38  5075.7   298.3  5080.7  298.49  5096.9  298.58
#Mann= 4 ,-1 , 0
  4847.7     .16       0  4993.2     .07       0  4999.2     .16       0
  5080.7      .1       0
Bank Sta=4993.2,4999.2
XS Rating Curve= 0 ,0
Exp/Cntr=0.3,0.1

Type RM Length L Ch R = 1 ,3029    ,323,323,323
BEGIN DESCRIPTION:
UNT05299 IN WICK 6.0
END DESCRIPTION:
XS GIS Cut Line= 2
      3572847.11     10226923.14      3573207.73     10226839.92
#Sta/Elev= 30
  4765.9  300.87  4771.1  300.87  4790.6  299.97  4795.7  300.04  4812.1  299.11
  4822.3  299.31  4838.5  298.19  4843.6  298.29  4863.4  297.19  4914.7  295.47
  4929.2  294.83  4935.2  294.23  4955.8  293.57  4971.9  292.03  4977.1  292.06
  4993.8  287.39  4996.6  286.89  4999.8  287.39  5007.1  287.55  5014.7  290.25
  5019.8  291.17  5027.6   293.6  5037.9  294.56  5057.4  294.45    5063  294.76
  5078.9  295.02  5099.4  294.66  5105.3  294.33  5110.5  294.49    5136  293.43
#Mann= 4 ,-1 , 0
  4765.9     .16       0  4993.8     .07       0  4999.8     .16       0
    5063     .05       0
Bank Sta=4993.8,4999.8
XS Rating Curve= 0 ,0
Exp/Cntr=0.3,0.1

Type RM Length L Ch R = 1 ,2706    ,220,220,220
BEGIN DESCRIPTION:
UNT05299 IN WICK 5.0
END DESCRIPTION:
XS GIS Cut Line= 2
      3572888.79     10227193.97      3573343.72     10227110.63
#Sta/Elev= 30
  4669.8  297.54  4693.5  297.17  4709.6   296.5  4714.7   296.9  4734.2  295.54
  4744.3  295.17  4774.8  295.05  4815.5  293.31    4821  292.77  4826.1  293.08
  4874.2  290.88  4879.3  290.93  4886.7  290.41  4917.2  289.58  4927.3   289.1
  4932.4  288.46  4937.5   288.8  4957.8  286.36    4968  285.64  4978.2  285.73
  4985.6  283.91  4995.5  283.31  4998.2  282.81  5001.5  283.31  5008.7  286.14
  5018.8  287.92  5038.7  289.89  5102.1  290.75  5116.5  290.49  5132.3   290.1
#Mann= 4 ,-1 , 0
  4669.8     .05       0  4995.5     .03       0  5001.5     .05       0
  5116.5     .05       0
Bank Sta=4995.5,5001.5
XS Rating Curve= 0 ,0
Exp/Cntr=0.3,0.1

Type RM Length L Ch R = 1 ,2486    ,388,388,388
BEGIN DESCRIPTION:
Mapping XS d380ff26
END DESCRIPTION:
XS GIS Cut Line= 2
      3572996.47     10227371.05      3573367.55     10227287.82
#Sta/Elev= 30
  4789.6  289.42  4805.1  289.09  4810.2  289.29  4836.4  288.84  4853.6  288.16
  4858.7  288.48  4867.1  287.84  4877.4  287.67  4896.9  286.72  4902.1  286.95
  4918.4  286.24  4938.9  285.87  4945.4  285.24  4950.5  285.71  4959.4  284.86
  4969.6  283.57  4979.9  281.73  4985.7  279.85  4988.5  279.35  4991.7  279.85
  5000.3  280.14  5010.6  281.47  5020.8  283.49  5031.1  284.99  5042.3  285.99
  5085.7  287.26  5113.1  287.62    5129  288.22  5145.1  288.41  5169.9  288.41
#Mann= 4 ,-1 , 0
  4789.6     .05       0  4985.7     .03       0  4991.7     .05       0
  5145.1     .05       0
Bank Sta=4985.7,4991.7
XS Rating Curve= 0 ,0
Exp/Cntr=0.3,0.1

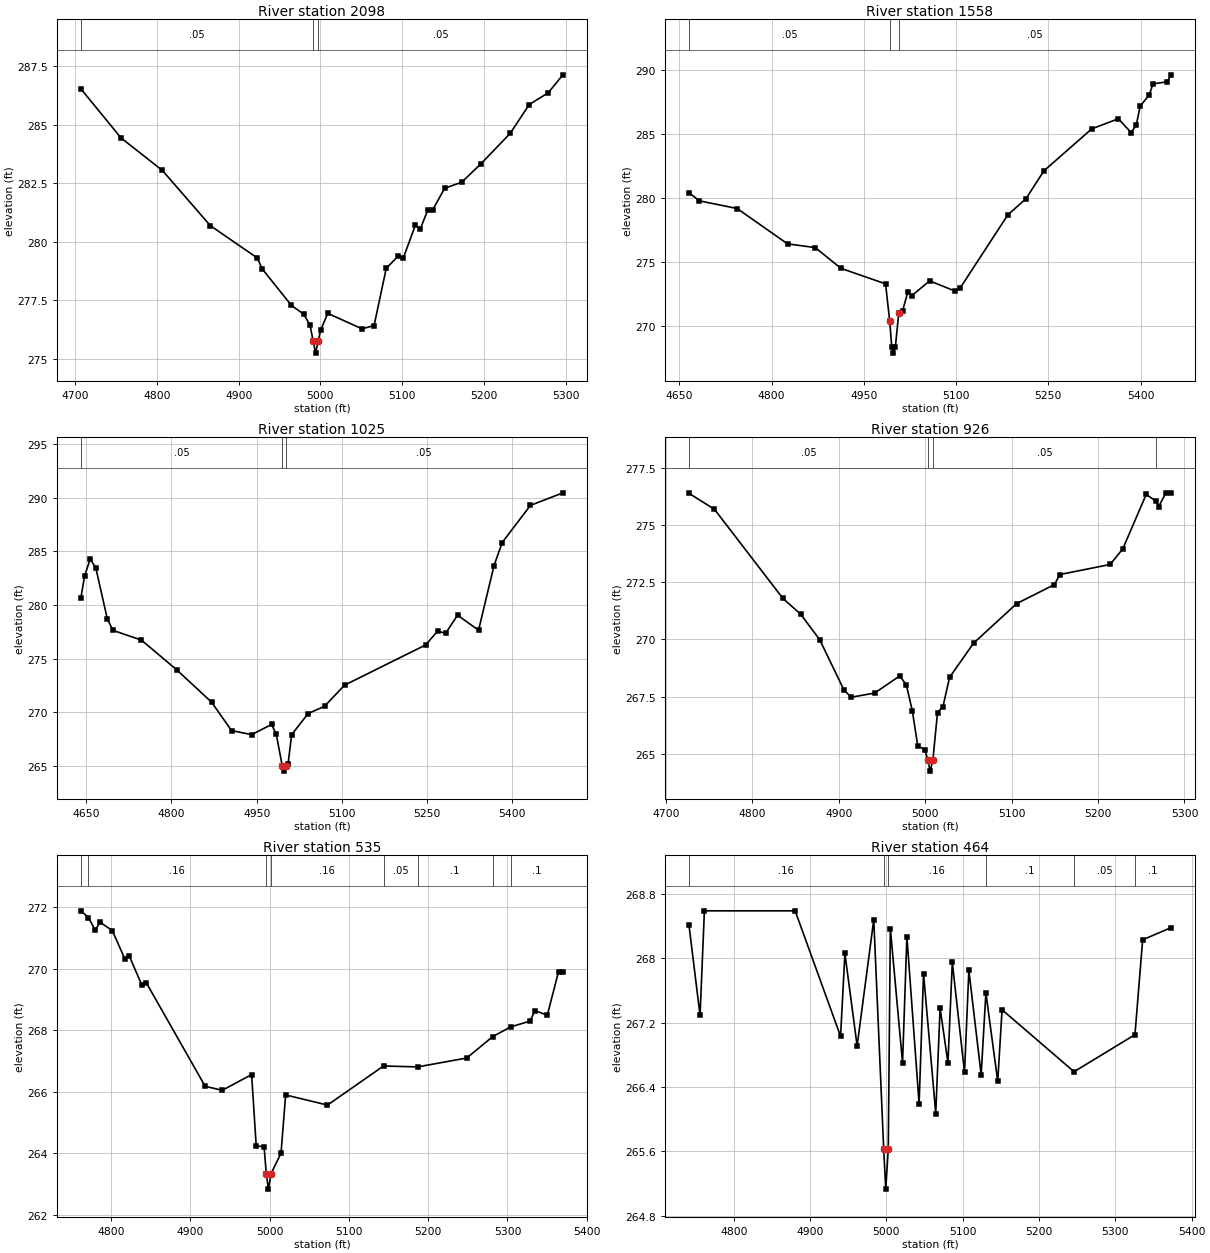
Type RM Length L Ch R = 1 ,2098    ,540,540,540
BEGIN DESCRIPTION:
UNT05299 IN WICK 4.0
END DESCRIPTION:
XS GIS Cut Line= 3
      3573142.12     10227891.62      3573418.21     10227496.05
      3573392.11     10227391.65
#Sta/Elev= 30
  4706.8  286.54    4756  284.44  4806.6  283.05  4865.3  280.69  4922.7  279.31
  4928.8  278.84  4964.5  277.28  4979.4  276.91  4987.3  276.44  4991.2  275.74
    4994  275.24  4997.2  275.74  5000.3  276.23    5009  276.94  5050.9  276.28
  5065.7  276.42  5080.6  278.87  5095.4   279.4  5101.5  279.31  5116.3  280.72
  5122.4  280.56  5131.2  281.34  5137.3  281.36  5152.1  282.29    5173  282.55
  5196.3  283.33  5232.4  284.64  5255.6  285.87  5278.8  286.37  5296.8  287.14
#Mann= 3 , 0 , 0
  4706.8     .05       0  4991.2     .03       0  4997.2     .05       0
Bank Sta=4991.2,4997.2
XS Rating Curve= 0 ,0
Exp/Cntr=0.3,0.1

Type RM Length L Ch R = 1 ,1558    ,533,533,533
BEGIN DESCRIPTION:
UNT05299 IN WICK 3.0
END DESCRIPTION:
XS GIS Cut Line= 3
      3573597.74     10228038.38      3573634.19     10227871.74
      3573997.96     10227378.06
#Sta/Elev= 30
  4665.5  280.45  4682.6  279.81    4744  279.21  4825.9  276.45    4871  276.16
  4912.7  274.54  4985.3  273.33  4992.1  270.39  4995.3  268.42    4998  267.92
  5001.3  268.42  5006.7  271.05  5012.9  271.21  5021.4  272.68  5027.6  272.39
  5056.9  273.56  5098.6  272.76    5107  273.03  5184.2  278.72  5213.5  279.97
  5242.7  282.15  5320.6  285.43  5363.8  286.22  5384.7  285.14  5393.1  285.75
  5399.3  287.21    5414  288.07  5420.2  288.94  5443.3  289.11  5449.3  289.65
#Mann= 3 , 0 , 0
  4665.5     .05       0  4992.1     .03       0  5006.7     .05       0
Bank Sta=4992.1,5006.7
XS Rating Curve= 0 ,0
Exp/Cntr=0.3,0.1

Type RM Length L Ch R = 1 ,1025    ,99,99,99
BEGIN DESCRIPTION:
UNT05299 IN WICK 2.0
END DESCRIPTION:
XS GIS Cut Line= 3
      3573795.63     10228184.24      3573962.32     10228189.45
      3574497.96     10227768.22
#Sta/Elev= 30
  4640.6  280.65  4647.1  282.68  4657.1   284.3  4667.1  283.39  4687.1  278.69
  4697.1  277.62  4747.1  276.72  4809.6  273.93  4870.5  270.94  4905.7  268.29
    4941  267.91  4976.3  268.86  4984.4  267.95  4994.9  265.01  4997.7  264.51
  5000.9  265.01  5005.2  265.18  5011.5  267.91  5040.4  269.87  5069.3  270.55
  5104.6  272.52  5247.4  276.27  5268.2  277.55  5282.6  277.36  5303.4  279.04
  5340.4  277.64  5367.6  283.66    5382  285.81  5431.7  289.27  5488.8  290.44
#Mann= 3 ,-1 , 0
  4640.6     .05       0  4994.9     .03       0  5000.9     .05       0
Bank Sta=4994.9,5000.9
XS Rating Curve= 0 ,0
Exp/Cntr=0.3,0.1

Type RM Length L Ch R = 1 ,926     ,391,391,391
BEGIN DESCRIPTION:
Mapping XS cf45f55d
END DESCRIPTION:
XS GIS Cut Line= 2
       3573971.3     10228292.87      3574416.45     10227956.75
#Sta/Elev= 30
  4726.5  276.38  4756.1  275.68  4835.2  271.79    4856  271.09  4877.9  269.98
    4906  267.78  4914.3  267.47  4941.4  267.65  4970.5   268.4  4978.1  268.01
  4985.1  266.87  4991.3  265.35  4999.6  265.17  5002.9  264.74  5005.7  264.24
  5008.9  264.74  5014.2   266.8  5020.5  267.06  5028.2  268.34  5055.9  269.83
  5105.8  271.56  5149.5  272.39  5155.8  272.83    5214  273.27  5228.6  273.95
  5255.7  276.33  5267.2  276.03  5270.2   275.8  5278.5   276.4  5284.3   276.4
#Mann= 4 ,-1 , 0
  4726.5     .05       0  5002.9     .03       0  5008.9     .05       0
  5267.2      .1       0
Bank Sta=5002.9,5008.9
XS Rating Curve= 0 ,0
Exp/Cntr=0.3,0.1

Type RM Length L Ch R = 1 ,535     ,71,71,71
BEGIN DESCRIPTION:
Mapping XS d6747305
END DESCRIPTION:
XS GIS Cut Line= 2
      3574122.45     10228506.44      3574646.59     10228198.12
#Sta/Elev= 30
  4761.8  271.88  4771.3  271.66    4780  271.25  4785.8  271.51  4801.4  271.24
  4817.1  270.33  4822.9  270.41  4838.5  269.48  4844.4  269.54  4918.6  266.18
  4940.1  266.05  4977.2  266.56    4983  264.24  4992.9  264.22  4995.7  263.34
  4998.4  262.84  5001.7  263.34  5014.3  264.01  5020.1   265.9  5072.9  265.57
  5143.6  266.84  5186.8  266.81  5248.7   267.1  5281.1  267.79  5304.1  268.11
  5328.7   268.3  5334.5  268.64  5350.2  268.49  5364.4   269.9  5369.9   269.9
#Mann= 8 ,-1 , 0
  4761.8     .05       0  4771.3     .16       0  4995.7     .07       0
  5001.7     .16       0  5143.6     .05       0  5186.8      .1       0
  5281.1     .05       0  5304.1      .1       0
Bank Sta=4995.7,5001.7
XS Rating Curve= 0 ,0
Exp/Cntr=0.3,0.1

Type RM Length L Ch R = 1 ,464     ,223,223,223
BEGIN DESCRIPTION:
Mapping XS 9762cb72
END DESCRIPTION:
XS GIS Cut Line= 2
      3574145.39     10228564.28      3574697.34     10228257.45
#Sta/Elev= 30
  4741.3  268.42  4755.9  267.29  4761.6  268.59  4880.5  268.59    4940  267.03
  4945.7  268.06  4961.7  266.91  4983.5  268.48  4996.5  265.63  4999.2  265.13
  5002.5  265.63  5005.2  268.37  5021.2   266.7  5026.9  268.27  5042.9  266.19
  5048.7  267.81  5064.7  266.07  5070.4  267.38  5080.7   266.7  5086.4  267.95
  5102.4  266.58  5108.1  267.85  5124.2  266.55  5130.4  267.57  5145.9  266.47
  5151.6  267.36  5245.9  266.59  5325.7  267.05  5335.8  268.23  5372.8  268.38
#Mann= 6 ,-1 , 0
  4741.3     .16       0  4996.5     .07       0  5002.5     .16       0
  5130.4      .1       0  5245.9     .05       0  5325.7      .1       0
Bank Sta=4996.5,5002.5
XS Rating Curve= 0 ,0
Exp/Cntr=0.3,0.1

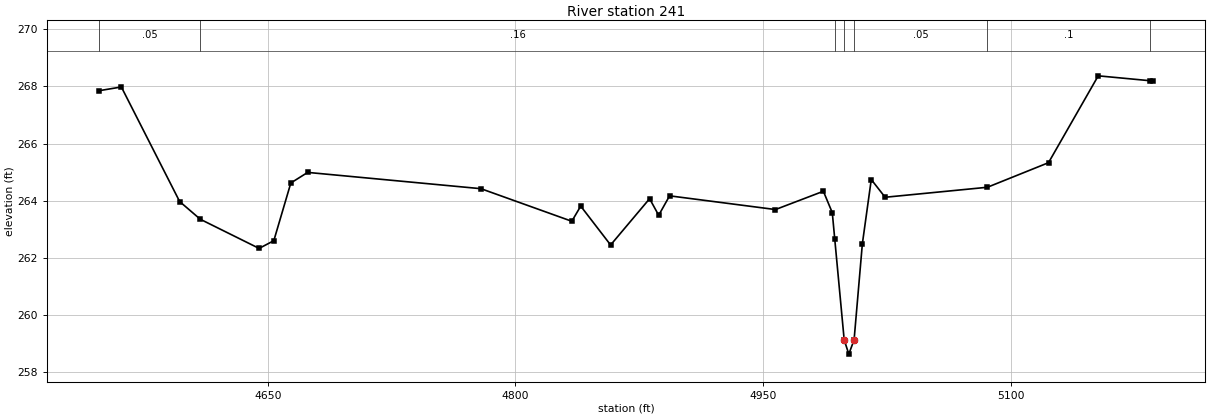
Type RM Length L Ch R = 1 ,241     ,0,0,0
BEGIN DESCRIPTION:
UNT05299 IN WICK 1.0
END DESCRIPTION:
XS GIS Cut Line= 4
      3574089.02     10228585.97      3574363.84     10228648.56
      3574584.93     10228553.81      3574593.95     10228438.76
#Sta/Elev= 30
    4548  267.85  4561.4  267.98  4596.7  263.97  4609.2  263.35  4644.8  262.33
  4653.7   262.6    4664  264.62  4674.2  264.99  4779.1  264.42  4834.1  263.28
  4839.5  263.81  4857.6  262.45  4881.2  264.07  4886.7  263.49  4893.3  264.17
  4957.4  263.69  4986.4  264.33  4991.8  263.58  4993.3  262.65    4999  259.13
  5001.8  258.63    5005  259.13    5010  262.49  5015.4  264.74  5023.8  264.12
  5085.7  264.47  5122.7  265.33  5152.8  268.37  5183.9   268.2  5185.8   268.2
#Mann= 7 ,-1 , 0
    4548     .05       0  4609.2     .16       0  4993.3     .05       0
    4999     .03       0    5005     .05       0  5085.7      .1       0
  5183.9     .05       0
Bank Sta=4999,5005
XS Rating Curve= 0 ,0
Exp/Cntr=0.3,0.1

Chan Stop Cuts=-1
Use User Specified Reach Order=0
Composite Channel Slope=5