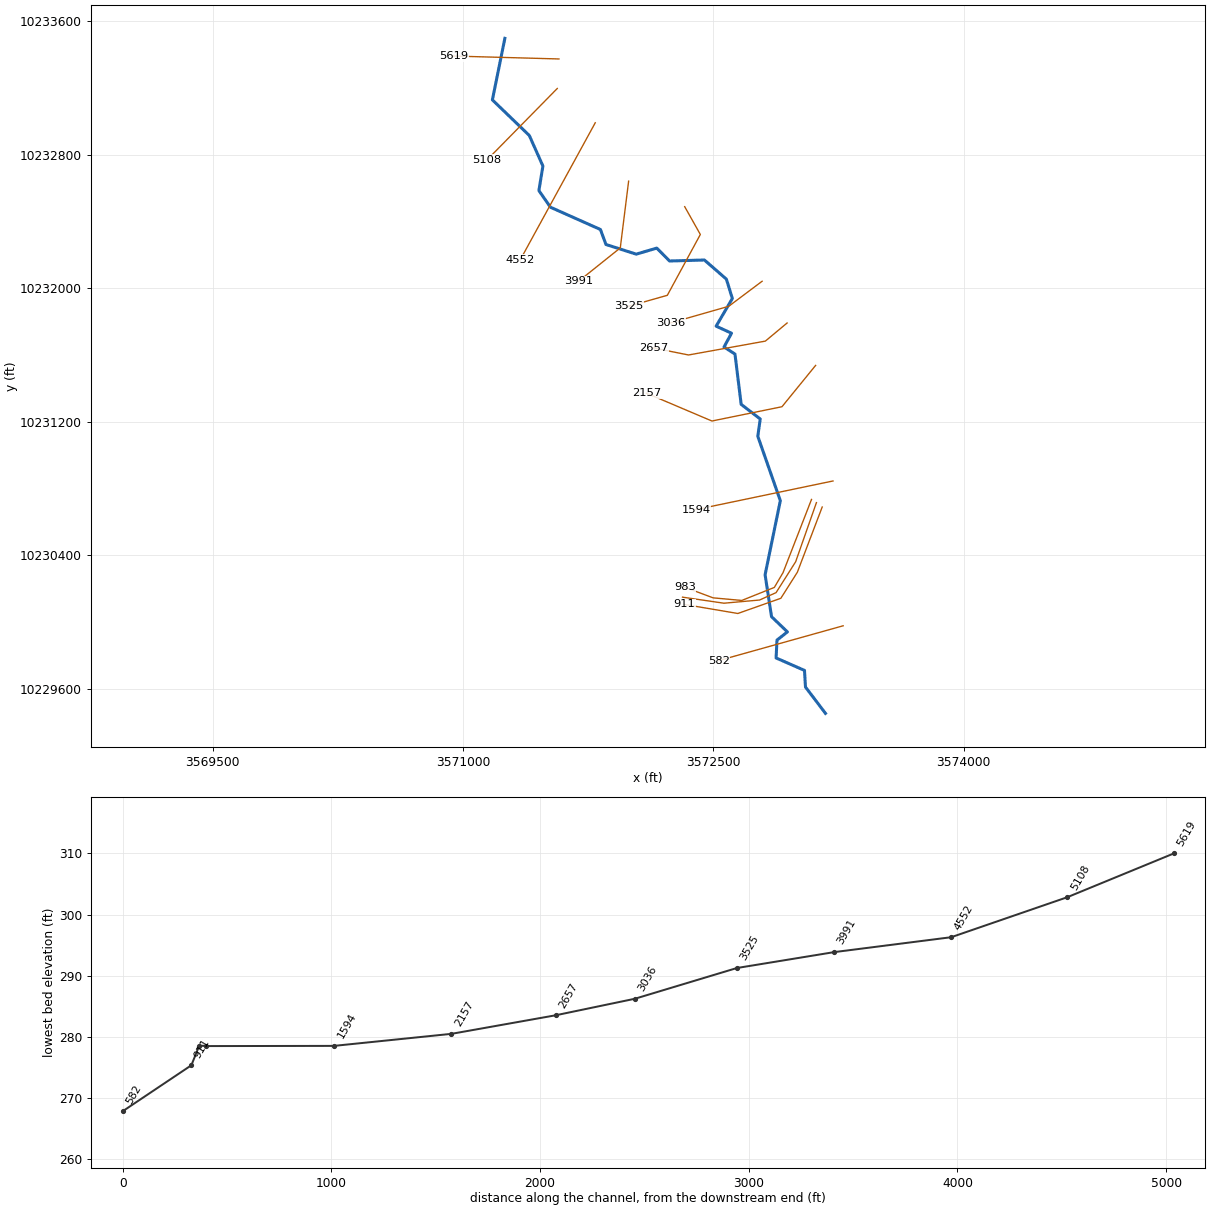
--- BRUSHYCREEKTRIB1.prj (project) ---

Proj Title=BRUSHY CREEK TRIB 14
Current Plan=p01
Default Exp/Contr=0.3,0.1
English Units
Geom File=g01
Flow File=f01
Plan File=p01
Y Axis Title=Elevation
X Axis Title(PF)=Main Channel Distance
X Axis Title(XS)=Station
BEGIN DESCRIPTION:
UNT05298 IN WICK
END DESCRIPTION:
DSS Export Rating Curves= 0
DSS Export Rating Curve Sorted= 0
DSS Export Volume Flow Curves= 0
DXF OffsetX= 0
DXF OffsetY= 0
DXF ScaleX= 1
DXF ScaleY= 10

--- BRUSHYCREEKTRIB1.p01 (plan) ---

Plan Title=Multiple Run
Short Identifier=Multiple
Geom File=g01
Flow File=f01
Subcritical Flow
K Sum by GR= 0
Std Step Tol= 0.01
Critical Tol= 0.01
Num of Std Step Trials= 20
Max Error Tol= 0.3
Flow Tol Ratio= 0.001
Split Flow NTrial= 30
Split Flow Tol= 0.02
Split Flow Ratio= 0.02
Log Output Level= 0
Friction Slope Method= 1
Unsteady Friction Slope Method= 2
Unsteady Bridges Friction Slope Method= 1
Parabolic Critical Depth
Global Vel Dist=  1 , 1 , 1
Global Log Level= 0
CheckData=True
Encroach Param= -1, 0, 0, 0
BEGIN DESCRIPTION:
Multiple Run
END DESCRIPTION:

--- BRUSHYCREEKTRIB1.f01 (steady flow) ---

Flow Title=Multiple
Program Version=4.10
Number of Profiles= 7
Profile Names=10-year,25-year,50-year,1pct_min,100-year,1pct_plu,500-year
River Rch & RM=UNT05298 IN WICK,Reach-1         ,5619
     207     261     303     258     349     473     465
River Rch & RM=BRUSHYCRTR14,Reach-1         ,5619
     207     261     303     258     349     473     465
Boundary for River Rch & Prof#=BRUSHYCRTR14,Reach-1         , 1
Up Type= 0
Dn Type= 3
Dn Slope=0.005
Boundary for River Rch & Prof#=BRUSHYCRTR14,Reach-1         , 2
Up Type= 0
Dn Type= 3
Dn Slope=0.005
Boundary for River Rch & Prof#=BRUSHYCRTR14,Reach-1         , 3
Up Type= 0
Dn Type= 3
Dn Slope=0.005
Boundary for River Rch & Prof#=BRUSHYCRTR14,Reach-1         , 4
Up Type= 0
Dn Type= 3
Dn Slope=0.005
Boundary for River Rch & Prof#=BRUSHYCRTR14,Reach-1         , 5
Up Type= 0
Dn Type= 3
Dn Slope=0.005
Boundary for River Rch & Prof#=BRUSHYCRTR14,Reach-1         , 6
Up Type= 0
Dn Type= 3
Dn Slope=0.005
Boundary for River Rch & Prof#=BRUSHYCRTR14,Reach-1         , 7
Up Type= 0
Dn Type= 3
Dn Slope=0.005
DSS Import GetInterval= 0
DSS Import GetPeak= 0
DSS Import FillOption= 0

--- BRUSHYCREEKTRIB1.g01 (geometry) ---

Geom Title=Existing Conditions
Program Version=4.10

River Reach=BRUSHYCRTR14    ,Reach-1
Reach XY= 30
      3571250.42     10233497.78      3571175.55     10233128.86
      3571396.81     10232915.53      3571478.41     10232732.37
      3571454.28     10232585.23      3571523.72     10232485.41
       3571823.2     10232351.94      3571856.22     10232262.08
      3572037.66     10232204.21      3572160.79     10232240.37
       3572237.6     10232163.12      3572446.33     10232169.12
      3572578.03     10232054.63      3572613.88     10231938.31
       3572516.7     10231772.55      3572608.92     10231730.19
      3572564.01     10231647.57      3572629.57     10231605.43
      3572666.79     10231303.91      3572781.04     10231216.05
      3572766.36     10231112.66      3572901.44     10230726.68
      3572810.18     10230282.56      3572848.79     10230031.19
      3572943.84     10229940.04      3572881.34     10229890.56
      3572876.13     10229783.79      3573046.27     10229709.14
      3573052.35     10229609.31      3573172.11     10229451.64

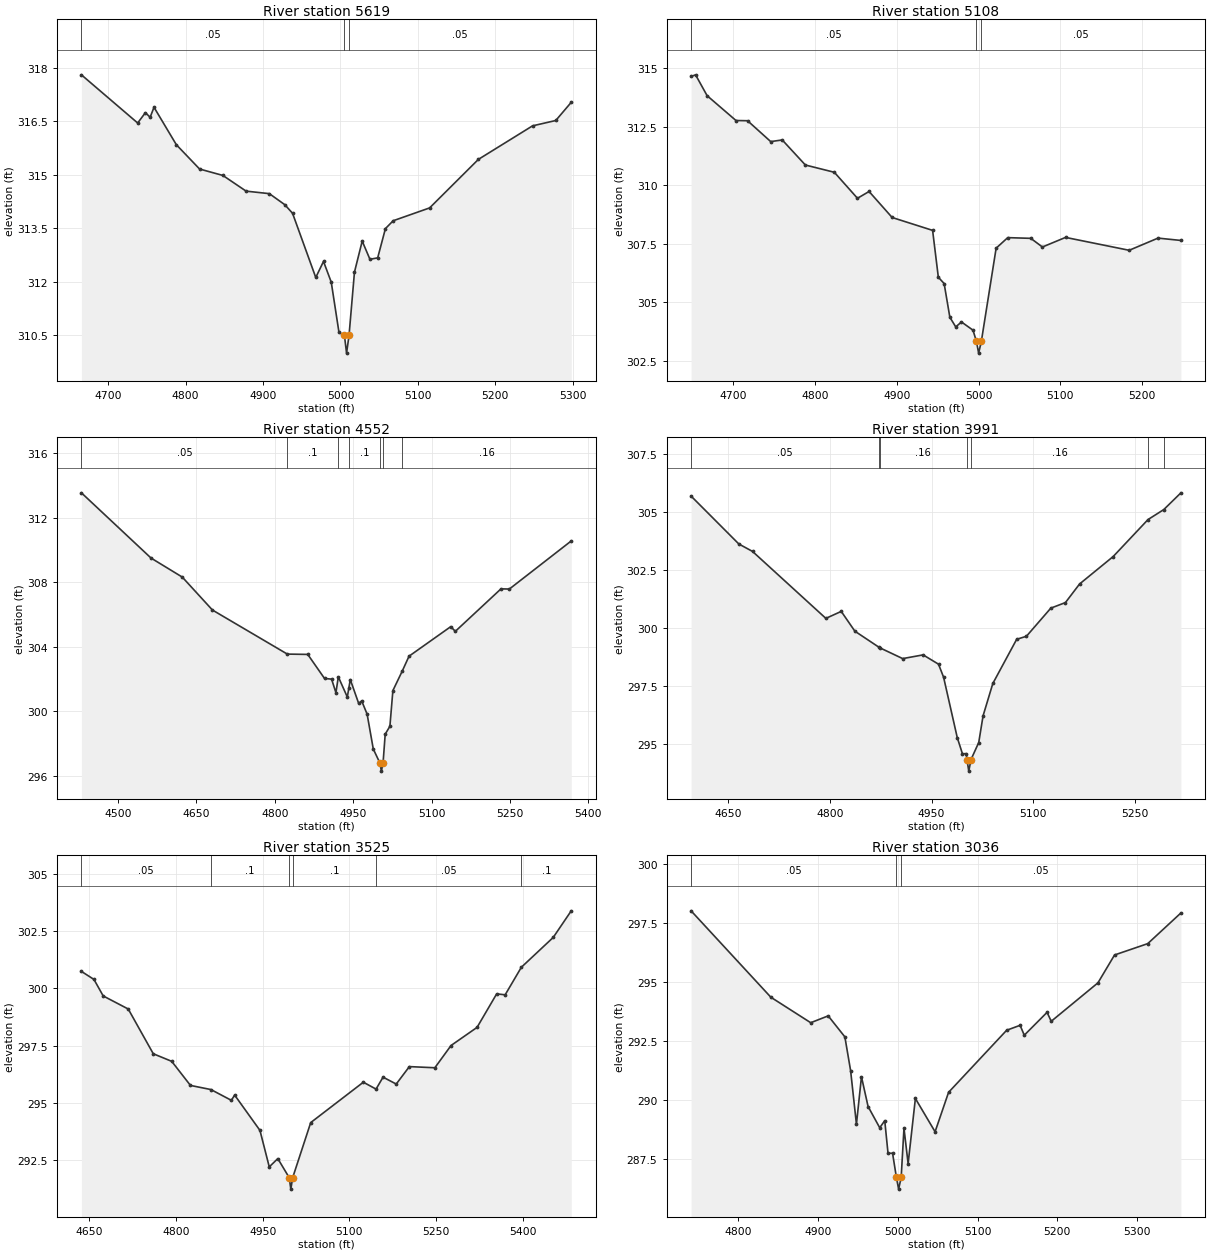
Type RM Length L Ch R = 1 ,5619    ,511,511,511
BEGIN DESCRIPTION:
UNT05298 IN WICK 11.0
END DESCRIPTION:
XS GIS Cut Line= 2
      3571574.79     10233374.16      3570942.13     10233391.64
#Sta/Elev= 30
  4665.3   317.8    4738  316.45    4748  316.74  4754.1  316.61  4759.1  316.89
    4788  315.84    4818  315.16  4848.1  314.98  4878.1  314.54  4908.1  314.47
  4928.1  314.16  4938.1  313.92  4968.1  312.12  4978.1  312.57  4988.1  311.99
  4998.1  310.58  5005.1   310.5  5007.9     310  5011.1   310.5  5018.1  312.27
  5028.1  313.14  5038.1  312.63  5048.1  312.67  5058.1  313.49  5068.1  313.71
  5115.2  314.07  5178.2  315.43  5248.2  316.37  5278.2  316.52  5298.2  317.03
#Mann= 3 ,-1 , 0
  4665.3     .05       0  5005.1     .03       0  5011.1     .05       0
Bank Sta=5005.1,5011.1
XS Rating Curve= 0 ,0
Exp/Cntr=0.3,0.1

Type RM Length L Ch R = 1 ,5108    ,556,556,556
BEGIN DESCRIPTION:
UNT05298 IN WICK 10.0
END DESCRIPTION:
XS GIS Cut Line= 2
      3571564.38     10233197.09      3571144.24       10232770.
#Sta/Elev= 30
  4648.3  314.64  4653.8  314.71  4667.9  313.82  4703.2  312.76  4717.4  312.75
  4745.7  311.86  4759.8  311.93  4788.1  310.86  4823.5  310.55  4851.8  309.44
    4866  309.73  4894.2  308.62  4943.7  308.07  4950.7  306.07  4957.8   305.8
  4964.8  304.36    4972  303.95    4979  304.16  4993.1  303.81  4997.3  303.33
    5000  302.83  5003.3  303.33  5021.4  307.31  5035.6  307.76  5063.8  307.73
    5078  307.36  5106.3  307.77  5184.1  307.22  5219.4  307.74  5247.4  307.64
#Mann= 3 ,-1 , 0
  4648.3     .05       0  4997.3     .03       0  5003.3     .05       0
Bank Sta=4997.3,5003.3
XS Rating Curve= 0 ,0
Exp/Cntr=0.3,0.1

Type RM Length L Ch R = 1 ,4552    ,561,561,561
BEGIN DESCRIPTION:
UNT05298 IN WICK 9.0
END DESCRIPTION:
XS GIS Cut Line= 2
      3571792.08      10232991.6      3571342.17     10232169.34
#Sta/Elev= 30
  4429.9  313.53  4563.1  309.49  4622.9  308.31  4680.6  306.27  4823.9  303.54
    4863  303.52  4895.1  302.03  4908.6  301.99  4916.9  301.15  4921.5  302.13
  4938.7  300.88  4941.7  301.45  4944.4  301.96  4960.5  300.48  4966.2  300.64
  4976.6  299.82  4988.4  297.66  5001.1  296.79  5003.9  296.29  5007.1  296.79
  5011.2  298.58  5020.2  299.07  5025.9  301.28    5044   302.5  5056.8  303.41
  5136.6  305.24  5145.4  304.95  5232.7  307.58  5248.8  307.57  5367.2  310.55
#Mann= 7 ,-1 , 0
  4429.9     .05       0  4823.9      .1       0  4921.5     .16       0
  4941.7      .1       0  5001.1     .07       0  5007.1      .1       0
    5044     .16       0
Bank Sta=5001.1,5007.1
XS Rating Curve= 0 ,0
Exp/Cntr=0.3,0.1

Type RM Length L Ch R = 1 ,3991    ,466,466,466
BEGIN DESCRIPTION:
UNT05298 IN WICK 8.0
END DESCRIPTION:
XS GIS Cut Line= 3
       3571992.1      10232641.6      3571942.11     10232241.64
      3571692.13     10232041.66
#Sta/Elev= 30
  4594.9  305.68  4665.4  303.62  4685.6   303.3  4793.9  300.42  4816.6  300.72
  4836.7  299.87  4871.7  299.19  4873.2  299.16  4907.3  298.69  4937.5  298.85
  4960.2  298.45  4967.7  297.89  4987.9  295.29  4995.5   294.6  5001.2   294.6
  5002.2  294.35  5004.9  293.85  5008.2  294.35  5019.6  295.08    5026  296.23
  5040.4  297.62  5075.6  299.52    5090  299.65    5126  300.86  5147.6   301.1
  5168.5   301.9  5218.1  303.08  5269.5  304.67  5292.8   305.1  5318.1  305.82
#Mann= 7 ,-1 , 0
  4594.9     .05       0  4871.7      .1       0  4873.2     .16       0
  5002.2     .07       0  5008.2     .16       0  5269.5     .05       0
  5292.8     .16       0
Bank Sta=5002.2,5008.2
XS Rating Curve= 0 ,0
Exp/Cntr=0.3,0.1

Type RM Length L Ch R = 1 ,3525    ,489,489,489
BEGIN DESCRIPTION:
UNT05298 IN WICK 7.0
END DESCRIPTION:
XS GIS Cut Line= 4
      3572328.25     10232488.76      3572422.01     10232322.08
      3572224.09     10231957.49      3571992.14     10231891.65
#Sta/Elev= 30
  4636.5  300.74  4658.2  300.39  4674.2  299.67  4717.5   299.1  4760.8  297.15
  4792.7  296.82  4825.1  295.77  4860.5  295.59  4895.9  295.12  4901.5  295.35
  4945.3  293.81  4961.4  292.22  4976.2  292.58  4995.9  291.75  4998.7  291.25
  5001.9  291.75  5033.1  294.15  5124.1  295.91  5146.1  295.61  5158.2  296.13
    5181  295.83  5203.7  296.59  5247.8  296.54  5275.8  297.51  5320.8   298.3
  5354.7  299.76  5369.4  299.72  5397.4  300.92  5452.5  302.22  5483.7  303.38
#Mann= 6 ,-1 , 0
  4636.5     .05       0  4860.5      .1       0  4995.9     .07       0
  5001.9      .1       0  5146.1     .05       0  5397.4      .1       0
Bank Sta=4995.9,5001.9
XS Rating Curve= 0 ,0
Exp/Cntr=0.3,0.1

Type RM Length L Ch R = 1 ,3036    ,379,379,379
BEGIN DESCRIPTION:
UNT05298 IN WICK 6.0
END DESCRIPTION:
XS GIS Cut Line= 3
      3572792.14     10232041.67      3572592.11     10231891.64
      3572242.06     10231791.63
#Sta/Elev= 30
  4740.9  298.01  4840.9  294.35  4890.9  293.27  4912.8  293.56  4933.7  292.67
  4940.9  291.24  4948.2  288.97  4954.5  290.98  4962.8  289.72  4977.4  288.82
  4983.7  289.12  4987.8  287.74  4993.5  287.74  4998.3  286.72  5001.1  286.22
  5004.3  286.72  5007.8   288.8    5013   287.3  5022.1  290.06  5046.8  288.65
  5063.7  290.32  5136.5  292.95  5153.4  293.16  5158.6  292.74  5187.2  293.71
  5192.4  293.33    5251  294.96  5271.8  296.14  5313.4  296.62    5355  297.92
#Mann= 3 ,-1 , 0
  4740.9     .05       0  4998.3     .03       0  5004.3     .05       0
Bank Sta=4998.3,5004.3
XS Rating Curve= 0 ,0
Exp/Cntr=0.3,0.1

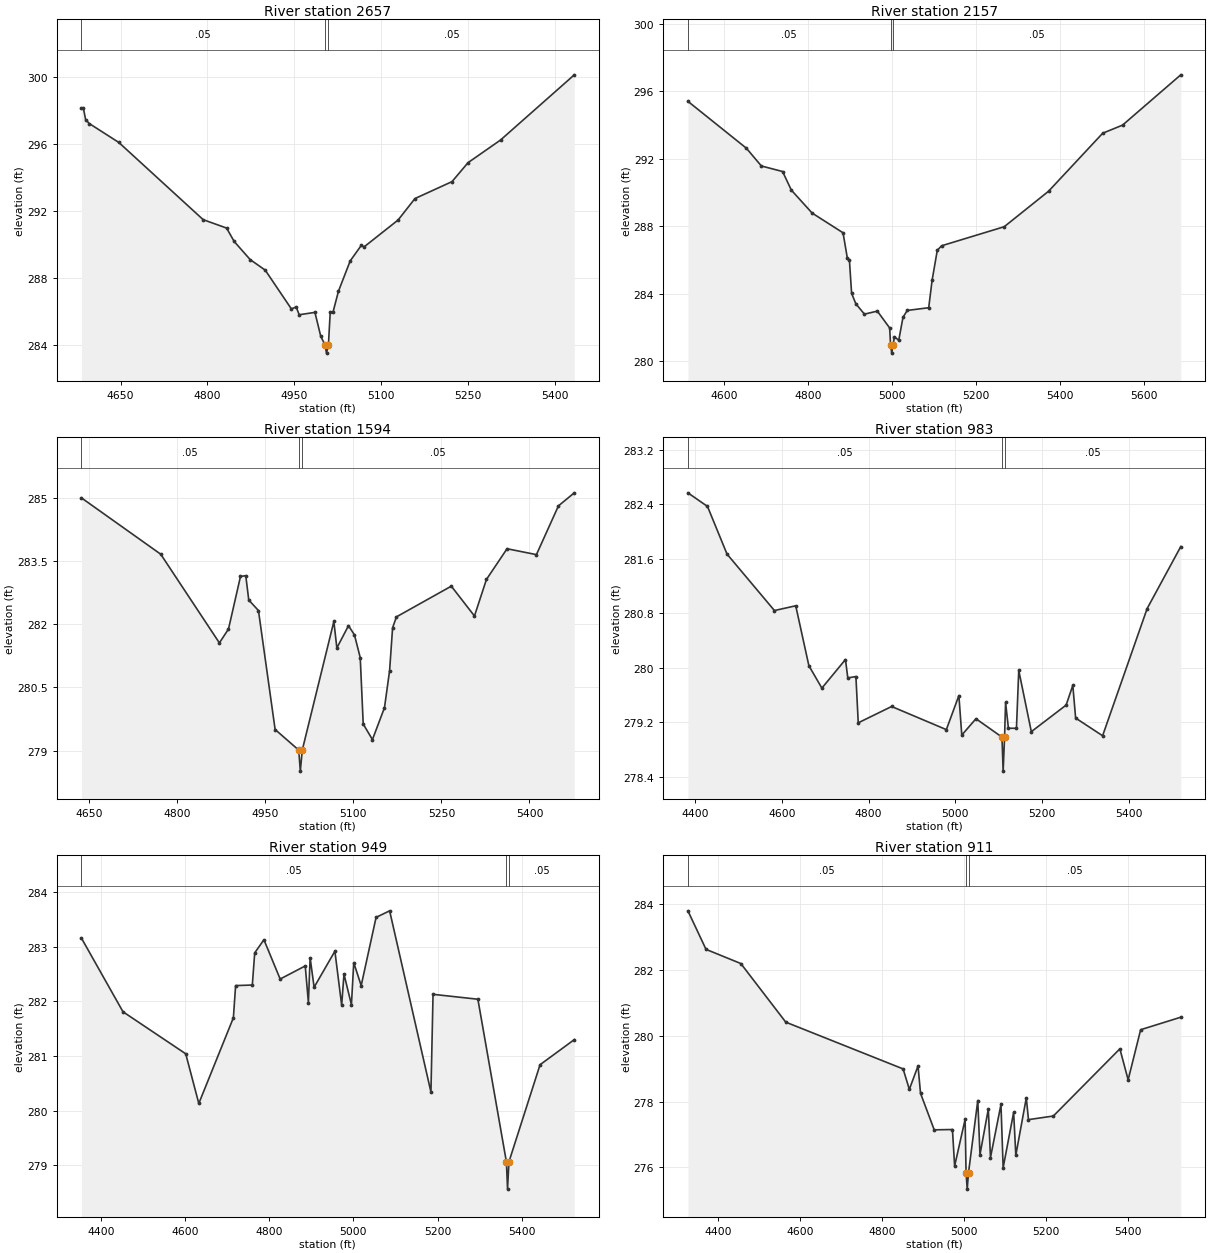
Type RM Length L Ch R = 1 ,2657    ,500,500,500
BEGIN DESCRIPTION:
UNT05298 IN WICK 5.0
END DESCRIPTION:
XS GIS Cut Line= 4
      3572942.11     10231791.64      3572811.67     10231682.95
      3572351.17     10231599.83      3572142.14     10231641.63
#Sta/Elev= 30
  4582.5  298.15  4585.8  298.15  4589.7  297.45  4596.2  297.21  4646.9  296.09
  4792.7  291.48  4833.1  290.98  4846.2  290.18  4873.8   289.1  4899.8  288.47
  4944.9  286.16  4953.3  286.27  4958.4  285.81  4985.6  285.95  4995.7  284.52
  5002.9  284.02  5005.6  283.52  5008.9  284.02    5012  285.95  5017.1     286
  5026.2  287.21  5046.5  289.02  5065.5  289.94  5070.6  289.86  5129.2  291.46
  5158.3  292.74  5222.3  293.75  5249.9  294.88    5306  296.23  5433.4  300.12
#Mann= 3 ,-1 , 0
  4582.5     .05       0  5002.9     .03       0  5008.9     .05       0
Bank Sta=5002.9,5008.9
XS Rating Curve= 0 ,0
Exp/Cntr=0.3,0.1

Type RM Length L Ch R = 1 ,2157    ,563,563,563
BEGIN DESCRIPTION:
UNT05298 IN WICK 4.0
END DESCRIPTION:
XS GIS Cut Line= 4
      3573112.98     10231537.35      3572911.29     10231289.68
      3572491.45     10231204.02      3572099.08     10231370.69
#Sta/Elev= 30
  4514.5   295.4  4653.9  292.62  4689.5  291.57  4740.1  291.24  4760.9  290.14
  4810.4  288.78  4884.1  287.61  4894.2  286.13  4899.3  285.99  4904.5  284.02
  4914.7   283.4  4935.1  282.79  4965.8  282.97  4995.2  281.97  4997.3  280.98
  5000.1  280.48  5003.3  280.98  5006.6  281.45  5016.8  281.24    5027  282.61
  5037.2  283.01  5088.2  283.17  5096.3   284.8  5108.6  286.57  5118.8  286.84
  5268.1  287.97  5373.6  290.07  5502.7  293.51    5550  293.99  5688.7  296.97
#Mann= 3 ,-1 , 0
  4514.5     .05       0  4997.3     .03       0  5003.3     .05       0
Bank Sta=4997.3,5003.3
XS Rating Curve= 0 ,0
Exp/Cntr=0.3,0.1

Type RM Length L Ch R = 1 ,1594    ,611,611,611
BEGIN DESCRIPTION:
UNT05298 IN WICK 3.0
END DESCRIPTION:
XS GIS Cut Line= 2
      3573217.19     10230844.66      3572395.71     10230673.08
#Sta/Elev= 30
  4637.1  285.01  4772.1  283.67    4872  281.56  4887.5  281.89  4907.9  283.14
  4916.9  283.16    4922  282.58  4938.5  282.33  4966.9   279.5  5007.1  279.01
  5009.8  278.51  5013.1  279.01  5066.9  282.07    5072  281.44  5091.8  281.97
    5102  281.75  5111.8  281.21  5116.9  279.63  5132.6  279.26  5153.1  280.02
  5161.8   280.9  5166.9  281.92  5173.5  282.18  5266.9  282.91  5306.3   282.2
  5326.7  283.07  5361.8   283.8  5411.8  283.66  5449.3  284.82  5476.3  285.13
#Mann= 3 ,-1 , 0
  4637.1     .05       0  5007.1     .03       0  5013.1     .05       0
Bank Sta=5007.1,5013.1
XS Rating Curve= 0 ,0
Exp/Cntr=0.3,0.1

Type RM Length L Ch R = 1 ,983     ,34,34,34
BEGIN DESCRIPTION:
Mapping XS 0614e689
END DESCRIPTION:
XS GIS Cut Line= 6
      3573088.28     10230733.86      3572917.67     10230295.17
      3572865.58     10230206.63      3572670.27      10230128.5
      3572498.39     10230144.13       3572329.5     10230207.25
#Sta/Elev= 30
  4383.1  282.57  4428.3  282.37  4473.3  281.67  4582.7  280.84  4631.8  280.91
  4662.1  280.03  4692.1   279.7  4746.5  280.12  4751.9  279.85  4770.6  279.87
    4776  279.19    4853  279.43  4979.2  279.09  5008.1  279.59  5014.8  279.01
  5047.5  279.25  5107.5  278.98  5110.2  278.48  5113.5  278.98  5115.8  279.49
  5122.4  279.11  5140.9  279.11  5146.2  279.96  5175.2  279.06  5255.4  279.45
  5270.9  279.74  5277.4  279.26  5339.6     279  5442.4  280.87  5519.9  281.78
#Mann= 3 ,-1 , 0
  4383.1     .05       0  5107.5    .033       0  5113.5     .05       0
Bank Sta=5107.5,5113.5
XS Rating Curve= 0 ,0
Exp/Cntr=0.3,0.1

Type RM Length L Ch R = 1 ,949     ,38,38,38
BEGIN DESCRIPTION:
Mapping XS 4248a692
END DESCRIPTION:
XS GIS Cut Line= 6
      3573117.82     10230714.83      3572993.19     10230360.27
        3572876.     10230175.38      3572777.04      10230131.1
       3572563.5     10230112.01      3572315.33      10230148.2
#Sta/Elev= 30
  4353.5  283.16  4452.3  281.81  4601.4  281.04  4632.5  280.13  4714.7   281.7
    4720  282.29  4759.7   282.3  4765.4  282.89  4787.3  283.13  4825.9  282.41
  4885.5  282.65    4893  281.98  4897.1   282.8  4906.6  282.26    4956  282.92
  4972.1  281.93  4977.6   282.5  4995.3  281.94  5000.8  282.71  5018.5  282.29
  5053.9  283.54  5086.1  283.66  5184.3  280.34  5189.3  282.13  5295.9  282.04
  5363.7  279.06  5366.4  278.56  5369.7  279.06  5443.7  280.84  5525.1   281.3
#Mann= 3 ,-1 , 0
  4353.5     .05       0  5363.7    .033       0  5369.7     .05       0
Bank Sta=5363.7,5369.7
XS Rating Curve= 0 ,0
Exp/Cntr=0.3,0.1

Type RM Length L Ch R = 1 ,911     ,329,329,329
BEGIN DESCRIPTION:
Mapping XS 7457d21d
END DESCRIPTION:
XS GIS Cut Line= 5
      3573152.51     10230688.72       3573003.6     10230297.77
      3572904.64     10230141.52      3572646.83     10230050.38
      3572325.55     10230104.79
#Sta/Elev= 30
  4325.6  283.79  4369.8  282.62  4454.7  282.19  4564.4  280.41  4850.7  278.99
  4865.9  278.37  4887.1  279.08  4893.2  278.25  4926.6  277.14  4971.1  277.15
  4976.4  276.04    5002  277.46  5004.3  275.84  5007.1  275.34  5010.3  275.84
  5032.9  278.03  5038.3  276.39  5058.6  277.77  5063.9   276.3  5089.5  277.91
  5094.8  275.99  5120.4  277.67  5125.7  276.37  5151.3  278.11  5156.6  277.45
  5217.3  277.56  5379.6   279.6  5399.8  278.66  5430.3  280.18  5528.2  280.56
#Mann= 3 ,-1 , 0
  4325.6     .05       0  5004.3    .035       0  5010.3     .05       0
Bank Sta=5004.3,5010.3
XS Rating Curve= 0 ,0
Exp/Cntr=0.3,0.1

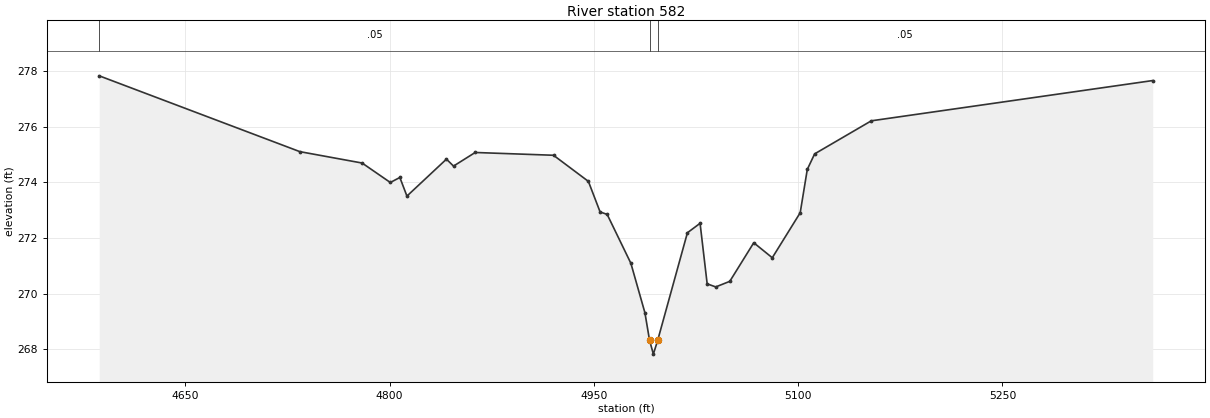
Type RM Length L Ch R = 1 ,582     ,0,0,0
BEGIN DESCRIPTION:
UNT05298 IN WICK 1.0
END DESCRIPTION:
XS GIS Cut Line= 2
      3573277.94      10229976.6      3572533.13     10229768.26
#Sta/Elev= 30
  4586.9  277.84  4734.2  275.11  4779.9   274.7  4800.6     274  4807.6  274.18
  4812.8  273.51  4841.8  274.84    4847  274.59  4862.9  275.08  4920.4  274.98
    4946  274.04  4954.6  272.94  4959.8  272.85  4977.2  271.09  4987.5  269.31
  4990.9  268.32  4993.7  267.82  4996.9  268.32  5018.7  272.19    5028  272.53
  5033.2  270.35  5039.5  270.24  5049.8  270.44  5067.4  271.83    5081  271.29
  5101.5  272.91  5106.7  274.47  5112.1  275.03  5153.7  276.22  5360.3  277.67
#Mann= 3 ,-1 , 0
  4586.9     .05       0  4990.9    .035       0  4996.9     .05       0
Bank Sta=4990.9,4996.9
XS Rating Curve= 0 ,0
Exp/Cntr=0.3,0.1

Chan Stop Cuts=-1
Use User Specified Reach Order=0
Composite Channel Slope=5