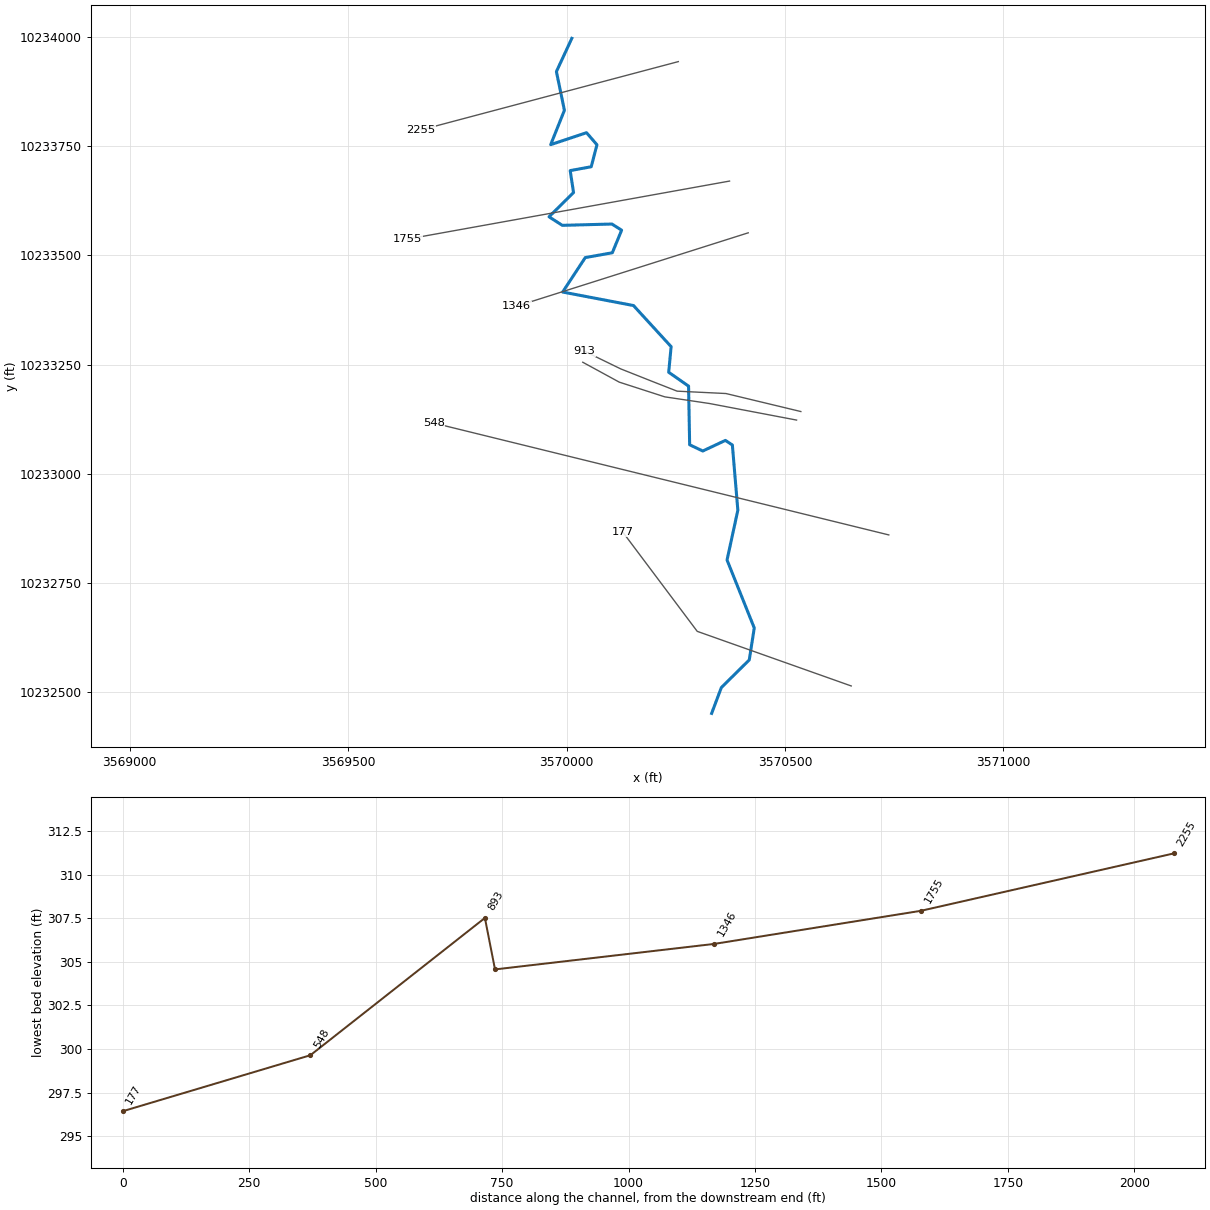
--- BRUSHY CREEK TRIB 15 1.prj (project) ---

Proj Title=BRUSHY CREEK TRIB 15 1 Base Level Engineering
Current Plan=p01
Default Exp/Contr=0.3,0.1
English Units
Geom File=g01
Flow File=f01
Plan File=p01
Y Axis Title=Elevation
X Axis Title(PF)=Main Channel Distance
X Axis Title(XS)=Station
BEGIN DESCRIPTION:
BRUSHY CREEK TRIB 15 1
END DESCRIPTION:
DSS Export Rating Curves= 0
DSS Export Rating Curve Sorted= 0
DSS Export Volume Flow Curves= 0
DXF OffsetX= 0
DXF OffsetY= 0
DXF ScaleX= 1
DXF ScaleY= 10

--- BRUSHY CREEK TRIB 15 1.p01 (plan) ---

Plan Title=Multiple Run
Short Identifier=Multiple
Geom File=g01
Flow File=f01
Subcritical Flow
K Sum by GR= 0
Std Step Tol= 0.01
Critical Tol= 0.01
Num of Std Step Trials= 20
Max Error Tol= 0.3
Flow Tol Ratio= 0.001
Split Flow NTrial= 30
Split Flow Tol= 0.02
Split Flow Ratio= 0.02
Log Output Level= 0
Friction Slope Method= 1
Unsteady Friction Slope Method= 2
Unsteady Bridges Friction Slope Method= 1
Parabolic Critical Depth
Global Vel Dist=  1 , 1 , 1
Global Log Level= 0
CheckData=True
Encroach Param= -1, 0, 0, 0
BEGIN DESCRIPTION:
Multiple Run
END DESCRIPTION:

--- BRUSHY CREEK TRIB 15 1.f01 (steady flow) ---

Flow Title=Multiple
Program Version=4.10
Number of Profiles= 7
Profile Names=10-year,25-year,50-year,1pct_min,100-year,1pct_plu,500-year
River Rch & RM=BRUSHY CREEK TRI,Reach-1         ,2255
     134     164     186     156     210     285     269
Boundary for River Rch & Prof#=BRUSHY CREEK TRI,Reach-1         , 1
Up Type= 0
Dn Type= 3
Dn Slope=0.009
Boundary for River Rch & Prof#=BRUSHY CREEK TRI,Reach-1         , 2
Up Type= 0
Dn Type= 3
Dn Slope=0.009
Boundary for River Rch & Prof#=BRUSHY CREEK TRI,Reach-1         , 3
Up Type= 0
Dn Type= 3
Dn Slope=0.009
Boundary for River Rch & Prof#=BRUSHY CREEK TRI,Reach-1         , 4
Up Type= 0
Dn Type= 3
Dn Slope=0.009
Boundary for River Rch & Prof#=BRUSHY CREEK TRI,Reach-1         , 5
Up Type= 0
Dn Type= 3
Dn Slope=0.009
Boundary for River Rch & Prof#=BRUSHY CREEK TRI,Reach-1         , 6
Up Type= 0
Dn Type= 3
Dn Slope=0.009
Boundary for River Rch & Prof#=BRUSHY CREEK TRI,Reach-1         , 7
Up Type= 0
Dn Type= 3
Dn Slope=0.009
DSS Import GetInterval= 0
DSS Import GetPeak= 0
DSS Import FillOption= 0

--- BRUSHY CREEK TRIB 15 1.g01 (geometry) ---

Geom Title=Existing Conditions

River Reach=BRUSHY CREEK TRI,Reach-1
Reach XY= 30
      3570012.11     10233996.64      3569976.80     10233920.56
      3569995.13     10233831.95      3569963.71     10233753.33
      3570045.71     10233780.70      3570069.59     10233753.07
      3570056.50     10233702.74      3570008.33     10233693.91
      3570016.02     10233643.71      3569959.88     10233588.15
      3569990.36     10233568.63      3570103.88     10233571.62
      3570126.02     10233557.49      3570104.78     10233505.89
      3570042.83     10233494.80      3569991.10     10233415.98
      3570153.25     10233385.08      3570239.36     10233290.98
      3570233.81     10233232.30      3570279.29     10233200.70
      3570281.77     10233066.41      3570311.85     10233052.14
      3570363.53     10233076.41      3570379.53     10233065.90
      3570392.07     10232916.66      3570367.34     10232802.63
      3570429.65     10232647.13      3570418.19     10232573.92
      3570354.33     10232510.81      3570332.11     10232451.64

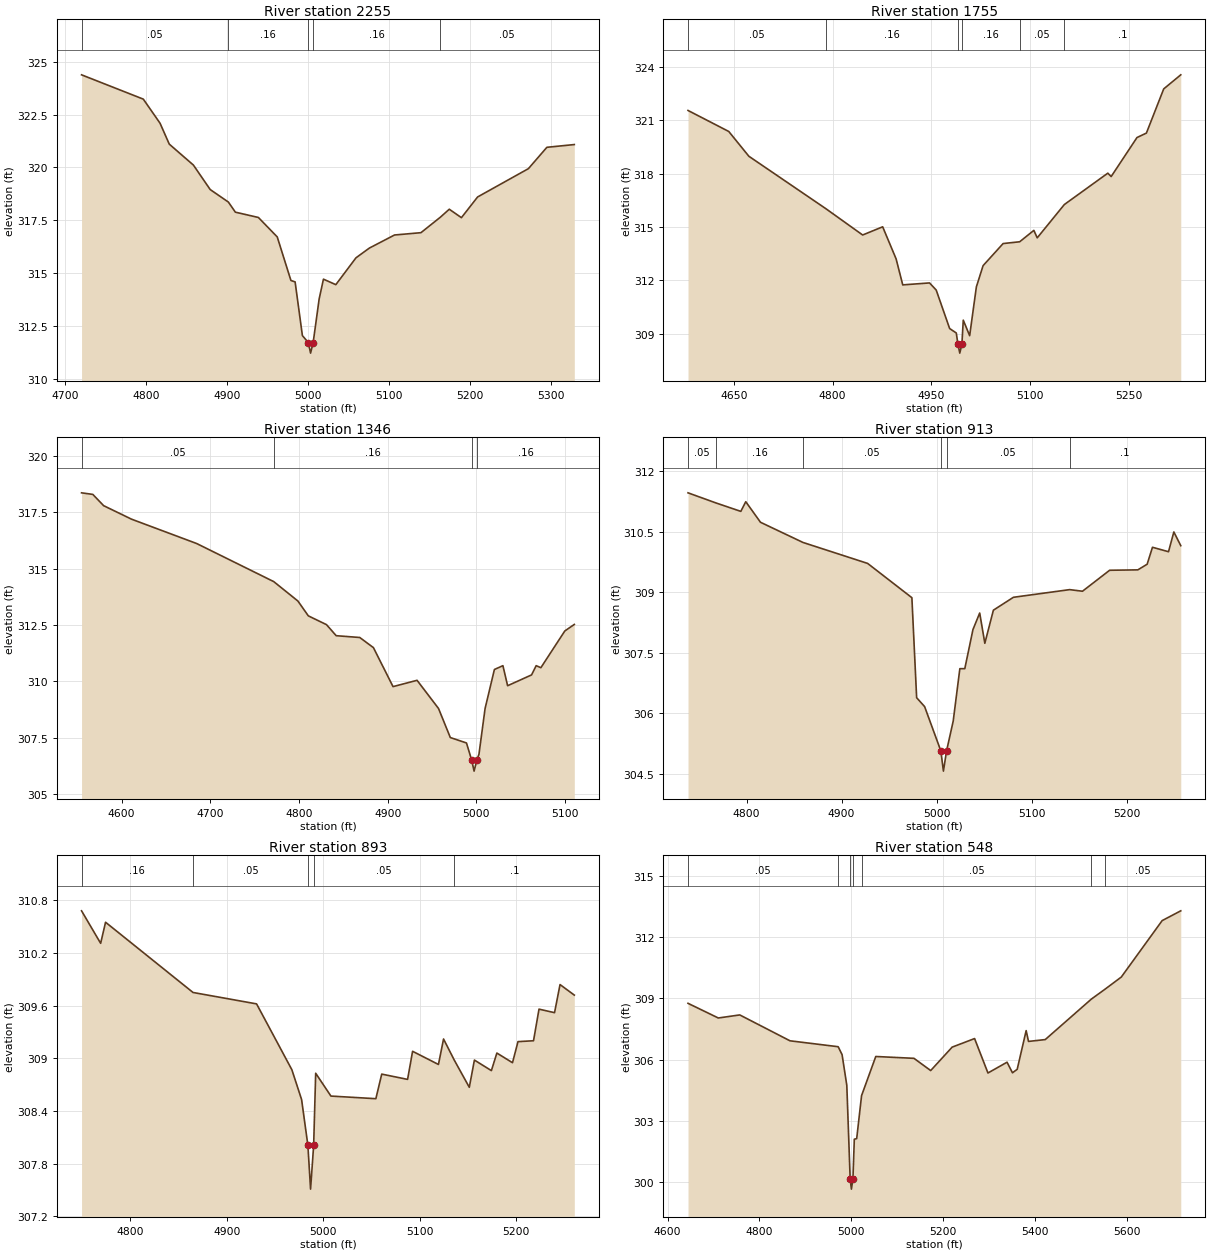
Type RM Length L Ch R = 1,2255,500,500,500
BEGIN DESCRIPTION:
UNT05296 IN WICK 11.0
END DESCRIPTION:
XS GIS Cut Line= 2
      3570255.83     10233943.38      3569667.32     10233787.14
#Sta/Elev= 30
  4720.4  324.38  4796.7  323.23  4817.4  322.09  4828.8  321.10  4858.6  320.11
  4879.4  318.95  4901.8  318.36  4910.5  317.88  4938.9  317.63  4962.2  316.71
  4979.1  314.65  4984.3  314.58  4993.3  312.04  5000.6  311.71  5003.4  311.21
  5006.6  311.71  5014.0  313.77  5019.3  314.71  5034.6  314.45  5059.5  315.72
  5076.0  316.18  5107.1  316.80  5139.8  316.91  5163.4  317.63  5174.8  318.02
  5189.8  317.62  5209.8  318.60  5272.6  319.94  5295.4  320.95  5329.3  321.08
#Mann=5,-1,0
  4720.4    0.05       0  4901.8    0.16       0  5000.6    0.07       0
  5006.6    0.16       0  5163.4    0.05       0
Bank Sta=5000.6,5006.6
Exp/Cntr=0.3,0.1

Type RM Length L Ch R = 1,1755,409,409,409
BEGIN DESCRIPTION:
UNT05296 IN WICK 10.0
END DESCRIPTION:
XS GIS Cut Line= 2
      3570373.06     10233669.96      3569636.62     10233537.24
#Sta/Elev= 30
  4580.5  321.54  4642.4  320.36  4672.9  318.97  4790.1  316.02  4845.7  314.55
  4876.1  315.01  4896.5  313.21  4906.6  311.75  4947.3  311.86  4957.4  311.46
  4977.8  309.30  4987.9  309.05  4990.4  308.42  4993.2  307.92  4996.4  308.42
  4998.5  309.77  5008.2  308.90  5018.4  311.64  5028.6  312.83  5059.0  314.07
  5084.2  314.17  5105.7  314.81  5110.8  314.39  5152.0  316.26  5218.0  318.02
  5223.1  317.83  5262.3  320.02  5276.6  320.27  5302.9  322.75  5328.8  323.54
#Mann=6,-1,0
  4580.5    0.05       0  4790.1    0.16       0  4990.4    0.07       0
  4996.4    0.16       0  5084.2    0.05       0  5152.0     0.1       0
Bank Sta=4990.4,4996.4
Exp/Cntr=0.3,0.1

Type RM Length L Ch R = 1,1346,433,433,433
BEGIN DESCRIPTION:
UNT05296 IN WICK 9.0
END DESCRIPTION:
XS GIS Cut Line= 2
      3570415.82     10233551.52      3569886.19     10233383.65
#Sta/Elev= 30
  4554.8  318.37  4567.5  318.30  4579.7  317.80  4611.2  317.20  4684.6  316.12
  4771.5  314.43  4798.7  313.57  4810.5  312.91  4831.0  312.52  4841.9  312.03
  4868.5  311.95  4883.9  311.50  4906.0  309.77  4933.1  310.05  4957.3  308.80
  4970.6  307.51  4988.8  307.27  4994.6  306.52  4997.4  306.02  5000.6  306.52
  5002.9  306.77  5009.8  308.80  5020.3  310.53  5029.9  310.70  5035.2  309.81
  5062.2  310.29  5067.4  310.70  5072.7  310.61  5099.7  312.24  5110.4  312.53
#Mann=4,-1,0
  4554.8    0.05       0  4771.5    0.16       0  4994.6    0.07       0
  5000.6    0.16       0
Bank Sta=4994.6,5000.6
Exp/Cntr=0.3,0.1

Type RM Length L Ch R = 1,913,20,20,20
BEGIN DESCRIPTION:
Mapping XS 9b285071
END DESCRIPTION:
XS GIS Cut Line= 6
      3570536.27     10233142.46      3570364.84     10233183.69
      3570253.08     10233189.12      3570197.74     10233210.82
      3570123.95     10233240.11      3570041.46     10233280.28
#Sta/Elev= 30
  4738.3  311.46  4767.6  311.21  4793.9  311.00  4799.1  311.24  4814.6  310.73
  4859.3  310.23  4927.4  309.71  4974.0  308.86  4979.0  306.38  4987.4  306.16
  5004.5  305.06  5007.2  304.56  5010.5  305.06  5017.5  305.80  5024.5  307.10
  5029.7  307.10  5038.3  308.07  5045.4  308.48  5050.8  307.73  5059.8  308.55
  5080.9  308.87  5140.1  309.06  5153.6  309.02  5182.2  309.54  5211.9  309.55
  5221.7  309.69  5227.3  310.11  5244.2  310.00  5249.8  310.49  5257.1  310.15
#Mann=6,-1,0
  4738.3    0.05       0  4767.6    0.16       0  4859.3    0.05       0
  5004.5    0.03       0  5010.5    0.05       0  5140.1     0.1       0
Bank Sta=5004.5,5010.5
Exp/Cntr=0.3,0.1

Type RM Length L Ch R = 1,893,345,345,345
BEGIN DESCRIPTION:
Mapping XS fdf704b3
END DESCRIPTION:
XS GIS Cut Line= 5
      3570526.48     10233122.93      3570326.86     10233160.90
      3570224.86     10233176.09      3570120.70     10233209.73
      3570037.11     10233255.32
#Sta/Elev= 30
  4749.4  310.68  4769.2  310.31  4774.3  310.55  4865.0  309.75  4930.9  309.62
  4967.5  308.87  4977.6  308.53  4984.1  308.01  4986.9  307.51  4990.1  308.01
  4992.2  308.83  5008.0  308.57  5054.6  308.54  5060.7  308.82  5087.5  308.76
  5092.7  309.08  5119.5  308.93  5124.8  309.22  5135.9  308.98  5151.5  308.67
  5156.8  308.98  5174.4  308.86  5180.1  309.06  5196.3  308.95  5202.0  309.19
  5218.1  309.20  5223.8  309.56  5239.9  309.52  5245.6  309.84  5260.4  309.72
#Mann=5,-1,0
  4749.4    0.16       0  4865.0    0.05       0  4984.1    0.03       0
  4990.1    0.05       0  5135.9     0.1       0
Bank Sta=4984.1,4990.1
Exp/Cntr=0.3,0.1

Type RM Length L Ch R = 1,548,371,371,371
BEGIN DESCRIPTION:
Mapping XS 44f93b86
END DESCRIPTION:
XS GIS Cut Line= 2
      3570737.59     10232860.06      3569696.49     10233116.00
#Sta/Elev= 30
  4644.6  308.76  4710.5  308.04  4757.2  308.19  4866.5  306.92  4971.3  306.63
  4979.8  306.24  4990.1  304.73  4997.4  300.14  5000.1  299.64  5003.4  300.14
  5006.4  302.09  5011.6  302.12  5022.2  304.23  5053.1  306.15  5136.2  306.06
  5172.6  305.46  5219.3  306.61  5268.1  307.03  5297.2  305.34  5338.7  305.87
  5350.5  305.35  5360.8  305.52  5380.3  307.42  5385.4  306.89  5421.8  306.98
  5522.3  308.97  5551.1  309.44  5587.3  310.05  5676.2  312.82  5716.7  313.30
#Mann=7,-1,0
  4644.6    0.05       0  4971.3    0.16       0  4997.4    0.07       0
  5003.4    0.16       0  5022.2    0.05       0  5522.3    0.16       0
  5551.1    0.05       0
Bank Sta=4997.4,5003.4
Exp/Cntr=0.3,0.1

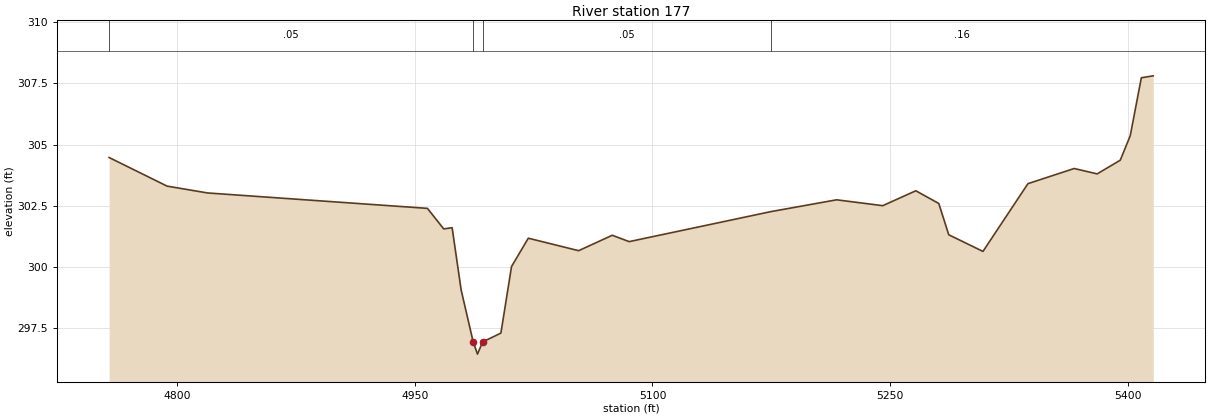
Type RM Length L Ch R = 1,177,0,0,0
BEGIN DESCRIPTION:
Mapping XS b0efa21f
END DESCRIPTION:
XS GIS Cut Line= 3
      3570651.58     10232514.38      3570299.10     10232639.39
      3570127.91     10232867.64
#Sta/Elev= 30
  4756.9  304.47  4793.5  303.30  4819.1  303.02  4957.9  302.39  4968.2  301.55
  4973.5  301.60  4979.2  299.05  4986.8  296.93  4989.5  296.43  4992.8  296.93
  5004.3  297.29  5011.0  300.01  5021.6  301.17  5053.4  300.66  5074.6  301.29
  5085.3  301.03  5175.0  302.26  5216.3  302.74  5245.4  302.50  5266.3  303.11
  5280.8  302.59  5287.1  301.31  5308.7  300.63  5337.1  303.40  5366.3  304.02
  5380.8  303.80  5395.4  304.36  5401.7  305.36  5408.7  307.73  5416.2  307.81
#Mann=4,-1,0
  4756.9    0.05       0  4986.8    0.03       0  4992.8    0.05       0
  5175.0    0.16       0
Bank Sta=4986.8,4992.8
Exp/Cntr=0.3,0.1

Chan Stop Cuts=-1