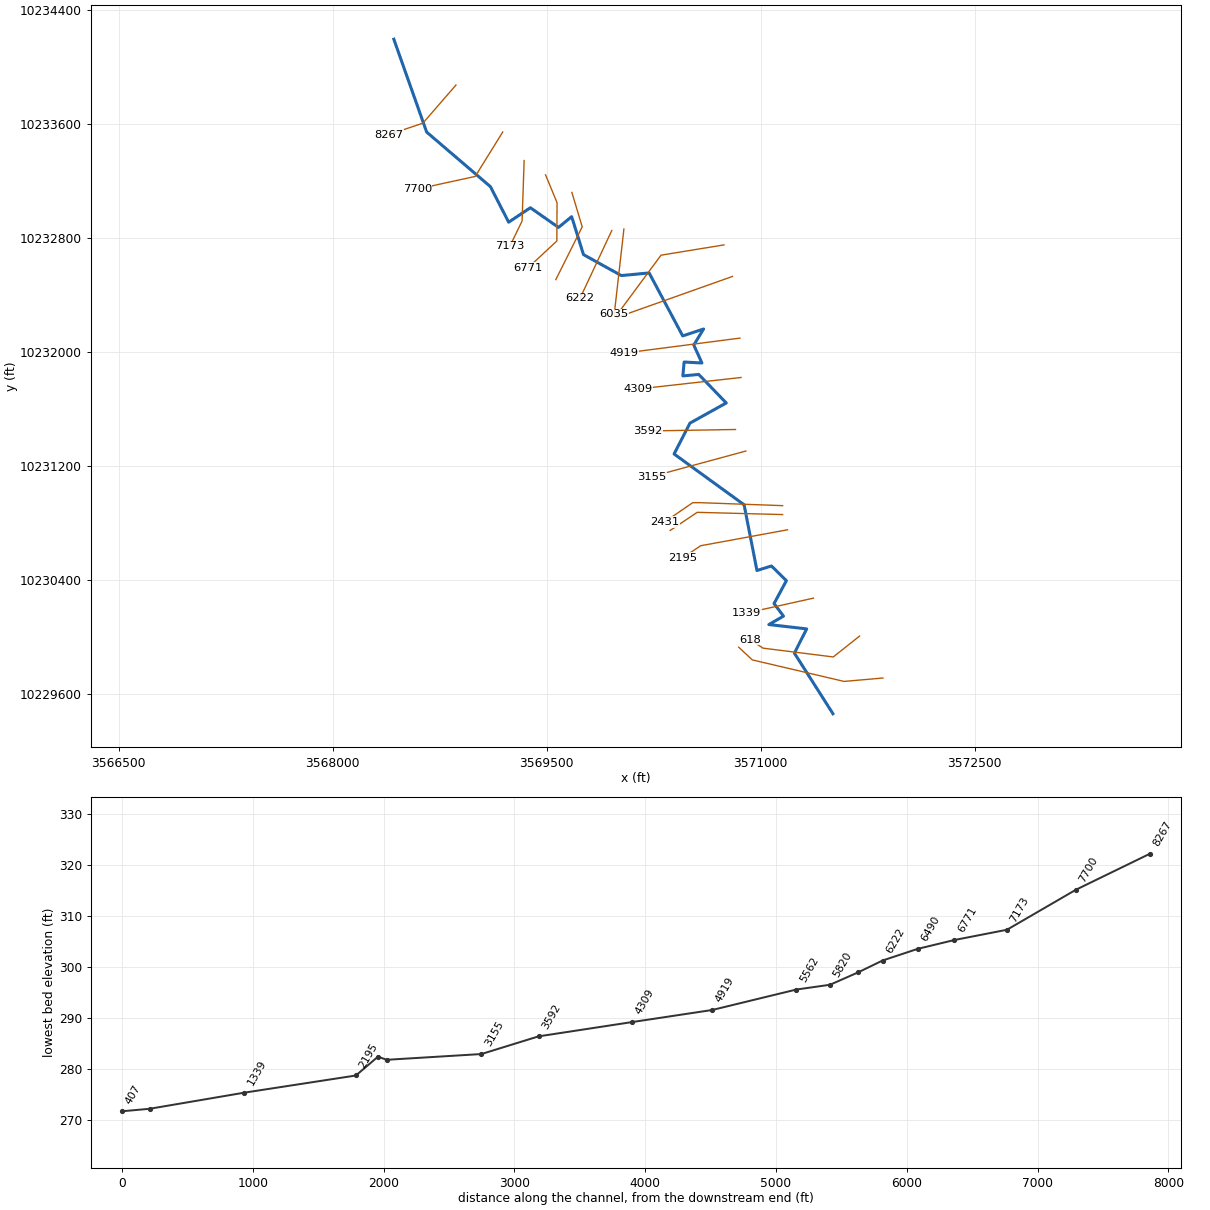
--- BRUSHYCREEKTRIB1.prj (project) ---

Proj Title=BRUSHY CREEK TRIB 15
Current Plan=p01
Default Exp/Contr=0.3,0.1
English Units
Geom File=g01
Flow File=f01
Plan File=p01
Y Axis Title=Elevation
X Axis Title(PF)=Main Channel Distance
X Axis Title(XS)=Station
BEGIN DESCRIPTION:
UNT05296 IN WICK
END DESCRIPTION:
DSS Export Rating Curves= 0
DSS Export Rating Curve Sorted= 0
DSS Export Volume Flow Curves= 0
DXF OffsetX= 0
DXF OffsetY= 0
DXF ScaleX= 1
DXF ScaleY= 10

--- BRUSHYCREEKTRIB1.p01 (plan) ---

Plan Title=Multiple Run
Short Identifier=Multiple
Geom File=g01
Flow File=f01
Subcritical Flow
K Sum by GR= 0
Std Step Tol= 0.01
Critical Tol= 0.01
Num of Std Step Trials= 20
Max Error Tol= 0.3
Flow Tol Ratio= 0.001
Split Flow NTrial= 30
Split Flow Tol= 0.02
Split Flow Ratio= 0.02
Log Output Level= 0
Friction Slope Method= 1
Unsteady Friction Slope Method= 2
Unsteady Bridges Friction Slope Method= 1
Parabolic Critical Depth
Global Vel Dist=  1 , 1 , 1
Global Log Level= 0
CheckData=True
Encroach Param= -1, 0, 0, 0
BEGIN DESCRIPTION:
Multiple Run
END DESCRIPTION:

--- BRUSHYCREEKTRIB1.f01 (steady flow) ---

Flow Title=Multiple
Program Version=4.10
Number of Profiles= 7
Profile Names=10-year,25-year,50-year,1pct_min,100-year,1pct_plu,500-year
River Rch & RM=BRUSHYCRTR15,Reach-1         ,8267
     119     144     163     136     183     248     232
River Rch & RM=BRUSHYCRTR15,Reach-1         ,5820
     281     362     425     367     496     671     675
River Rch & RM=BRUSHYCRTR15,Reach-1         ,5562
     281     362     425     367     496     671     675
Boundary for River Rch & Prof#=BRUSHYCRTR15,Reach-1         , 1
Up Type= 0
Dn Type= 3
Dn Slope=0.005
Boundary for River Rch & Prof#=BRUSHYCRTR15,Reach-1         , 2
Up Type= 0
Dn Type= 3
Dn Slope=0.005
Boundary for River Rch & Prof#=BRUSHYCRTR15,Reach-1         , 3
Up Type= 0
Dn Type= 3
Dn Slope=0.005
Boundary for River Rch & Prof#=BRUSHYCRTR15,Reach-1         , 4
Up Type= 0
Dn Type= 3
Dn Slope=0.005
Boundary for River Rch & Prof#=BRUSHYCRTR15,Reach-1         , 5
Up Type= 0
Dn Type= 3
Dn Slope=0.005
Boundary for River Rch & Prof#=BRUSHYCRTR15,Reach-1         , 6
Up Type= 0
Dn Type= 3
Dn Slope=0.005
Boundary for River Rch & Prof#=BRUSHYCRTR15,Reach-1         , 7
Up Type= 0
Dn Type= 3
Dn Slope=0.005
DSS Import GetInterval= 0
DSS Import GetPeak= 0
DSS Import FillOption= 0

--- BRUSHYCREEKTRIB1.g01 (geometry) ---

Geom Title=Existing Conditions
Program Version=4.10

River Reach=BRUSHYCRTR15    ,Reach-1
Reach XY= 30
      3568428.59     10234192.29      3568658.83     10233541.23
      3569105.79      10233158.6      3569233.75     10232909.67
      3569385.87     10233011.01      3569582.92     10232872.99
      3569675.25     10232948.29      3569758.24     10232682.39
       3570023.4     10232535.49      3570218.48     10232553.81
      3570453.54     10232112.33      3570600.33     10232161.12
      3570531.41     10232048.61      3570588.57      10231922.4
      3570463.58     10231929.44       3570454.8     10231832.12
      3570566.12     10231842.23      3570758.99     10231642.43
      3570504.82     10231501.29      3570393.21      10231284.8
      3570884.01     10230928.72      3570974.22     10230467.95
      3571075.85     10230499.62      3571180.63     10230396.64
      3571094.16     10230236.07      3571160.24     10230147.91
       3571057.7     10230088.98       3571322.7     10230058.55
      3571236.75     10229888.56      3571506.75       10229464.

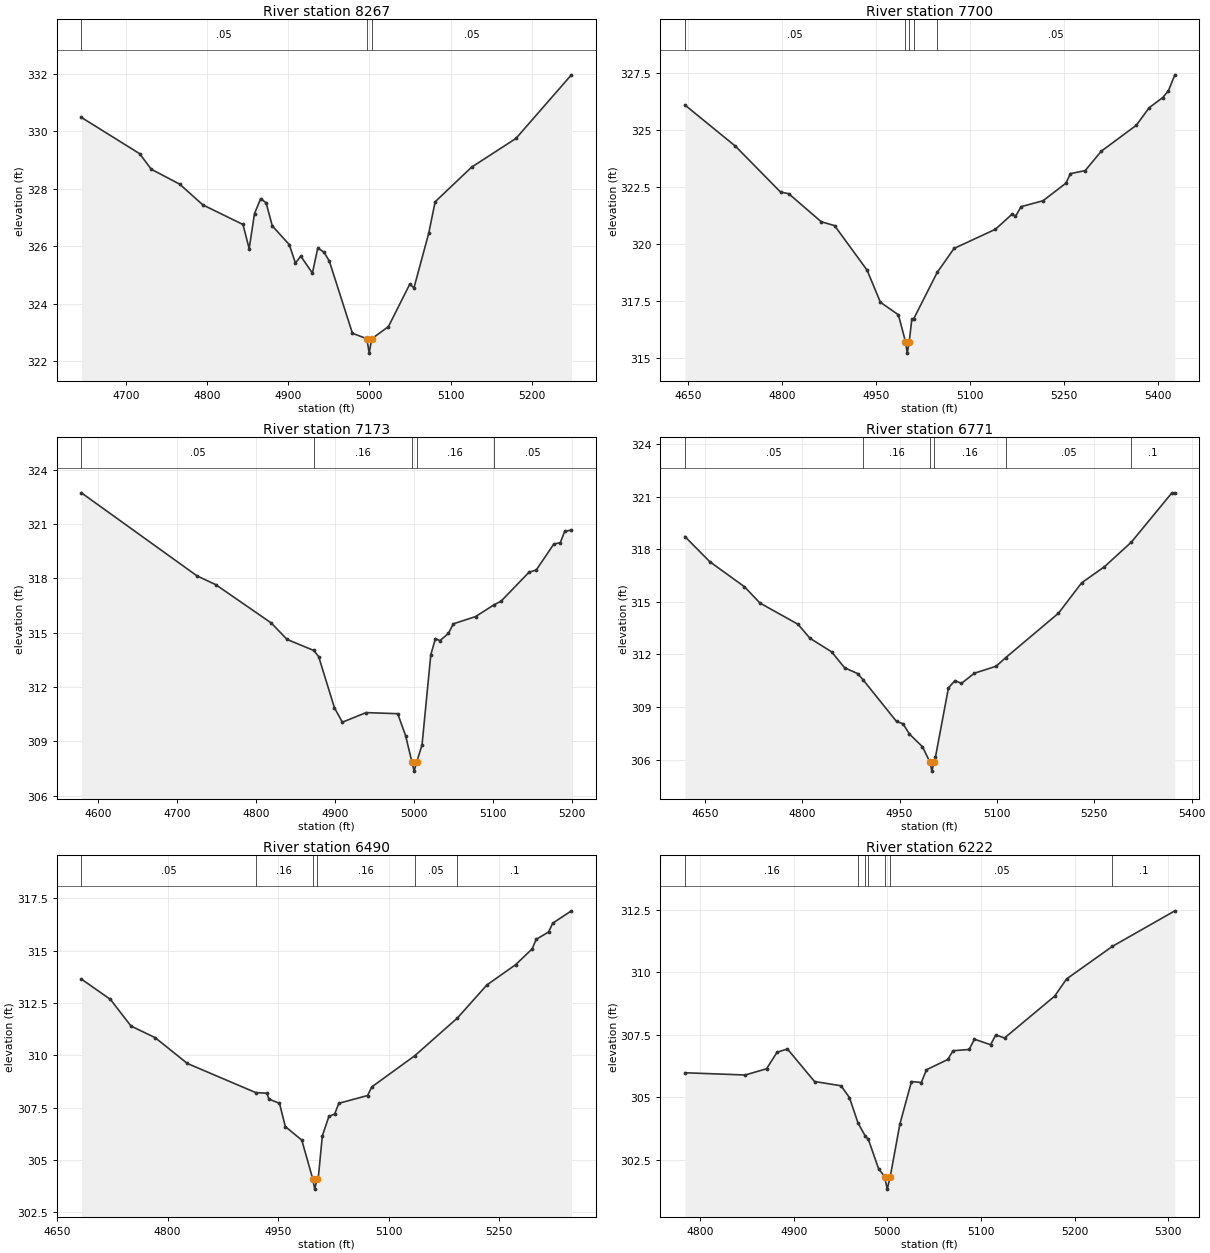
Type RM Length L Ch R = 1 ,8267    ,567,567,567
BEGIN DESCRIPTION:
UNT05297 IN WICK 5.0
END DESCRIPTION:
XS GIS Cut Line= 3
      3568864.12     10233870.83      3568632.35      10233603.9
      3568395.58     10233523.68
#Sta/Elev= 30
  4645.4  330.48  4717.1  329.22  4731.4  328.68  4766.5  328.16    4795  327.44
  4844.4  326.76    4852  325.92  4858.6  327.14  4866.2  327.66  4872.9  327.51
  4880.5  326.71  4901.4  326.06    4909  325.42  4915.6  325.66  4929.9  325.07
  4936.5  325.94  4944.1   325.8  4950.7  325.49  4979.2  322.98    4997  322.79
  4999.8  322.29    5003  322.79  5023.5  323.21  5049.7  324.68    5055  324.56
  5073.1  326.45  5081.1  327.55  5125.9  328.75  5180.6  329.75  5248.9  331.96
#Mann= 3 ,-1 , 0
  4645.4     .05       0    4997     .03       0    5003     .05       0
Bank Sta=4997,5003
XS Rating Curve= 0 ,0
Exp/Cntr=0.3,0.1

Type RM Length L Ch R = 1 ,7700    ,527,527,527
BEGIN DESCRIPTION:
UNT05297 IN WICK 4.0
END DESCRIPTION:
XS GIS Cut Line= 3
      3569192.09     10233541.61      3568998.99     10233230.33
      3568592.06     10233141.63
#Sta/Elev= 30
  4644.5  326.09  4725.4  324.28  4797.4  322.27  4810.4   322.2  4862.4  320.97
  4883.7   320.8  4935.6  318.85  4956.9  317.44  4985.7  316.89    4997  315.71
  4999.8  315.21    5003  315.71  5007.1   316.7  5009.8   316.7  5047.7  318.75
  5074.6   319.8  5140.7  320.64  5167.6  321.31  5172.7   321.2  5181.6  321.63
  5216.7  321.89  5253.3  322.66  5260.6  323.08    5284  323.21  5309.7  324.06
  5365.8   325.2  5386.3  325.97  5407.8  326.41    5417  326.71  5427.3  327.41
#Mann= 5 ,-1 , 0
  4644.5     .05       0    4997     .03       0    5003     .05       0
  5009.8     .16       0  5047.7     .05       0
Bank Sta=4997,5003
XS Rating Curve= 0 ,0
Exp/Cntr=0.3,0.1

Type RM Length L Ch R = 1 ,7173    ,402,402,402
BEGIN DESCRIPTION:
UNT05297 IN WICK 3.0
END DESCRIPTION:
XS GIS Cut Line= 3
      3569342.11     10233341.65      3569327.77     10232917.83
      3569242.09     10232741.62
#Sta/Elev= 30
  4578.8  322.72  4725.3  318.13  4748.9  317.65  4818.9  315.54    4839  314.63
  4872.8  314.02    4879  313.68    4899  310.85    4909  310.06    4939  310.59
    4979  310.53    4989  309.32    4997  307.86  4999.8  307.36    5003  307.86
  5009.8  308.81  5020.9  313.79  5026.8  314.68  5032.4  314.56  5043.1  314.96
  5049.4  315.49  5077.5  315.89  5100.9  316.54  5109.8  316.74  5145.2  318.34
  5154.3  318.46  5176.5  319.89  5184.7  319.97  5190.3  320.59  5198.8  320.67
#Mann= 5 ,-1 , 0
  4578.8     .05       0  4872.8     .16       0    4997     .07       0
    5003     .16       0  5100.9     .05       0
Bank Sta=4997,5003
XS Rating Curve= 0 ,0
Exp/Cntr=0.3,0.1

Type RM Length L Ch R = 1 ,6771    ,281,281,281
BEGIN DESCRIPTION:
UNT05297 IN WICK 2.0
END DESCRIPTION:
XS GIS Cut Line= 4
       3569492.1     10233241.66      3569572.78     10233046.77
      3569571.64     10232777.99      3569370.23     10232590.47
#Sta/Elev= 30
  4619.2  318.72  4657.8  317.28    4711  315.86  4734.9  314.93  4793.5  313.72
    4812  312.92  4845.3  312.15  4865.3  311.24  4885.3  310.91  4893.5  310.57
  4945.3  308.18  4955.3  308.05  4965.3  307.46  4985.3  306.74    4997  305.85
  4999.8  305.35    5003  305.85  5005.3  306.15  5025.3  310.09  5035.3  310.51
  5045.3  310.35  5065.3  310.93  5098.9  311.33  5113.3  311.81  5194.8  314.35
  5230.5  316.08  5265.7     317  5307.1   318.4  5369.6  321.21  5374.1  321.21
#Mann= 6 ,-1 , 0
  4619.2     .05       0  4893.5     .16       0    4997     .07       0
    5003     .16       0  5113.3     .05       0  5307.1      .1       0
Bank Sta=4997,5003
XS Rating Curve= 0 ,0
Exp/Cntr=0.3,0.1

Type RM Length L Ch R = 1 ,6490    ,268,268,268
BEGIN DESCRIPTION:
Mapping XS 0e49a168
END DESCRIPTION:
XS GIS Cut Line= 3
      3569676.93     10233118.24      3569749.31     10232876.84
       3569564.1     10232507.15
#Sta/Elev= 30
  4682.9  313.64  4722.3  312.67  4750.2   311.4  4783.2  310.84  4826.8  309.61
  4919.7  308.22  4934.9  308.19  4937.5  307.91  4951.9  307.71  4959.8   306.6
  4982.2  305.95    4997  304.11  4999.8  303.61    5003  304.11  5004.5  304.11
  5010.1  306.15    5019  307.08  5026.9   307.2  5032.5  307.71  5071.6  308.08
  5077.2  308.49  5135.3  309.97  5193.5  311.78  5233.6  313.36  5272.7  314.33
    5295  315.08  5300.6  315.54  5317.4  315.89    5323  316.31  5348.4   316.9
#Mann= 6 ,-1 , 0
  4682.9     .05       0  4919.7     .16       0    4997     .07       0
    5003     .16       0  5135.3     .05       0  5193.5      .1       0
Bank Sta=4997,5003
XS Rating Curve= 0 ,0
Exp/Cntr=0.3,0.1

Type RM Length L Ch R = 1 ,6222    ,187,187,187
BEGIN DESCRIPTION:
Mapping XS d1fd7e82
END DESCRIPTION:
XS GIS Cut Line= 2
      3569956.43     10232850.83      3569734.23     10232376.94
#Sta/Elev= 30
  4783.6  305.98  4848.1  305.89  4870.9  306.14  4882.1   306.8  4893.2  306.93
  4922.1  305.63  4950.4  305.46  4959.4  304.99  4968.6  303.97  4976.5  303.44
  4979.6  303.32  4990.5  302.15    4997  301.83  4999.8  301.33    5003  301.83
  5013.3  303.93  5025.7  305.63  5036.2  305.59  5041.7   306.1  5064.5  306.51
    5070  306.86  5087.3  306.91  5092.9  307.32  5110.2   307.1  5115.7  307.49
  5125.1  307.37  5178.6  309.04  5191.4  309.73  5240.3  311.03    5307  312.45
#Mann= 7 ,-1 , 0
  4783.6     .16       0  4968.6     .05       0  4976.5     .16       0
  4979.6     .05       0    4997     .03       0    5003     .05       0
  5240.3      .1       0
Bank Sta=4997,5003
XS Rating Curve= 0 ,0
Exp/Cntr=0.3,0.1

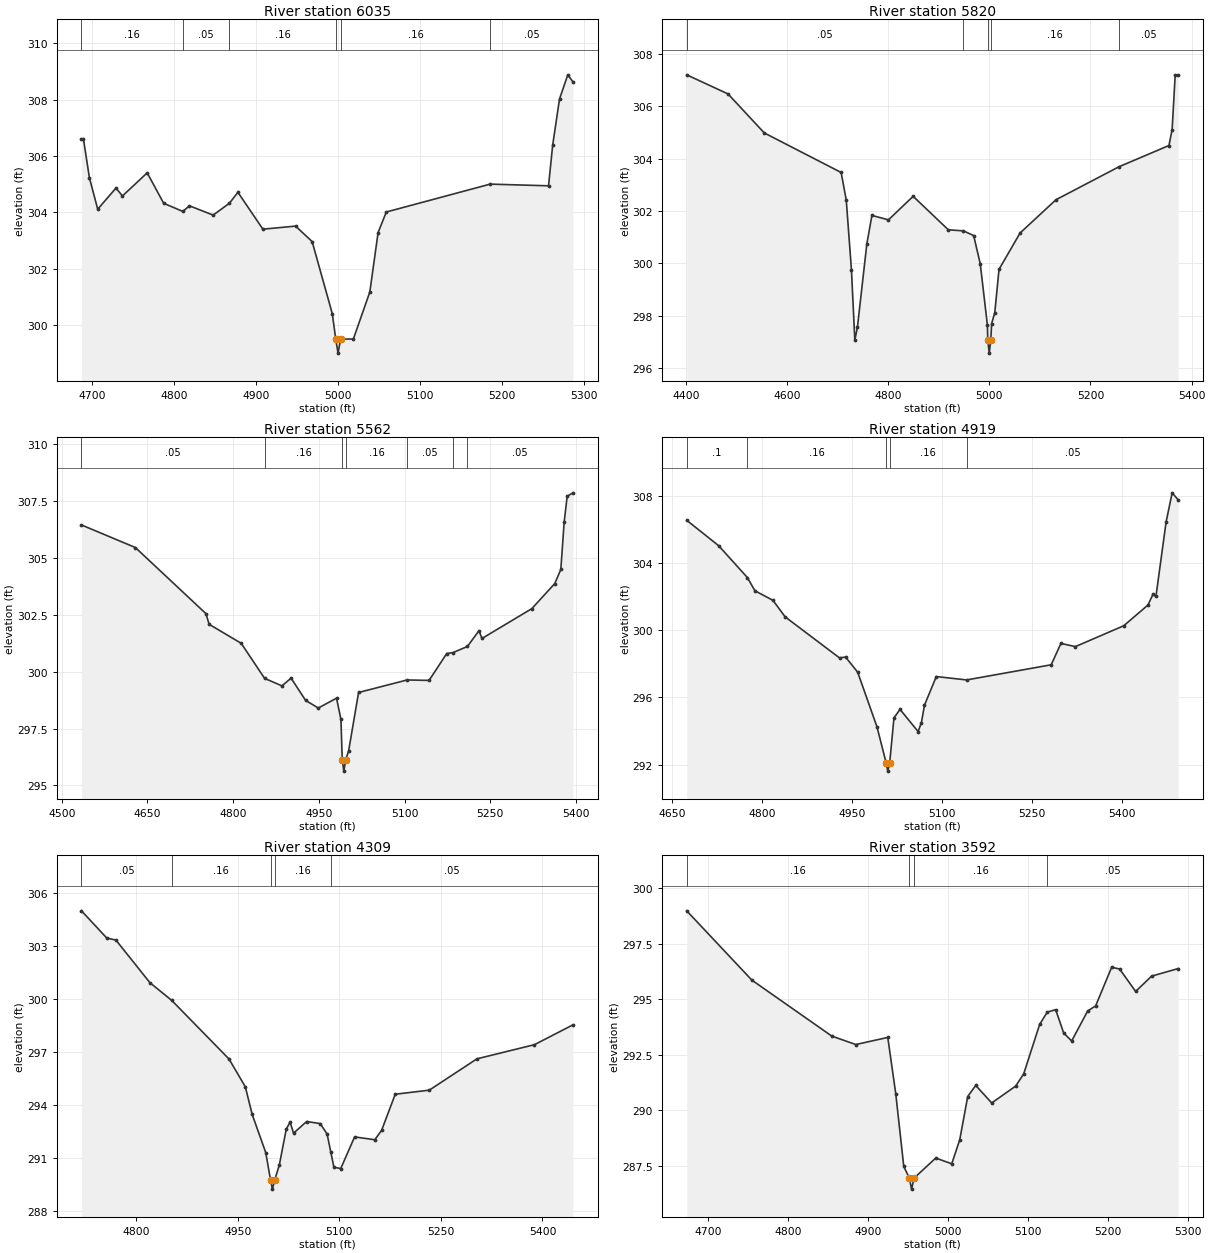
Type RM Length L Ch R = 1 ,6035    ,215,215,215
BEGIN DESCRIPTION:
Mapping XS 2a9ac74a
END DESCRIPTION:
XS GIS Cut Line= 2
      3570041.52     10232861.32      3569973.95     10232265.34
#Sta/Elev= 30
  4686.7   306.6  4689.1   306.6  4696.4  305.22  4706.5  304.11  4728.8  304.86
  4736.7  304.58  4766.9   305.4    4787  304.32  4810.4  304.03  4818.4  304.23
  4847.4   303.9  4867.2  304.32  4877.6  304.71  4908.1   303.4    4948  303.51
  4968.2  302.96  4992.8   300.4    4997   299.5  4999.8     299    5003   299.5
  5018.5   299.5  5038.6  301.17  5048.7  303.28  5058.7  304.01  5185.5     305
  5256.7  304.94  5261.8  306.39  5270.1  308.02  5280.2  308.88  5286.5  308.63
#Mann= 6 ,-1 , 0
  4686.7     .16       0  4810.4     .05       0  4867.2     .16       0
    4997     .07       0    5003     .16       0  5185.5     .05       0
Bank Sta=4997,5003
XS Rating Curve= 0 ,0
Exp/Cntr=0.3,0.1

Type RM Length L Ch R = 1 ,5820    ,258,258,258
BEGIN DESCRIPTION:
UNT05297 IN WICK 1.0
END DESCRIPTION:
XS GIS Cut Line= 3
      3570743.52      10232750.5      3570301.67     10232678.34
       3569990.1     10232257.04
#Sta/Elev= 30
  4401.7   307.2  4483.4  306.47  4555.1  304.98  4707.1  303.47  4717.2  302.41
  4727.4  299.76  4734.1  297.07  4739.2  297.55  4757.8  300.73  4767.9  301.83
  4800.6  301.66  4849.4  302.56    4919  301.28  4948.7  301.24  4969.1  301.06
  4982.1  299.98  4996.2  297.65    4997  297.07  4999.8  296.57    5003  297.07
  5004.6   297.7  5010.8  298.11  5019.2  299.77  5060.9  301.16  5131.9  302.43
  5256.5  303.69  5355.2   304.5  5361.5  305.11  5367.5  307.18  5373.4  307.18
#Mann= 5 ,-1 , 0
  4401.7     .05       0  4948.7     .16       0    4997     .07       0
    5003     .16       0  5256.5     .05       0
Bank Sta=4997,5003
XS Rating Curve= 0 ,0
Exp/Cntr=0.3,0.1

Type RM Length L Ch R = 1 ,5562    ,643,643,643
BEGIN DESCRIPTION:
UNT05296 IN WICK 8.0
END DESCRIPTION:
XS GIS Cut Line= 2
      3570802.76     10232529.34       3569992.1     10232241.64
#Sta/Elev= 30
  4534.6  306.43  4628.9  305.44  4752.4  302.54  4758.1  302.07  4814.1  301.24
  4855.1   299.7  4885.5  299.37  4901.4  299.71    4927  298.73  4949.1   298.4
    4981  298.83  4988.7   297.9    4991  296.13  4993.8  295.63    4997  296.13
  5002.2  296.52  5019.6  299.08  5104.6  299.63    5143  299.61  5173.9  300.79
  5184.8  300.83  5210.1   301.1  5230.3  301.79  5235.6  301.45  5322.9  302.76
    5363  303.86  5373.6  304.48  5379.4  306.55  5384.7  307.69  5394.8  307.84
#Mann= 7 ,-1 , 0
  4534.6     .05       0  4855.1     .16       0    4991     .07       0
    4997     .16       0  5104.6     .05       0  5184.8     .16       0
  5210.1     .05       0
Bank Sta=4991,4997
XS Rating Curve= 0 ,0
Exp/Cntr=0.3,0.1

Type RM Length L Ch R = 1 ,4919    ,610,610,610
BEGIN DESCRIPTION:
UNT05296 IN WICK 7.0
END DESCRIPTION:
XS GIS Cut Line= 2
      3570854.84     10232097.04      3570042.14     10231991.65
#Sta/Elev= 30
  4674.4  306.53  4727.6  305.02  4775.7  303.12  4788.1  302.34  4818.3  301.77
  4838.5  300.79  4929.2  298.35  4939.3   298.4  4959.5   297.5  4991.7  294.25
  5006.9  292.12  5009.7  291.62  5012.9  292.12    5020  294.78  5030.1  295.29
  5060.3  293.97  5065.8  294.51  5070.9  295.54  5090.6  297.24  5141.2  297.04
  5282.2  297.94  5298.4  299.21  5322.5  299.02  5403.2  300.26  5443.5  301.49
  5451.8  302.12  5456.9  302.01  5473.8  306.43  5483.9  308.16  5493.9  307.74
#Mann= 5 ,-1 , 0
  4674.4      .1       0  4775.7     .16       0  5006.9     .07       0
  5012.9     .16       0  5141.2     .05       0
Bank Sta=5006.9,5012.9
XS Rating Curve= 0 ,0
Exp/Cntr=0.3,0.1

Type RM Length L Ch R = 1 ,4309    ,717,717,717
BEGIN DESCRIPTION:
UNT05296 IN WICK 6.0
END DESCRIPTION:
XS GIS Cut Line= 2
      3570862.61     10231820.99      3570141.22     10231740.26
#Sta/Elev= 30
  4719.1  304.98  4756.5  303.44  4769.9  303.33  4820.2  300.92  4852.4  299.92
    4937  296.61  4961.1  295.04  4971.2  293.48  4991.3  291.32  4998.4  289.76
  5001.1  289.26  5004.4  289.76  5011.4  290.64  5021.5  292.64  5027.2  293.05
  5032.3  292.42  5051.7  293.08  5071.8  292.96  5081.9  292.37  5087.4  291.34
  5091.9   290.5    5102  290.42  5122.5  292.21  5152.3  292.05  5162.4  292.58
  5182.5  294.62  5232.8  294.85  5303.2  296.62  5388.2  297.42    5445  298.54
#Mann= 5 ,-1 , 0
  4719.1     .05       0  4852.4     .16       0  4998.4     .07       0
  5004.4     .16       0  5087.4     .05       0
Bank Sta=4998.4,5004.4
XS Rating Curve= 0 ,0
Exp/Cntr=0.3,0.1

Type RM Length L Ch R = 1 ,3592    ,437,437,437
BEGIN DESCRIPTION:
UNT05296 IN WICK 5.0
END DESCRIPTION:
XS GIS Cut Line= 2
      3570823.56     10231456.41      3570208.94     10231445.99
#Sta/Elev= 30
  4673.4  298.98  4754.9  295.86  4854.9  293.34  4884.9  292.96  4924.9  293.28
  4934.9  290.74  4944.9  287.47  4951.9  286.95  4954.6  286.45  4957.9  286.95
  4984.9  287.85  5004.9  287.59  5014.9  288.67  5024.9  290.62  5034.9  291.12
  5054.9  290.33  5084.9  291.09  5094.9  291.64  5114.9  293.87  5124.4  294.42
  5134.9  294.53  5144.9  293.48  5154.9  293.12  5174.9  294.47  5184.9   294.7
  5204.9  296.44  5214.9  296.36  5234.9  295.35  5254.9  296.04  5288.1  296.38
#Mann= 4 ,-1 , 0
  4673.4     .16       0  4951.9     .07       0  4957.9     .16       0
  5124.4     .05       0
Bank Sta=4951.9,4957.9
XS Rating Curve= 0 ,0
Exp/Cntr=0.3,0.1

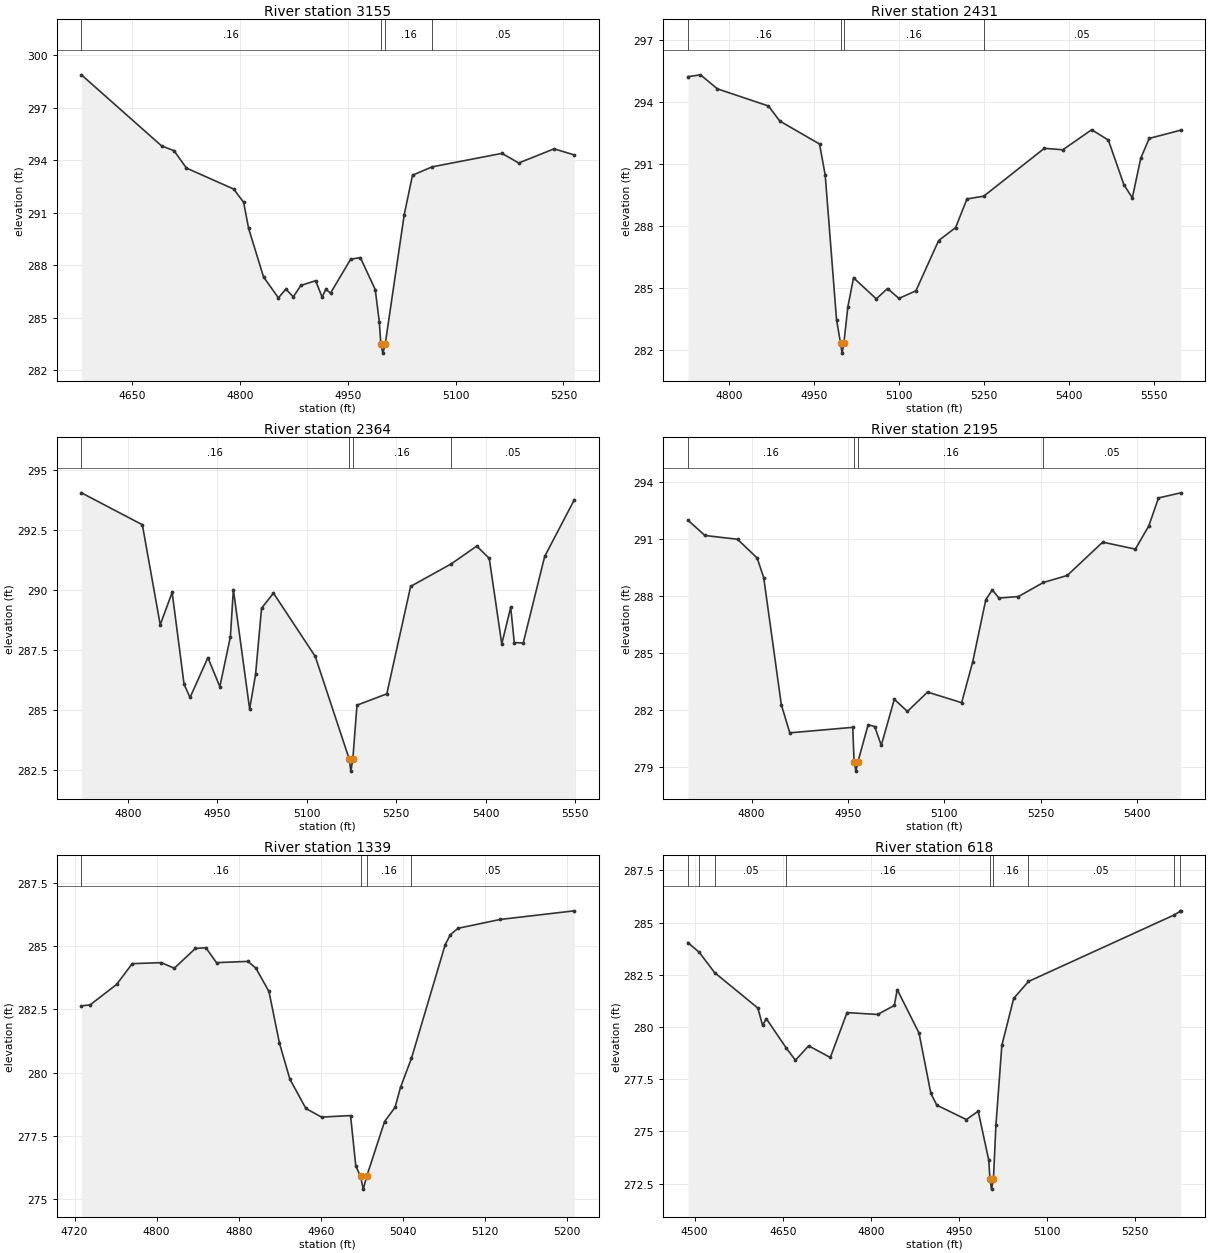
Type RM Length L Ch R = 1 ,3155    ,724,724,724
BEGIN DESCRIPTION:
UNT05296 IN WICK 4.0
END DESCRIPTION:
XS GIS Cut Line= 2
      3570896.43     10231305.36        3570235.     10231125.68
#Sta/Elev= 30
  4579.7  298.89  4691.1  294.83  4708.5  294.55  4725.7  293.56  4791.4  292.36
  4805.3   291.6  4812.2  290.11  4832.9  287.34  4853.6  286.14    4864  286.64
  4874.3   286.2  4884.9  286.85  4905.4  287.12  4914.4  286.18  4919.5  286.63
  4926.1  286.41  4954.1  288.35  4967.6  288.44  4988.3  286.61  4993.9  284.77
  4996.1  283.48  4998.9  282.98  5002.1  283.48  5028.6   290.9  5040.1  293.15
  5067.4  293.63  5164.5   294.4  5187.8  293.85    5237  294.66  5265.1  294.31
#Mann= 4 ,-1 , 0
  4579.7     .16       0  4996.1     .07       0  5002.1     .16       0
  5067.4     .05       0
Bank Sta=4996.1,5002.1
XS Rating Curve= 0 ,0
Exp/Cntr=0.3,0.1

Type RM Length L Ch R = 1 ,2431    ,67,67,67
BEGIN DESCRIPTION:
Mapping XS 02f4cd8e
END DESCRIPTION:
XS GIS Cut Line= 4
      3571154.24     10230922.56      3570576.16     10230943.39
      3570524.07     10230943.39      3570326.61     10230808.28
#Sta/Elev= 30
  4726.9  295.24  4749.1  295.33  4779.1  294.65  4869.1  293.82  4889.1  293.09
  4959.2  291.98  4969.2  290.48  4989.2  283.47  4996.2  282.35    4999  281.85
  5002.2  282.35  5009.2  284.09  5019.2   285.5  5059.3  284.48  5079.3  284.98
  5099.3   284.5  5129.3  284.87  5169.3   287.3  5199.3  287.93  5219.4  289.32
  5248.9  289.45  5355.9  291.77  5388.6   291.7  5439.4  292.67  5468.9  292.17
  5496.3  290.01  5511.2  289.37  5526.1  291.29    5541  292.25  5596.7  292.65
#Mann= 4 ,-1 , 0
  4726.9     .16       0  4996.2     .07       0  5002.2     .16       0
  5248.9     .05       0
Bank Sta=4996.2,5002.2
XS Rating Curve= 0 ,0
Exp/Cntr=0.3,0.1

Type RM Length L Ch R = 1 ,2364    ,169,169,169
BEGIN DESCRIPTION:
Mapping XS b6c77e24
END DESCRIPTION:
XS GIS Cut Line= 3
      3571154.24     10230860.06      3570555.32     10230875.68
      3570366.19     10230748.73
#Sta/Elev= 30
    4722  294.06  4824.2  292.73  4854.2  288.56  4874.2  289.91  4894.2  286.08
  4904.2  285.53  4934.2  287.19  4954.2  285.98  4971.9  288.06  4976.9  290.03
  5004.2  285.05  5014.2   286.5  5024.2  289.25  5044.2  289.88  5114.3  287.24
  5171.3  282.96    5174  282.46  5177.3  282.96  5184.3  285.21  5234.3  285.68
  5274.3  290.16  5342.5   291.1  5385.2  291.84  5406.2  291.33  5427.2  287.76
  5442.2  289.29  5448.2  287.82  5463.2   287.8  5499.2  291.41  5548.9  293.77
#Mann= 4 ,-1 , 0
    4722     .16       0  5171.3     .07       0  5177.3     .16       0
  5342.5     .05       0
Bank Sta=5171.3,5177.3
XS Rating Curve= 0 ,0
Exp/Cntr=0.3,0.1

Type RM Length L Ch R = 1 ,2195    ,856,856,856
BEGIN DESCRIPTION:
UNT05296 IN WICK 3.0
END DESCRIPTION:
XS GIS Cut Line= 3
      3571188.13     10230753.28      3570578.76      10230641.3
      3570456.73     10230558.22
#Sta/Elev= 30
    4701  292.01  4727.5   291.2  4778.3     291  4808.8  290.01    4819  288.98
  4846.4  282.28  4859.6  280.79  4957.6  281.08  4959.7  279.27  4962.5  278.77
  4965.7  279.27  4981.6  281.22  4991.8  281.12    5002  280.13  5022.3  282.56
  5042.7  281.92    5074  282.94  5127.1  282.38  5144.3  284.53  5164.7  287.81
  5174.8  288.33  5185.2   287.9  5215.5  287.98  5254.3  288.72  5291.4  289.09
  5346.7  290.85  5397.5  290.48  5418.5  291.71  5433.5  293.18  5468.2  293.45
#Mann= 4 ,-1 , 0
    4701     .16       0  4959.7     .07       0  4965.7     .16       0
  5254.3     .05       0
Bank Sta=4959.7,4965.7
XS Rating Curve= 0 ,0
Exp/Cntr=0.3,0.1

Type RM Length L Ch R = 1 ,1339    ,721,721,721
BEGIN DESCRIPTION:
UNT05296 IN WICK 2.0
END DESCRIPTION:
XS GIS Cut Line= 2
      3571370.41     10230274.11      3570901.65     10230169.94
#Sta/Elev= 30
  4726.7  282.64  4735.2  282.68    4761  283.49  4776.2  284.31  4804.5  284.35
  4817.2  284.13  4837.7  284.91  4847.9  284.94  4858.3  284.35  4888.9   284.4
  4896.7  284.13  4909.4  283.21  4919.6  281.17  4929.8  279.74  4945.4  278.58
  4960.6  278.24  4988.9   278.3    4994  276.31  4998.6  275.89  5001.3  275.39
  5004.6  275.89    5022  278.06  5032.3  278.63  5037.6  279.42  5048.2  280.56
  5081.1  285.06  5086.2  285.46  5093.7  285.71  5134.9  286.06  5206.9   286.4
#Mann= 4 ,-1 , 0
  4726.7     .16       0  4998.6     .07       0  5004.6     .16       0
  5048.2     .05       0
Bank Sta=4998.6,5004.6
XS Rating Curve= 0 ,0
Exp/Cntr=0.3,0.1

Type RM Length L Ch R = 1 ,618     ,211,211,211
BEGIN DESCRIPTION:
Mapping XS a6860a07
END DESCRIPTION:
XS GIS Cut Line= 4
      3571693.52     10230008.26      3571509.08     10229861.79
      3571016.46     10229923.64      3570926.77     10229983.07
#Sta/Elev= 30
  4488.5  284.04    4508  283.57  4534.1   282.6  4607.6  280.91  4615.7  280.08
  4622.1   280.4  4656.4  278.98  4671.7  278.41  4694.2   279.1  4731.1  278.54
  4759.6  280.69  4811.7   280.6  4840.1  281.03  4845.1  281.79  4882.2  279.71
  4902.4  276.82  4912.5  276.26  4962.9  275.57    4983  275.97    5001  273.63
    5003  272.74  5005.7  272.24    5009  272.74  5013.2   275.3  5023.3  279.12
  5043.5  281.37  5068.7  282.18  5316.7  285.36  5327.4  285.54  5328.1  285.56
#Mann= 9 ,-1 , 0
  4488.5     .05       0    4508     .16       0  4534.1     .05       0
  4656.4     .16       0    5003     .07       0    5009     .16       0
  5068.7     .05       0  5316.7     .16       0  5327.4     .05       0
Bank Sta=5003,5009
XS Rating Curve= 0 ,0
Exp/Cntr=0.3,0.1

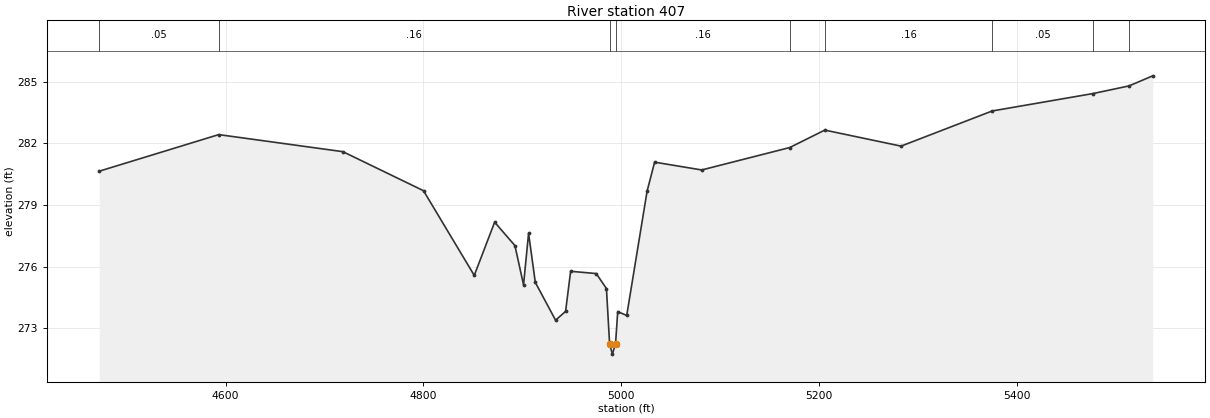
Type RM Length L Ch R = 1 ,407     ,0,0,0
BEGIN DESCRIPTION:
UNT05296 IN WICK 1.0
END DESCRIPTION:
XS GIS Cut Line= 4
      3571857.42     10229714.23      3571585.03     10229690.35
      3570941.59     10229841.18      3570846.09     10229930.24
#Sta/Elev= 30
  4472.3  280.65  4593.1  282.43  4718.6   281.6  4800.1   279.7  4851.4  275.58
    4872  278.17  4892.5  277.03  4901.2  275.12  4906.3  277.63  4913.1  275.24
  4933.6   273.4  4943.7  273.83  4948.8  275.78  4974.7  275.67    4985  274.94
  4988.2  272.25    4991  271.75  4994.2  272.25  4996.4  273.82  5005.5  273.63
  5026.1  279.68  5033.7  281.09  5081.3  280.71  5170.2   281.8  5205.7  282.65
  5282.8  281.87  5374.9  283.58  5477.1  284.43  5513.3   284.8  5537.2  285.29
#Mann= 9 ,-1 , 0
  4472.3     .05       0  4593.1     .16       0  4988.2     .07       0
  4994.2     .16       0  5170.2     .05       0  5205.7     .16       0
  5374.9     .05       0  5477.1     .16       0  5513.3     .05       0
Bank Sta=4988.2,4994.2
XS Rating Curve= 0 ,0
Exp/Cntr=0.3,0.1

Chan Stop Cuts=-1
Use User Specified Reach Order=0
Composite Channel Slope=5