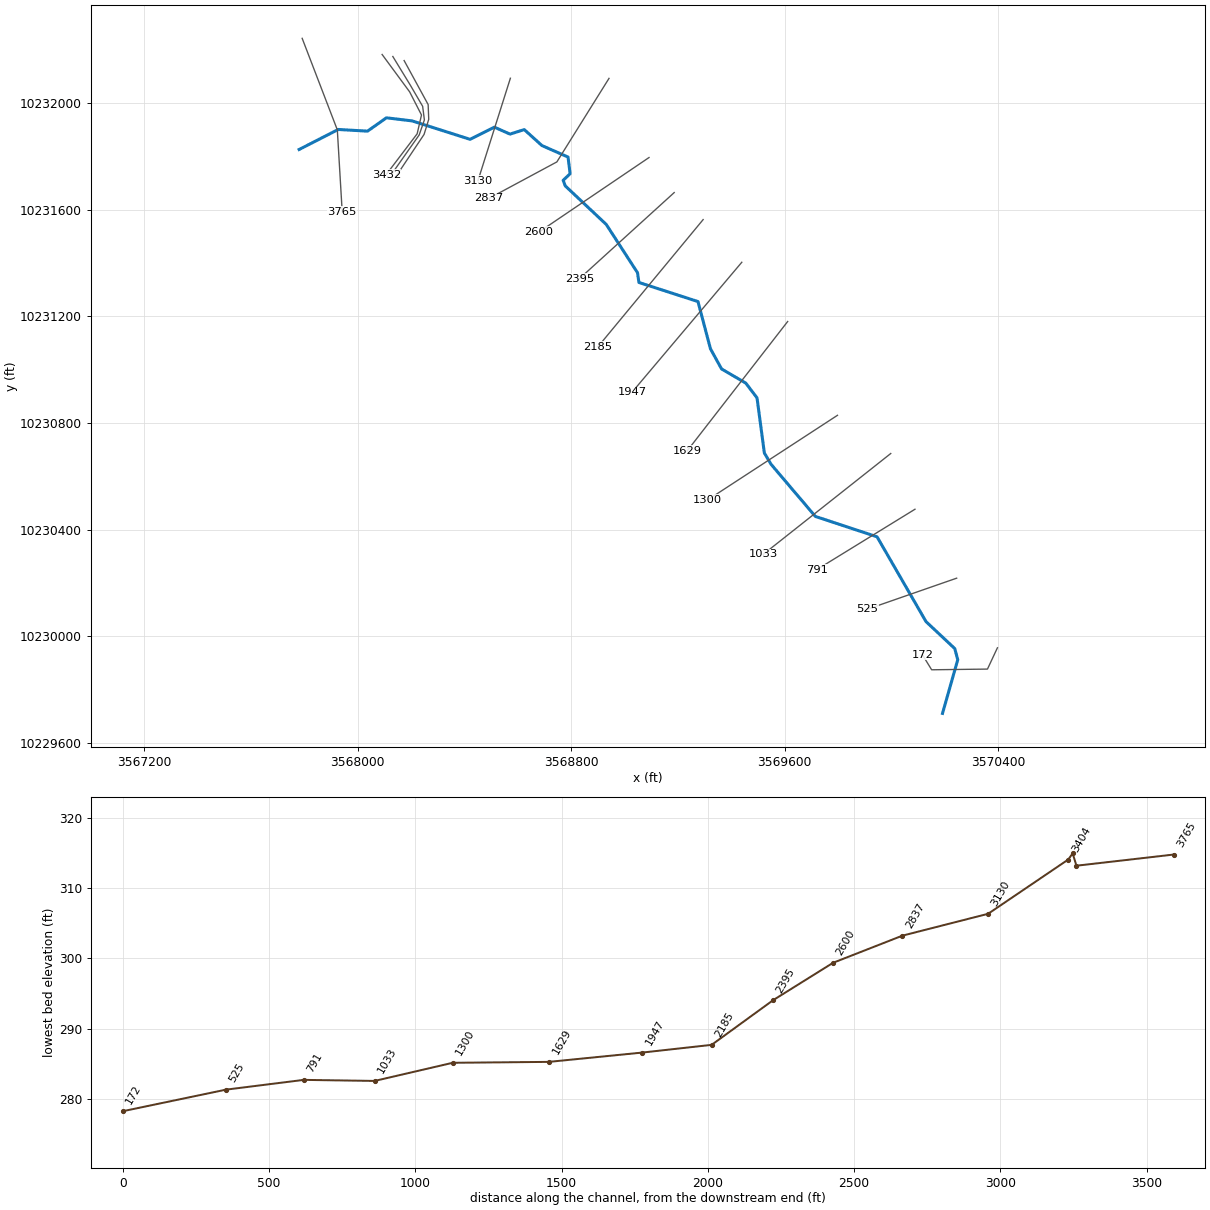
--- BRUSHYCREEKTRIB1.prj (project) ---

Proj Title=BRUSHY CREEK TRIB 16
Current Plan=p01
Default Exp/Contr=0.3,0.1
English Units
Geom File=g01
Flow File=f01
Plan File=p01
Y Axis Title=Elevation
X Axis Title(PF)=Main Channel Distance
X Axis Title(XS)=Station
BEGIN DESCRIPTION:
UNT05295 IN WICK
END DESCRIPTION:
DSS Export Rating Curves= 0
DSS Export Rating Curve Sorted= 0
DSS Export Volume Flow Curves= 0
DXF Filename=UNT05295 IN WICK.
DXF OffsetX= 0
DXF OffsetY= 0
DXF ScaleX= 1
DXF ScaleY= 10

--- BRUSHYCREEKTRIB1.p01 (plan) ---

Plan Title=Multiple Run
Short Identifier=Multiple
Geom File=g01
Flow File=f01
Subcritical Flow
K Sum by GR= 0
Std Step Tol= 0.01
Critical Tol= 0.01
Num of Std Step Trials= 20
Max Error Tol= 0.3
Flow Tol Ratio= 0.001
Split Flow NTrial= 30
Split Flow Tol= 0.02
Split Flow Ratio= 0.02
Log Output Level= 0
Friction Slope Method= 1
Unsteady Friction Slope Method= 2
Unsteady Bridges Friction Slope Method= 1
Parabolic Critical Depth
Global Vel Dist=  1 , 1 , 1
Global Log Level= 0
CheckData=True
Encroach Param= -1, 0, 0, 0
BEGIN DESCRIPTION:
Multiple Run
END DESCRIPTION:

--- BRUSHYCREEKTRIB1.f01 (steady flow) ---

Flow Title=Multiple
Program Version=4.10
Number of Profiles= 7
Profile Names=10-year,25-year,50-year,1pct_min,100-year,1pct_plu,500-year
River Rch & RM=UNT05295 IN WICK,Reach-1         ,3765
     144     177     201     169     229     309     295
River Rch & RM=BRUSHYCRTR16,Reach-1         ,3765
     144     177     201     169     229     309     295
Boundary for River Rch & Prof#=BRUSHYCRTR16,Reach-1         , 1
Up Type= 0
Dn Type= 3
Dn Slope=0.005
Boundary for River Rch & Prof#=BRUSHYCRTR16,Reach-1         , 2
Up Type= 0
Dn Type= 3
Dn Slope=0.005
Boundary for River Rch & Prof#=BRUSHYCRTR16,Reach-1         , 3
Up Type= 0
Dn Type= 3
Dn Slope=0.005
Boundary for River Rch & Prof#=BRUSHYCRTR16,Reach-1         , 4
Up Type= 0
Dn Type= 3
Dn Slope=0.005
Boundary for River Rch & Prof#=BRUSHYCRTR16,Reach-1         , 5
Up Type= 0
Dn Type= 3
Dn Slope=0.005
Boundary for River Rch & Prof#=BRUSHYCRTR16,Reach-1         , 6
Up Type= 0
Dn Type= 3
Dn Slope=0.005
Boundary for River Rch & Prof#=BRUSHYCRTR16,Reach-1         , 7
Up Type= 0
Dn Type= 3
Dn Slope=0.005
DSS Import GetInterval= 0
DSS Import GetPeak= 0
DSS Import FillOption= 0

--- BRUSHYCREEKTRIB1.g01 (geometry) ---

Geom Title=Existing Conditions
Program Version=4.10

River Reach=BRUSHYCRTR16    ,Reach-1
Reach XY= 30
      3567780.77     10231825.08       3567927.3     10231900.08
      3568037.02     10231893.83      3568107.85     10231943.83
      3568204.32     10231932.19      3568421.33     10231863.18
      3568512.48     10231908.76      3568571.07     10231882.72
      3568624.46     10231899.64      3568690.86     10231839.75
      3568788.52     10231796.78      3568796.33     10231734.28
      3568770.29     10231709.54       3568778.1     10231688.71
      3568931.75     10231544.17      3569048.94     10231363.18
      3569054.15     10231326.73       3569275.5     10231255.11
      3569322.37     10231078.03      3569364.04     10231002.51
      3569454.67     10230949.54      3569496.91     10230894.13
      3569524.31     10230687.55      3569549.53     10230645.22
      3569715.43     10230449.82      3569946.73     10230373.46
      3570130.26     10230055.54      3570237.94     10229954.55
      3570249.23     10229912.82      3570192.11     10229711.64

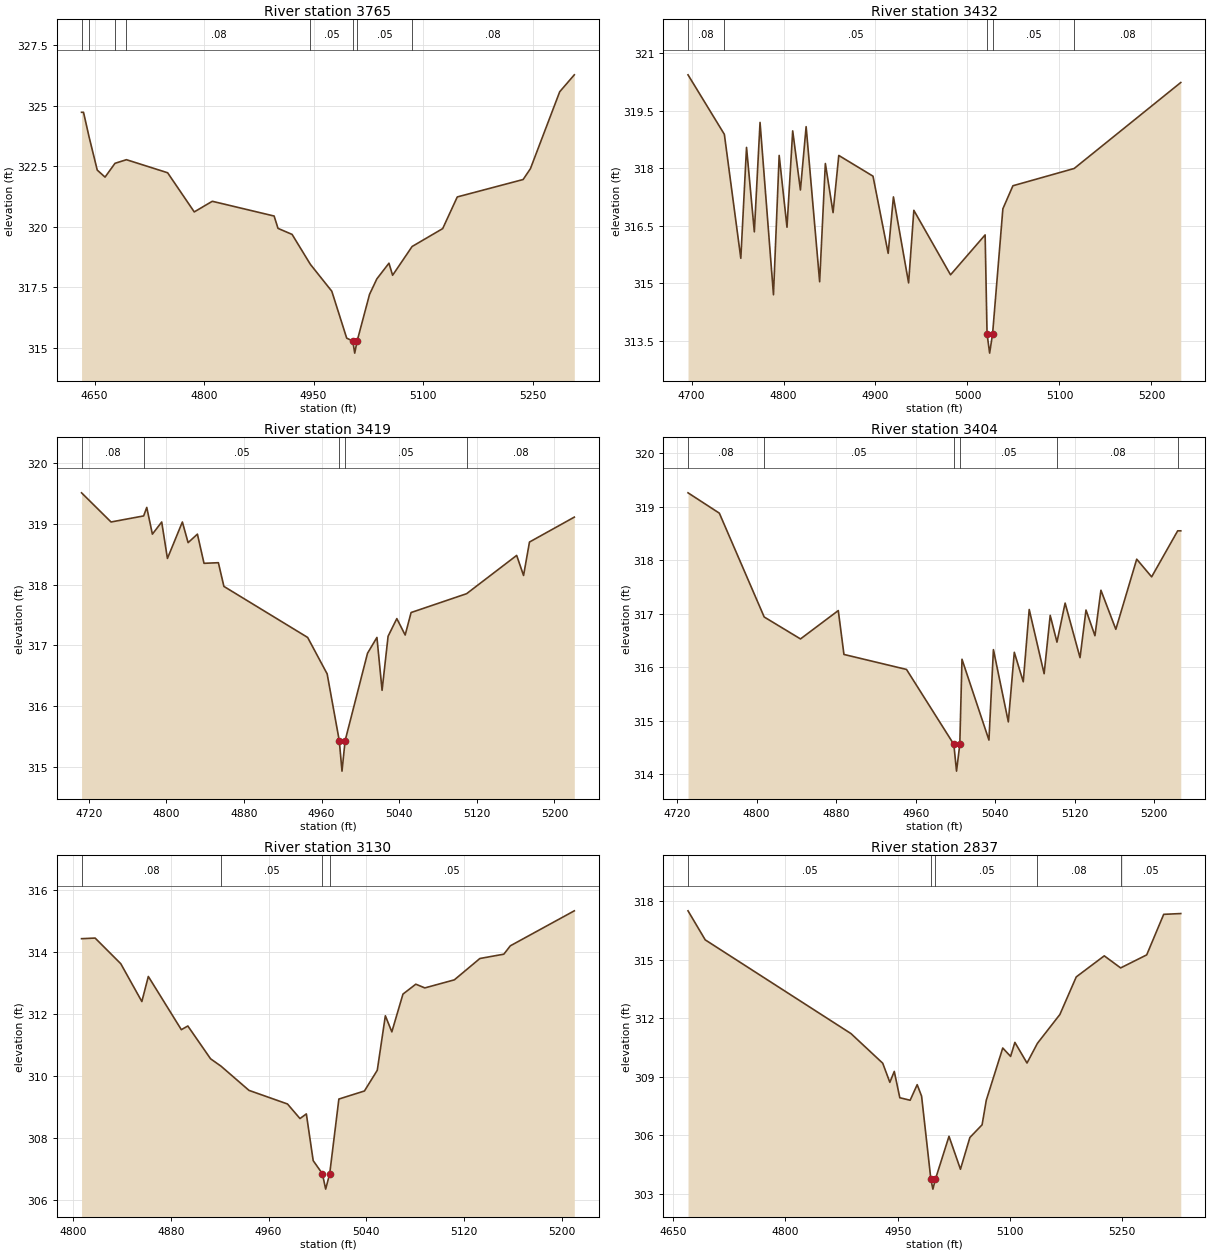
Type RM Length L Ch R = 1 ,3765    ,333,333,333
BEGIN DESCRIPTION:
UNT05295 IN WICK 8.0
END DESCRIPTION:
XS GIS Cut Line= 3
      3567792.09     10232241.68      3567923.82     10231898.69
       3567942.1     10231591.66
#Sta/Elev= 30
  4632.2  324.73  4634.9  324.73  4642.3  323.74  4653.7  322.34  4664.4  322.05
    4678  322.62  4693.7  322.77  4750.1  322.23  4786.6  320.61  4811.3  321.05
    4896  320.44  4901.3  319.93  4920.6  319.68  4945.7  318.44    4975  317.33
  4995.4  315.39  5003.7  315.27  5006.4  314.77  5009.7  315.27  5026.7   317.2
  5036.7  317.84  5053.3  318.49  5058.3  317.99    5085  319.18  5126.9  319.92
  5146.9  321.23  5237.1  321.95  5247.1   322.4  5287.2  325.58  5307.2  326.28
#Mann= 8 ,-1 , 0
  4632.2      .1       0  4642.3     .08       0    4678      .1       0
  4693.7     .08       0  4945.7     .05       0  5003.7     .04       0
  5009.7     .05       0    5085     .08       0
Bank Sta=5003.7,5009.7
XS Rating Curve= 0 ,0
Exp/Cntr=0.3,0.1

Type RM Length L Ch R = 1 ,3432    ,13,13,13
BEGIN DESCRIPTION:
Mapping XS 76b488af
END DESCRIPTION:
XS GIS Cut Line= 5
      3568091.75     10232181.14      3568194.83     10232041.17
      3568239.31     10231954.37      3568223.04     10231883.84
        3568107.     10231730.93
#Sta/Elev= 30
  4696.2  320.43  4735.7  318.88  4753.6  315.65  4759.8  318.54  4768.3  316.34
  4774.5  319.19  4789.1   314.7  4795.3  318.33  4803.8  316.46    4810  318.97
  4818.4  317.43  4824.6  319.08  4839.3  315.04  4845.5  318.12  4853.9  316.84
  4860.1  318.33  4897.3  317.79  4913.8  315.78  4919.5  317.25    4936  315.01
  4941.7   316.9  4981.6  315.22  5019.2  316.26  5021.3  313.68  5024.1  313.18
  5027.3  313.68  5038.5  316.94  5049.4  317.54    5116  317.99  5231.9  320.23
#Mann= 5 ,-1 , 0
  4696.2     .08       0  4735.7     .05       0  5021.3     .04       0
  5027.3     .05       0    5116     .08       0
Bank Sta=5021.3,5027.3
XS Rating Curve= 0 ,0
Exp/Cntr=0.3,0.1

Type RM Length L Ch R = 1 ,3419    ,15,15,15
BEGIN DESCRIPTION:
Mapping XS e65383ef
END DESCRIPTION:
XS GIS Cut Line= 6
      3568131.87     10232173.58      3568198.08     10232065.04
      3568243.65     10231986.92      3568250.16     10231935.92
      3568230.63      10231879.5      3568127.57     10231733.03
#Sta/Elev= 30
  4712.7  319.51  4743.1  319.03  4776.7  319.13  4779.9  319.27  4785.7  318.83
  4795.3  319.03  4801.2  318.43  4816.6  319.03  4822.5  318.69  4832.1  318.83
  4838.9  318.35  4853.7  318.36  4859.4  317.97  4945.7  317.13  4965.8  316.53
  4978.3  315.43  4981.1  314.93  4984.3  315.43  5007.4  316.87  5017.1  317.13
  5022.4  316.26  5028.6  317.15  5037.6  317.44  5046.2  317.17  5052.3  317.54
  5109.5  317.85  5161.1  318.48  5168.2  318.15  5174.3   318.7  5220.5  319.11
#Mann= 5 ,-1 , 0
  4712.7     .08       0  4776.7     .05       0  4978.3     .04       0
  4984.3     .05       0  5109.5     .08       0
Bank Sta=4978.3,4984.3
XS Rating Curve= 0 ,0
Exp/Cntr=0.3,0.1

Type RM Length L Ch R = 1 ,3404    ,274,274,274
BEGIN DESCRIPTION:
UNT05295 IN WICK 7.0
END DESCRIPTION:
XS GIS Cut Line= 5
      3568174.22     10232158.35      3568264.27     10231993.43
      3568266.44     10231938.09       3568248.9     10231881.43
      3568141.66     10231721.08
#Sta/Elev= 30
  4731.1  319.26  4762.6  318.88  4807.7  316.94  4844.2  316.53  4882.2  317.06
  4887.9  316.24  4950.8  315.96  4998.4  314.56  5001.1  314.06  5004.4  314.56
  5006.6  316.15  5033.7  314.64  5038.2  316.33  5053.2  314.98  5059.2  316.28
  5068.2  315.73  5074.2  317.08  5089.2  315.88  5095.3  316.97  5102.1  316.47
  5110.3   317.2  5125.3  316.18  5131.3  317.07  5140.3  316.59  5146.3  317.44
  5161.3  316.71  5182.3  318.02  5197.3  317.69  5223.5  318.55  5226.6  318.55
#Mann= 6 ,-1 , 0
  4731.1     .08       0  4807.7     .05       0  4998.4     .04       0
  5004.4     .05       0  5102.1     .08       0  5223.5      .1       0
Bank Sta=4998.4,5004.4
XS Rating Curve= 0 ,0
Exp/Cntr=0.3,0.1

Type RM Length L Ch R = 1 ,3130    ,293,293,293
BEGIN DESCRIPTION:
Mapping XS cf0d501e
END DESCRIPTION:
XS GIS Cut Line= 2
      3568572.44     10232092.21      3568450.91     10231708.08
#Sta/Elev= 30
  4807.1  314.43  4818.2  314.45  4839.2  313.62  4856.4   312.4  4861.7  313.21
  4888.7  311.49    4894  311.61  4912.6  310.55  4921.2  310.31    4944  309.53
  4975.5  309.09  4985.7  308.62  4990.9  308.77  4996.5  307.26    5004  306.84
  5006.7  306.34    5010  306.84  5017.5  309.25  5038.4  309.51  5048.9  310.18
  5055.5  311.94  5060.8  311.42  5069.9  312.64  5080.4  312.96  5087.8  312.84
  5111.9   313.1  5132.8  313.79  5152.4  313.93  5157.7   314.2    5210  315.33
#Mann= 4 ,-1 , 0
  4807.1     .08       0  4921.2     .05       0    5004     .04       0
    5010     .05       0
Bank Sta=5004,5010
XS Rating Curve= 0 ,0
Exp/Cntr=0.3,0.1

Type RM Length L Ch R = 1 ,2837    ,237,237,237
BEGIN DESCRIPTION:
UNT05295 IN WICK 6.0
END DESCRIPTION:
XS GIS Cut Line= 3
      3568942.11     10232091.65      3568746.74     10231778.55
      3568492.07     10231641.62
#Sta/Elev= 30
    4670  317.51    4693  316.02  4887.7  311.21  4930.1  309.69  4939.6  308.71
  4945.5  309.27  4952.9  307.92  4966.7  307.79  4976.1  308.59    4982     308
  4994.4  303.73  4997.1  303.23  5000.4  303.73  5018.6  305.94  5033.9  304.25
  5046.5  305.88  5062.8  306.53  5068.4  307.79  5090.4  310.47  5100.9  310.04
  5106.6  310.76  5122.8   309.7  5136.7  310.71  5166.7  312.19  5188.6  314.12
    5226   315.2  5247.9  314.58  5282.7  315.25  5305.4  317.33  5328.2  317.37
#Mann= 5 ,-1 , 0
    4670     .05       0  4994.4     .04       0  5000.4     .05       0
  5136.7     .08       0  5247.9     .05       0
Bank Sta=4994.4,5000.4
XS Rating Curve= 0 ,0
Exp/Cntr=0.3,0.1

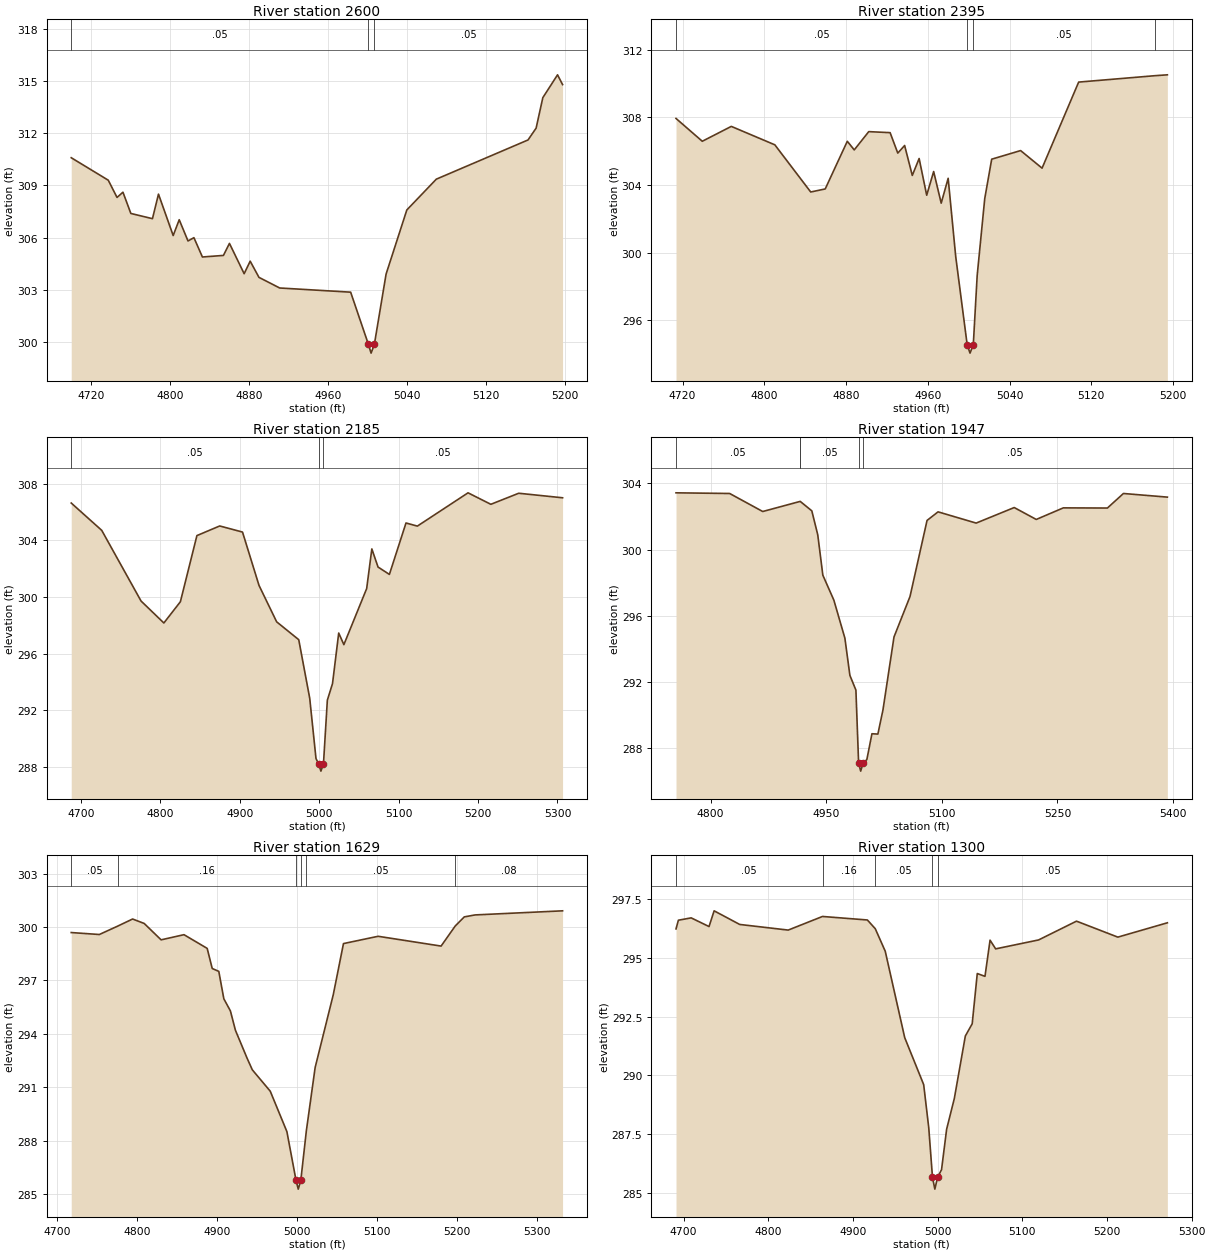
Type RM Length L Ch R = 1 ,2600    ,205,205,205
BEGIN DESCRIPTION:
Mapping XS ad96a090
END DESCRIPTION:
XS GIS Cut Line= 2
      3569092.11     10231794.94      3568679.92     10231515.82
#Sta/Elev= 30
  4700.2  310.59  4737.7   309.3  4746.6  308.31  4752.6  308.61  4760.6  307.39
  4782.5  307.09  4788.6   308.5  4803.5  306.12  4809.6  307.03  4818.5  305.81
  4824.5     306  4833.1  304.89  4854.4  304.98  4860.5  305.67  4875.4  303.93
  4881.5  304.65  4890.4  303.72  4911.4  303.11  4983.3  302.87  5001.3  299.87
    5004  299.37  5007.3  299.87  5019.2  303.91  5040.2  307.59  5070.1  309.36
    5163  311.61  5171.2  312.29    5178  314.04  5192.9  315.35    5198  314.79
#Mann= 3 ,-1 , 0
  4700.2     .05       0  5001.3     .04       0  5007.3     .05       0
Bank Sta=5001.3,5007.3
XS Rating Curve= 0 ,0
Exp/Cntr=0.3,0.1

Type RM Length L Ch R = 1 ,2395    ,210,210,210
BEGIN DESCRIPTION:
Mapping XS ec15288e
END DESCRIPTION:
XS GIS Cut Line= 2
       3569186.5     10231663.63      3568830.63     10231340.31
#Sta/Elev= 30
  4713.6  307.93  4739.3  306.58  4767.7  307.46  4810.3  306.37  4845.4  303.58
  4859.6  303.76  4881.2  306.58    4888  306.07  4902.2  307.15  4923.1  307.09
  4930.6  305.88  4937.3  306.33  4944.8  304.56  4951.5  305.56  4958.9  303.39
  4965.7  304.79  4973.1  302.92  4979.9  304.39  4987.3  299.76  4998.5  294.55
  5001.3  294.05  5004.5  294.55  5008.3  298.64  5015.7  303.19  5022.5  305.52
  5050.8  306.03  5071.8  304.99  5107.6  310.08  5182.5  310.46  5194.4  310.51
#Mann= 4 ,-1 , 0
  4713.6     .05       0  4998.5     .04       0  5004.5     .05       0
  5182.5     .08       0
Bank Sta=4998.5,5004.5
XS Rating Curve= 0 ,0
Exp/Cntr=0.3,0.1

Type RM Length L Ch R = 1 ,2185    ,238,238,238
BEGIN DESCRIPTION:
UNT05295 IN WICK 5.0
END DESCRIPTION:
XS GIS Cut Line= 2
      3569294.89     10231562.29      3568900.64     10231085.72
#Sta/Elev= 30
  4687.9  306.63  4726.3   304.7  4775.8  299.71  4804.5  298.16  4825.3  299.66
  4846.1  304.33  4874.8  305.01  4903.5  304.58  4924.3  300.81  4946.5  298.24
  4974.3  296.98  4988.1  292.85    4996  288.59  4999.4   288.2  5002.2   287.7
  5005.4   288.2  5010.3  292.71  5016.8  293.88  5024.6  297.45  5031.1  296.63
  5059.8  300.59  5066.3  303.39  5074.1  302.11  5088.4  301.59  5109.3  305.22
  5123.6     305  5187.4  307.35  5216.1  306.54  5251.2  307.32  5306.4     307
#Mann= 3 ,-1 , 0
  4687.9     .05       0  4999.4     .04       0  5005.4     .05       0
Bank Sta=4999.4,5005.4
XS Rating Curve= 0 ,0
Exp/Cntr=0.3,0.1

Type RM Length L Ch R = 1 ,1947    ,318,318,318
BEGIN DESCRIPTION:
Mapping XS 4737b7a5
END DESCRIPTION:
XS GIS Cut Line= 2
      3569439.79     10231402.41      3569028.49     10230915.34
#Sta/Elev= 30
  4755.1  303.43  4824.7  303.39  4867.6   302.3  4916.1  302.91  4916.3  302.91
  4931.3  302.34    4939  300.89  4945.6  298.45  4959.9  296.94  4974.2  294.64
  4980.7  292.39  4988.5   291.5    4992   287.1  4994.7   286.6    4998   287.1
  5002.7   287.3  5009.3  288.86    5017  288.84  5023.6   290.3  5037.9  294.71
  5058.7  297.16  5080.8  301.76  5095.1  302.28  5144.5   301.6  5193.9  302.54
  5222.5  301.82  5257.6  302.52  5314.8  302.51  5335.6  303.39  5392.6  303.17
#Mann= 5 ,-1 , 0
  4755.1     .05       0  4916.1     .16       0  4916.3     .05       0
    4992     .04       0    4998     .05       0
Bank Sta=4992,4998
XS Rating Curve= 0 ,0
Exp/Cntr=0.3,0.1

Type RM Length L Ch R = 1 ,1629    ,329,329,329
BEGIN DESCRIPTION:
UNT05295 IN WICK 4.0
END DESCRIPTION:
XS GIS Cut Line= 2
      3569611.72     10231180.33      3569235.06     10230695.44
#Sta/Elev= 30
    4718  299.69  4753.1  299.58    4776  300.05  4794.7  300.45  4809.2   300.2
  4830.3  299.28  4858.9  299.57  4887.9   298.8  4894.2  297.67  4902.4  297.51
  4908.7  295.97  4916.9  295.29  4923.2   294.2  4937.7  292.64  4944.3  291.98
  4966.7  290.78  4987.5  288.51  4998.9  285.78  5001.7  285.28  5004.9  285.78
  5011.8  288.55  5022.8  292.11  5045.4  296.19  5058.2  299.07  5101.5  299.48
  5180.2  298.93  5197.9  300.06  5209.2  300.57  5222.8  300.68    5332  300.91
#Mann= 6 ,-1 , 0
    4718     .05       0    4776     .16       0  4998.9     .07       0
  5004.9     .16       0  5011.8     .05       0  5197.9     .08       0
Bank Sta=4998.9,5004.9
XS Rating Curve= 0 ,0
Exp/Cntr=0.3,0.1

Type RM Length L Ch R = 1 ,1300    ,267,267,267
BEGIN DESCRIPTION:
UNT05295 IN WICK 3.0
END DESCRIPTION:
XS GIS Cut Line= 2
       3569798.4     10230828.82      3569312.25     10230511.95
#Sta/Elev= 30
    4691  296.23  4693.8   296.6  4708.9   296.7    4730  296.33    4736     297
  4766.2  296.42  4823.5  296.18    4864  296.76    4917  296.61  4926.3  296.24
  4938.1  295.28  4961.1   291.6  4983.5   289.6  4989.5  287.76  4993.9  285.65
  4996.7  285.15  4999.9  285.65  5004.6  285.98  5010.6   287.7  5019.7  289.01
  5032.7  291.67  5040.8  292.19  5046.8  294.33  5055.9  294.21  5061.9  295.75
  5068.5  295.38  5119.2  295.76    5164  296.56  5212.8  295.88  5271.3  296.49
#Mann= 5 ,-1 , 0
    4691     .05       0    4864     .16       0  4926.3     .05       0
  4993.9     .03       0  4999.9     .05       0
Bank Sta=4993.9,4999.9
XS Rating Curve= 0 ,0
Exp/Cntr=0.3,0.1

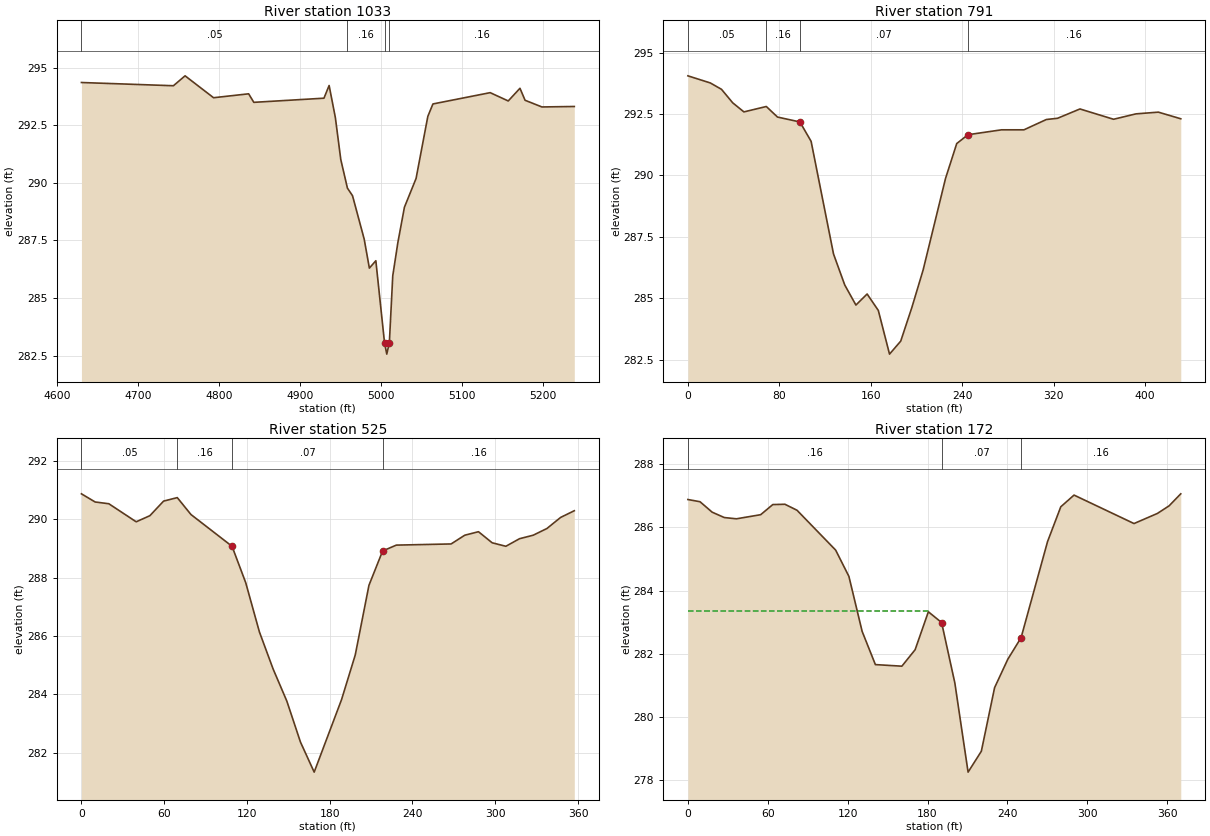
Type RM Length L Ch R = 1 ,1033    ,242,242,242
BEGIN DESCRIPTION:
UNT05295 IN WICK 2.0
END DESCRIPTION:
XS GIS Cut Line= 2
      3569998.06      10230685.6      3569520.64       10230308.
#Sta/Elev= 30
  4629.9  294.35  4743.5  294.21  4757.9  294.64  4793.1  293.69  4836.4  293.86
  4842.8  293.49  4929.4  293.67  4935.8  294.22  4943.5  292.83  4950.2  291.01
  4958.4  289.77  4964.7  289.44  4979.1  287.56  4985.5   286.3  4993.5  286.62
  5004.2  283.07    5007  282.57  5010.2  283.07  5014.4  285.97  5020.7  287.41
  5028.8  288.94  5043.2  290.19  5057.7  292.88    5064  293.42  5134.7  293.91
    5157  293.55  5171.5   294.1  5177.8  293.58  5198.6  293.29  5238.6  293.31
#Mann= 4 ,-1 , 0
  4629.9     .05       0  4958.4     .16       0  5004.2     .07       0
  5010.2     .16       0
Bank Sta=5004.2,5010.2
XS Rating Curve= 0 ,0
Exp/Cntr=0.3,0.1

Type RM Length L Ch R = 1 ,791     ,266,266,266
XS GIS Cut Line= 2
     3570088.829    10230476.713     3569720.774    10230250.324
#Sta/Elev= 30
       0  294.06    19.6  293.77    29.4  293.51    39.2  292.96   48.99  292.59
   68.59  292.81   78.39  292.38   97.99  292.18  107.79  291.39  127.39   286.8
  137.18  285.54  146.98  284.72  156.78  285.17  166.58   284.5  176.38  282.72
  186.18  283.25  195.98  284.63  205.78  286.15  225.37  289.88  235.17   291.3
  244.97  291.66  274.37  291.86  293.97  291.86  313.57  292.28  323.36  292.33
  342.96  292.71  372.36  292.29  391.96  292.51  411.55  292.58  431.15  292.31
#Mann= 4 ,-1 , 0
       0     .05       0   68.59     .16       0   97.99     .07       0
  244.97     .16       0
Bank Sta=97.99,244.97
XS Rating Curve= 0 ,0
Exp/Cntr=0.3,0.1

Type RM Length L Ch R = 1 ,525     ,353,353,353
XS GIS Cut Line= 2
     3570245.079     10230218.38     3569909.662    10230101.713
#Sta/Elev= 30
       0  290.88    9.93   290.6   19.85  290.54    39.7  289.92   49.63  290.13
   59.55  290.63   69.48  290.75    79.4  290.17  109.18  289.08   119.1  287.83
  129.03  286.14  138.95  284.87  148.88  283.77   158.8  282.36  168.73  281.33
  188.58  283.82   198.5  285.35  208.43  287.74  218.35  288.92  228.28  289.12
  267.98  289.16   277.9  289.46  287.83  289.58  297.75   289.2  307.68  289.08
   317.6  289.34  327.53  289.46  337.45  289.69  347.38  290.07   357.3   290.3
#Mann= 4 ,-1 , 0
       0     .05       0   69.48     .16       0  109.18     .07       0
  218.35     .16       0
Bank Sta=109.18,218.35
XS Rating Curve= 0 ,0
Exp/Cntr=0.3,0.1

Type RM Length L Ch R = 1 ,172     ,,,
XS GIS Cut Line= 4
      3570397.91     10229957.49     3570360.584    10229877.629
     3570151.382    10229875.025      3570116.66    10229931.449
#Sta/Elev= 30
       0  286.88    9.11  286.81   18.22  286.48   27.33  286.31   36.44  286.27
   54.66   286.4   63.76  286.72   72.87  286.73   81.98  286.54  110.99  285.28
  120.93  284.45  130.88  282.71  140.83  281.66  160.72  281.61  170.67  282.13
  180.62  283.33  190.57  282.99  200.51  281.08  210.46  278.26  220.41  278.92
  230.36  280.93   240.3  281.83  250.25  282.51  270.15  285.55  280.09  286.65
  290.04  287.02   335.1  286.12  352.66  286.44  361.44  286.68  370.21  287.06
#Mann= 3 ,-1 , 0
       0     .16       0  190.57     .07       0  250.25     .16       0
#XS Ineff= 2 , 0
          180.82  283.34
Permanent Ineff=
       F       F
Bank Sta=190.57,250.25
XS Rating Curve= 0 ,0
Exp/Cntr=0.3,0.1

Chan Stop Cuts=-1
Use User Specified Reach Order=0
Composite Channel Slope=5