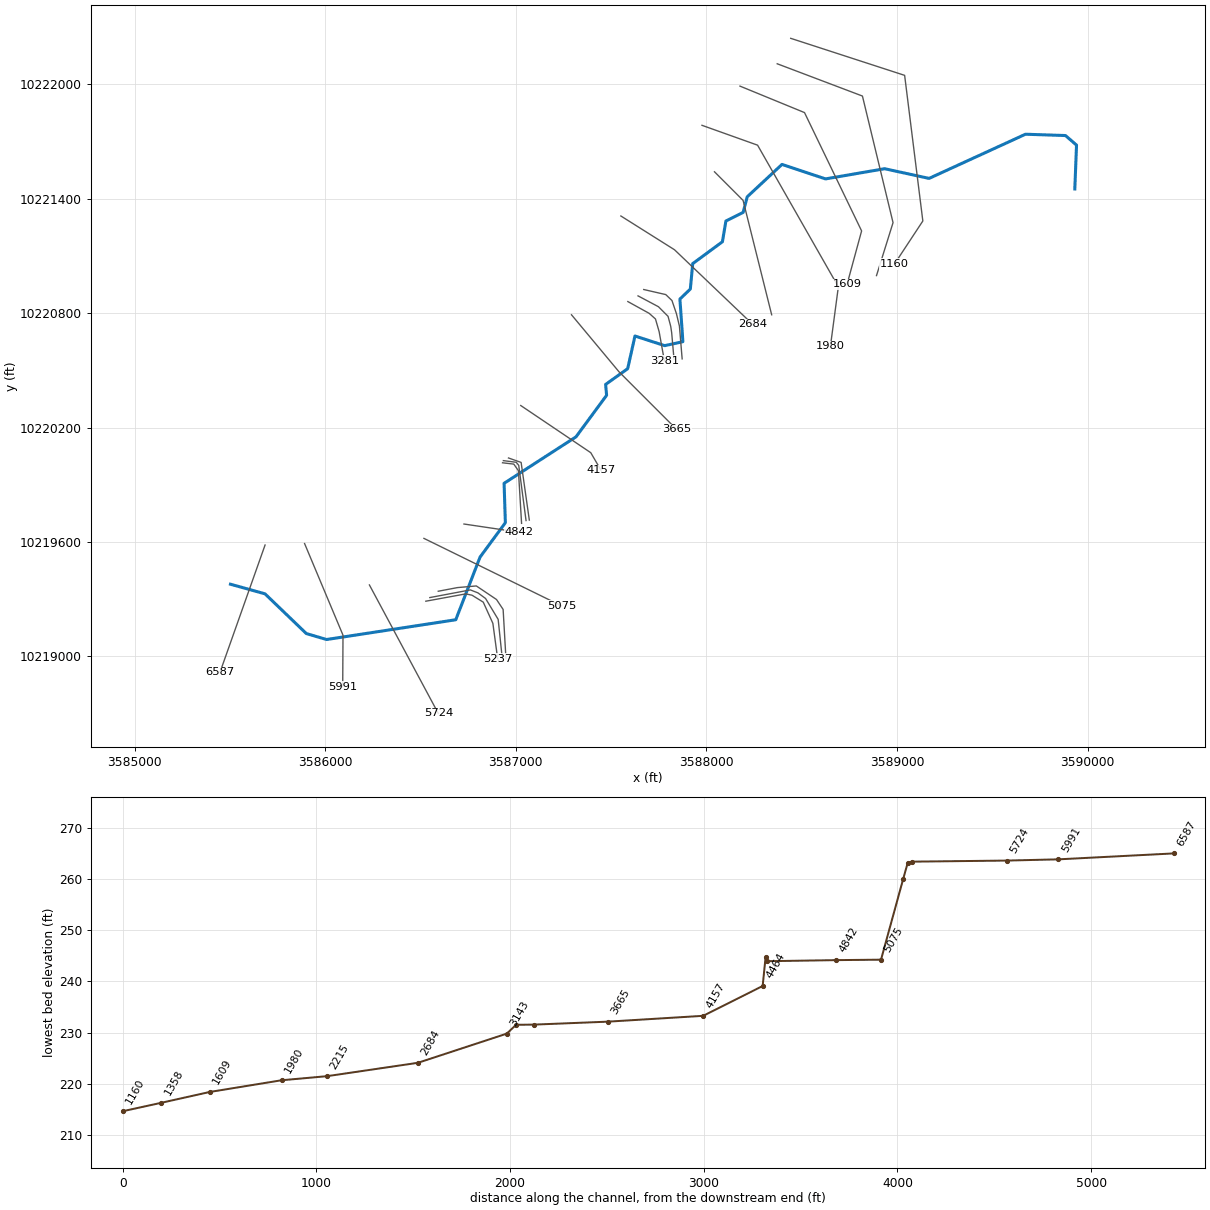
--- BRUSHYCREEKTRIB2.prj (project) ---

Proj Title=BRUSHY CREEK TRIB 2 1
Current Plan=p01
Default Exp/Contr=0.3,0.1
English Units
Geom File=g01
Flow File=f01
Plan File=p01
Y Axis Title=Elevation
X Axis Title(PF)=Main Channel Distance
X Axis Title(XS)=Station
BEGIN DESCRIPTION:
UNT05324 IN WICK
END DESCRIPTION:
DSS Export Rating Curves= 0
DSS Export Rating Curve Sorted= 0
DSS Export Volume Flow Curves= 0
DXF Filename=UNT05324 IN WICK.
DXF OffsetX= 0
DXF OffsetY= 0
DXF ScaleX= 1
DXF ScaleY= 10

--- BRUSHYCREEKTRIB2.p01 (plan) ---

Plan Title=Multiple Run
Short Identifier=Multiple
Geom File=g01
Flow File=f01
Subcritical Flow
K Sum by GR= 0
Std Step Tol= 0.01
Critical Tol= 0.01
Num of Std Step Trials= 20
Max Error Tol= 0.3
Flow Tol Ratio= 0.001
Split Flow NTrial= 30
Split Flow Tol= 0.02
Split Flow Ratio= 0.02
Log Output Level= 0
Friction Slope Method= 1
Unsteady Friction Slope Method= 2
Unsteady Bridges Friction Slope Method= 1
Parabolic Critical Depth
Global Vel Dist=  1 , 1 , 1
Global Log Level= 0
CheckData=True
Encroach Param= -1, 0, 0, 0
BEGIN DESCRIPTION:
Multiple Run
END DESCRIPTION:

--- BRUSHYCREEKTRIB2.f01 (steady flow) ---

Flow Title=Multiple
Program Version=4.10
Number of Profiles= 7
Profile Names=10-year,25-year,50-year,1pct_min,100-year,1pct_plu,500-year
River Rch & RM=UNT05324 IN WICK,Reach-1         ,6587
     282     364     429     371     502     678     687
River Rch & RM=BRUSHYCRTR21,Reach-1         ,6587
     282     364     429     371     502     678     687
Boundary for River Rch & Prof#=BRUSHYCRTR21,Reach-1         , 1
Up Type= 0
Dn Type= 3
Dn Slope=0.005
Boundary for River Rch & Prof#=BRUSHYCRTR21,Reach-1         , 2
Up Type= 0
Dn Type= 3
Dn Slope=0.005
Boundary for River Rch & Prof#=BRUSHYCRTR21,Reach-1         , 3
Up Type= 0
Dn Type= 3
Dn Slope=0.005
Boundary for River Rch & Prof#=BRUSHYCRTR21,Reach-1         , 4
Up Type= 0
Dn Type= 3
Dn Slope=0.005
Boundary for River Rch & Prof#=BRUSHYCRTR21,Reach-1         , 5
Up Type= 0
Dn Type= 3
Dn Slope=0.005
Boundary for River Rch & Prof#=BRUSHYCRTR21,Reach-1         , 6
Up Type= 0
Dn Type= 3
Dn Slope=0.005
Boundary for River Rch & Prof#=BRUSHYCRTR21,Reach-1         , 7
Up Type= 0
Dn Type= 3
Dn Slope=0.005
DSS Import GetInterval= 0
DSS Import GetPeak= 0
DSS Import FillOption= 0

--- BRUSHYCREEKTRIB2.g01 (geometry) ---

Geom Title=Existing Conditions
Program Version=4.10

River Reach=BRUSHYCRTR21    ,Reach-1
Reach XY= 30
      3585503.32     10219378.46      3585684.57     10219327.93
      3585901.23      10219119.6      3586007.48     10219088.35
      3586685.09       10219192.      3586812.44     10219520.46
      3586945.25     10219701.02      3586938.57     10219907.62
      3587315.76     10220151.42      3587476.21     10220369.19
      3587471.22     10220426.43      3587586.77     10220508.78
      3587624.99     10220680.26      3587781.14     10220629.78
       3587876.4     10220650.46      3587860.79     10220874.07
      3587915.47     10220926.67      3587927.97       10221060.
       3588083.7     10221174.59      3588101.93     10221283.44
      3588192.56     10221328.75      3588213.91     10221410.52
       3588396.2     10221580.31      3588624.76     10221504.36
      3588934.66     10221557.75      3589167.73     10221506.96
      3589673.48     10221738.69      3589883.32     10221731.77
       3589941.1     10221681.51      3589932.11     10221451.64

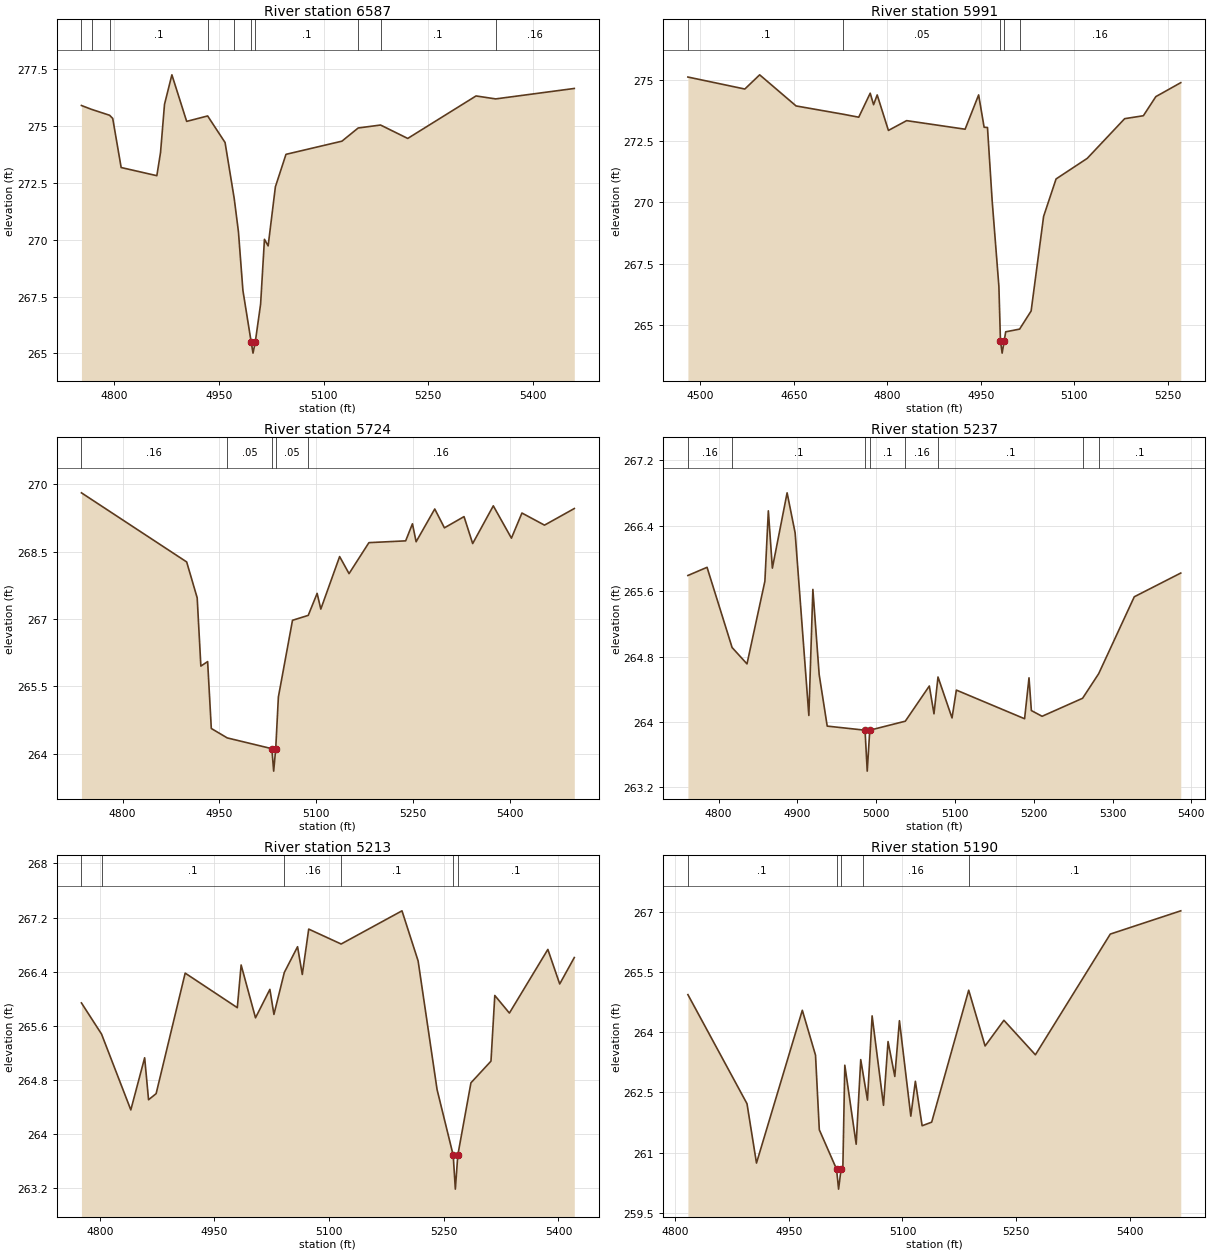
Type RM Length L Ch R = 1 ,6587    ,596,596,596
BEGIN DESCRIPTION:
UNT05324 IN WICK 13.0
END DESCRIPTION:
XS GIS Cut Line= 2
      3585684.85     10219583.99      3585448.75     10218917.36
#Sta/Elev= 30
  4752.6  275.91  4767.1  275.74    4793  275.48  4797.5  275.34  4809.6  273.18
  4860.8  272.82  4866.1  273.84  4871.8  275.96  4882.4  277.26  4903.6  275.21
  4933.7  275.45  4958.7  274.28  4971.8  271.82  4977.9  270.35  4984.3  267.77
  4996.1  265.51  4998.8  265.01  5002.1  265.51  5009.7  267.17  5015.2  270.02
  5020.5  269.73  5030.9  272.33  5046.1  273.76  5126.4  274.34  5149.7  274.92
  5181.8  275.05  5220.8  274.46  5318.8  276.33    5347   276.2  5459.8  276.66
#Mann= 10 ,-1 , 0
  4752.6      .1       0  4767.1     .16       0    4793      .1       0
  4933.7     .16       0  4971.8      .1       0  4996.1     .07       0
  5002.1      .1       0  5149.7     .16       0  5181.8      .1       0
    5347     .16       0
Bank Sta=4996.1,5002.1
XS Rating Curve= 0 ,0
Exp/Cntr=0.3,0.1

Type RM Length L Ch R = 1 ,5991    ,267,267,267
BEGIN DESCRIPTION:
UNT05324 IN WICK 12.0
END DESCRIPTION:
XS GIS Cut Line= 3
      3585892.11     10219591.64      3586093.62     10219111.04
      3586092.11     10218841.68
#Sta/Elev= 30
  4480.3  275.12  4571.6  274.63  4595.4  275.21  4653.8  273.94  4729.7   273.6
  4754.3  273.48  4772.7  274.46  4778.1  273.99  4783.9  274.39  4801.9  272.94
  4831.1  273.34  4924.9  272.99  4946.6  274.39  4955.4  273.07  4960.8  273.06
  4968.3  270.07  4979.1  266.57  4981.6  264.35  4984.3  263.85  4987.6  264.35
    4990  264.72  5012.3  264.83  5030.8  265.57  5050.8  269.43  5070.8  270.96
  5120.8   271.8  5180.8  273.42  5210.8  273.54  5230.8  274.32  5270.8  274.89
#Mann= 5 ,-1 , 0
  4480.3      .1       0  4729.7     .05       0  4981.6    .033       0
  4987.6     .05       0  5012.3     .16       0
Bank Sta=4981.6,4987.6
XS Rating Curve= 0 ,0
Exp/Cntr=0.3,0.1

Type RM Length L Ch R = 1 ,5724    ,487,487,487
BEGIN DESCRIPTION:
UNT05324 IN WICK 11.0
END DESCRIPTION:
XS GIS Cut Line= 2
      3586232.15     10219374.56      3586593.26     10218700.94
#Sta/Elev= 30
  4736.1  269.81  4899.3  268.27  4915.6  267.47  4921.3  265.95  4931.8  266.05
  4937.5  264.56  4962.2  264.35  5031.4  264.11  5034.2  263.61  5037.4  264.11
  5041.5  265.26  5063.4  266.97  5087.8  267.08  5101.6  267.57  5107.3  267.22
  5136.5  268.39  5151.1  268.01  5181.9   268.7  5238.9  268.74  5249.4  269.12
  5255.1  268.72    5284  269.45    5299  269.03  5329.4  269.28  5342.8  268.68
  5374.8  269.52  5402.9   268.8  5419.2  269.36  5454.2  269.09  5500.4  269.46
#Mann= 5 ,-1 , 0
  4736.1     .16       0  4962.2     .05       0  5031.4    .033       0
  5037.4     .05       0  5087.8     .16       0
Bank Sta=5031.4,5037.4
XS Rating Curve= 0 ,0
Exp/Cntr=0.3,0.1

Type RM Length L Ch R = 1 ,5237    ,24,24,24
BEGIN DESCRIPTION:
Mapping XS f969c474
END DESCRIPTION:
XS GIS Cut Line= 6
      3586528.11     10219289.31      3586737.35      10219327.7
      3586770.33     10219320.76      3586829.36      10219284.3
      3586879.71     10219173.19      3586904.89     10218987.23
#Sta/Elev= 30
  4761.1  265.79  4785.4  265.89  4817.2  264.91  4836.1  264.71  4858.8  265.72
  4863.2  266.58  4868.3  265.88    4887   266.8  4897.2  266.31  4914.6  264.08
  4919.7  265.62  4927.7  264.58  4937.9  263.95  4985.9   263.9  4988.7   263.4
  4991.9   263.9    5037  264.01  5067.5  264.44  5073.4   264.1  5078.5  264.55
  5096.3  264.05  5101.8  264.39  5188.4  264.04    5194  264.54    5197  264.14
  5210.6  264.07    5262  264.29  5282.4  264.59  5327.6  265.53  5386.6  265.82
#Mann= 8 ,-1 , 0
  4761.1     .16       0  4817.2      .1       0  4985.9     .07       0
  4991.9      .1       0    5037     .16       0  5078.5      .1       0
    5262     .05       0  5282.4      .1       0
Bank Sta=4985.9,4991.9
XS Rating Curve= 0 ,0
Exp/Cntr=0.3,0.1

Type RM Length L Ch R = 1 ,5213    ,23,23,23
BEGIN DESCRIPTION:
Mapping XS a599ca75
END DESCRIPTION:
XS GIS Cut Line= 6
      3586549.02     10219308.42      3586761.65     10219348.54
      3586801.58     10219332.91      3586841.51      10219303.4
      3586907.48     10219194.02      3586929.19     10218987.25
#Sta/Elev= 30
    4776  265.94  4802.3  265.48  4840.6  264.36  4858.7  265.13  4863.8  264.51
  4873.7   264.6  4911.7  266.38  4979.9  265.87  4984.9   266.5  5003.7  265.72
  5022.5  266.14  5027.8  265.77  5041.4  266.39  5058.7  266.77  5064.9  266.36
  5073.3  267.03  5115.7  266.81  5195.3   267.3  5216.4  266.56  5241.2  264.66
  5262.3  263.69  5265.1  263.19  5268.3  263.69  5285.5  264.76  5311.7  265.08
  5316.7  266.05  5335.8  265.79  5386.1  266.73  5401.6  266.22  5420.7  266.61
#Mann= 6 ,-1 , 0
    4776     .16       0  4802.3      .1       0  5041.4     .16       0
  5115.7      .1       0  5262.3     .07       0  5268.3      .1       0
Bank Sta=5262.3,5268.3
XS Rating Curve= 0 ,0
Exp/Cntr=0.3,0.1

Type RM Length L Ch R = 1 ,5190    ,115,115,115
BEGIN DESCRIPTION:
Mapping XS a8e6859a
END DESCRIPTION:
XS GIS Cut Line= 6
      3586593.28      10219341.6      3586693.94     10219360.69
       3586792.9     10219369.37       3586898.8     10219298.19
      3586933.53     10219246.11      3586948.29     10218988.92
#Sta/Elev= 30
  4817.2  264.94  4895.1  262.22  4907.6  260.74    4968  264.55  4985.4  263.43
  4990.4  261.57  5013.1  260.59  5015.8  260.09  5019.1  260.59  5021.4  260.59
    5024  263.18    5039  261.21    5045  263.32  5048.4  262.93  5053.9  262.31
    5060  264.41    5075  262.18    5081  263.77  5089.9   262.9    5096  264.29
    5111  261.91    5117  262.78  5125.9  261.67  5138.5  261.76  5187.3  265.05
  5208.9  263.66  5233.7   264.3  5275.2  263.44  5373.9  266.45  5466.8  267.03
#Mann= 5 ,-1 , 0
  4817.2      .1       0  5013.1     .07       0  5019.1      .1       0
  5048.4     .16       0  5187.3      .1       0
Bank Sta=5013.1,5019.1
XS Rating Curve= 0 ,0
Exp/Cntr=0.3,0.1

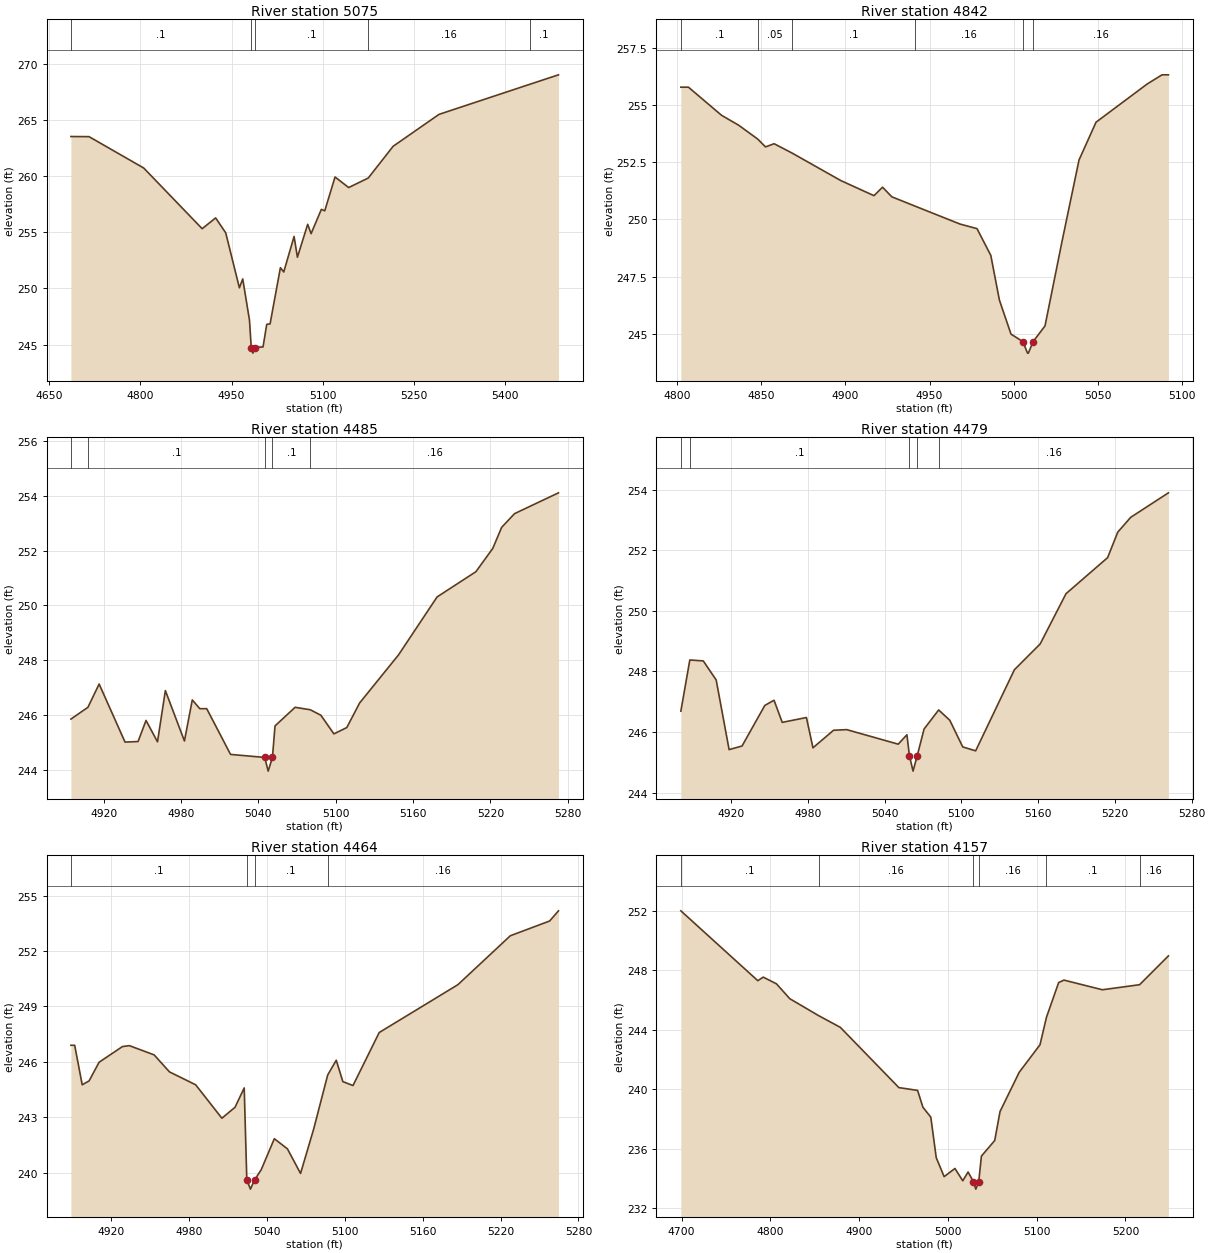
Type RM Length L Ch R = 1 ,5075    ,233,233,233
BEGIN DESCRIPTION:
UNT05324 IN WICK 10.0
END DESCRIPTION:
XS GIS Cut Line= 2
       3586518.2     10219618.75      3587238.73     10219265.41
#Sta/Elev= 30
  4685.5  263.52  4715.3  263.51  4805.3  260.72  4901.5  255.32  4923.7  256.28
  4940.3  254.95  4962.8  250.06  4968.3  250.85  4979.4  247.19  4982.3  244.75
    4985  244.25  4988.3  244.75  5001.7   244.8  5007.8  246.81  5013.3  246.85
  5030.3  251.85  5035.8  251.47  5052.8  254.63  5058.3  252.78  5075.2  255.71
  5080.8  254.88  5097.7  257.04  5103.3  256.91  5120.2  259.92  5142.7  258.98
  5174.9  259.83  5215.8  262.65  5291.3  265.49  5440.9  268.17    5488  269.01
#Mann= 5 ,-1 , 0
  4685.5      .1       0  4982.3     .07       0  4988.3      .1       0
  5174.9     .16       0  5440.9      .1       0
Bank Sta=4982.3,4988.3
XS Rating Curve= 0 ,0
Exp/Cntr=0.3,0.1

Type RM Length L Ch R = 1 ,4842    ,357,357,357
BEGIN DESCRIPTION:
Mapping XS 89edac5e
END DESCRIPTION:
XS GIS Cut Line= 2
      3586728.15     10219694.16      3587014.61     10219651.62
#Sta/Elev= 29
  4802.3  255.78  4806.8  255.78  4826.5  254.55  4836.6  254.12    4848  253.51
  4852.6  253.17  4857.7  253.31  4868.4   252.9  4897.3   251.7    4917  251.04
  4922.1  251.41  4927.6  250.99  4941.5  250.58  4968.1   249.8  4978.2   249.6
  4986.4  248.43  4991.5  246.48  4998.4  244.99  5005.5  244.66  5008.2  244.16
  5008.7  244.16  5011.5  244.66  5018.6  245.35  5028.7  249.04  5038.8   252.6
  5048.9  254.25  5079.3  255.92  5088.1  256.32  5091.9  256.32
#Mann= 6 ,-1 , 0
  4802.3      .1       0    4848     .05       0  4868.4      .1       0
  4941.5     .16       0  5005.5     .07       0  5011.5     .16       0
Bank Sta=5005.5,5011.5
XS Rating Curve= 0 ,0
Exp/Cntr=0.3,0.1

Type RM Length L Ch R = 1 ,4485    ,6,6,6
BEGIN DESCRIPTION:
Mapping XS 7b8b19e2
END DESCRIPTION:
XS GIS Cut Line= 4
       3586930.4     10220015.34      3586989.47     10220008.39
      3587013.77     10219973.67      3587030.26     10219697.62
#Sta/Elev= 30
  4894.5  245.85  4907.7  246.28  4916.4  247.13  4936.5  245.01  4946.6  245.03
  4952.8   245.8  4961.7  245.02  4967.8  246.89  4982.6  245.05  4988.7  246.55
  4994.5  246.23  4999.9  246.23  5018.4  244.56  5044.9  244.45  5047.6  243.95
  5050.9  244.45  5052.9   245.6  5068.5  246.28  5080.3  246.19  5088.5  245.99
  5098.6  245.31  5108.6  245.54  5118.6  246.44  5148.7  248.19  5178.7  250.31
  5208.8  251.23  5221.9  252.08  5228.8  252.85  5238.8  253.35  5272.9  254.11
#Mann= 5 ,-1 , 0
  4894.5     .16       0  4907.7      .1       0  5044.9     .07       0
  5050.9      .1       0  5080.3     .16       0
Bank Sta=5044.9,5050.9
XS Rating Curve= 0 ,0
Exp/Cntr=0.3,0.1

Type RM Length L Ch R = 1 ,4479    ,15,15,15
BEGIN DESCRIPTION:
Mapping XS 40397da0
END DESCRIPTION:
XS GIS Cut Line= 5
      3586934.74     10220026.62      3587002.49     10220017.94
      3587015.39     10220001.66      3587020.07     10219966.29
       3587053.7     10219712.36
#Sta/Elev= 30
  4880.9  246.69  4887.9  248.38  4898.4  248.35  4908.5  247.72  4918.6  245.42
  4928.7  245.54  4946.5  246.88  4953.7  247.05  4960.1  246.32    4979  246.48
  4984.1  245.48  5000.2  246.06  5010.5  246.08  5050.7   245.6  5057.5  245.91
  5059.5  245.21  5062.3  244.71  5065.5  245.21  5070.9   246.1  5082.3  246.73
    5091  246.39  5101.1  245.51  5111.2  245.38  5141.5  248.06  5161.6  248.91
  5181.8  250.57  5214.3  251.76  5222.2   252.6  5232.3  253.09  5261.8   253.9
#Mann= 5 ,-1 , 0
  4880.9     .16       0  4887.9      .1       0  5059.5     .07       0
  5065.5      .1       0  5082.3     .16       0
Bank Sta=5059.5,5065.5
XS Rating Curve= 0 ,0
Exp/Cntr=0.3,0.1

Type RM Length L Ch R = 1 ,4464    ,307,307,307
BEGIN DESCRIPTION:
UNT05324 IN WICK 9.0
END DESCRIPTION:
XS GIS Cut Line= 3
      3586961.66     10220040.52      3587027.93     10220017.23
      3587070.84      10219714.9
#Sta/Elev= 30
    4889   246.9  4891.9   246.9  4897.7  244.76    4903  244.97  4910.7  245.98
  4928.7  246.83    4934  246.88  4953.1  246.38  4964.9  245.46  4985.1  244.76
  5005.3  242.95  5015.4  243.54  5022.5  244.59  5024.5  239.61  5027.3  239.11
  5030.5  239.61  5035.6  240.16  5045.7  241.84  5055.8  241.29  5065.9  239.96
    5076  242.36  5086.8  245.29  5093.4  246.09  5098.5  244.93  5106.3  244.72
  5126.5  247.59  5187.1  250.18  5227.5  252.83  5257.8  253.63  5264.6  254.18
#Mann= 4 ,-1 , 0
    4889      .1       0  5024.5     .07       0  5030.5      .1       0
  5086.8     .16       0
Bank Sta=5024.5,5030.5
XS Rating Curve= 0 ,0
Exp/Cntr=0.3,0.1

Type RM Length L Ch R = 1 ,4157    ,492,492,492
BEGIN DESCRIPTION:
UNT05324 IN WICK 8.0
END DESCRIPTION:
XS GIS Cut Line= 3
      3587025.97     10220315.65      3587393.19     10220068.23
      3587446.86     10219976.23
#Sta/Elev= 30
  4699.2     252  4785.9   247.3    4792  247.54  4806.9  247.09  4821.9  246.09
  4854.4  244.95  4878.9  244.16  4944.8  240.11  4965.9  239.92  4971.9  238.79
  4980.8  238.12  4986.9   235.4  4995.8  234.12    5008  234.67  5016.8  233.84
  5022.8  234.43  5028.8  233.78  5031.5  233.28  5034.8  233.78  5037.8   235.5
  5052.8  236.55  5058.8   238.5  5080.4  241.14  5103.8  242.99  5111.1  244.84
  5124.8  247.17  5130.8  247.34  5174.1  246.69    5216  247.03  5248.5  248.97
#Mann= 6 ,-1 , 0
  4699.2      .1       0  4854.4     .16       0  5028.8     .07       0
  5034.8     .16       0  5111.1      .1       0    5216     .16       0
Bank Sta=5028.8,5034.8
XS Rating Curve= 0 ,0
Exp/Cntr=0.3,0.1

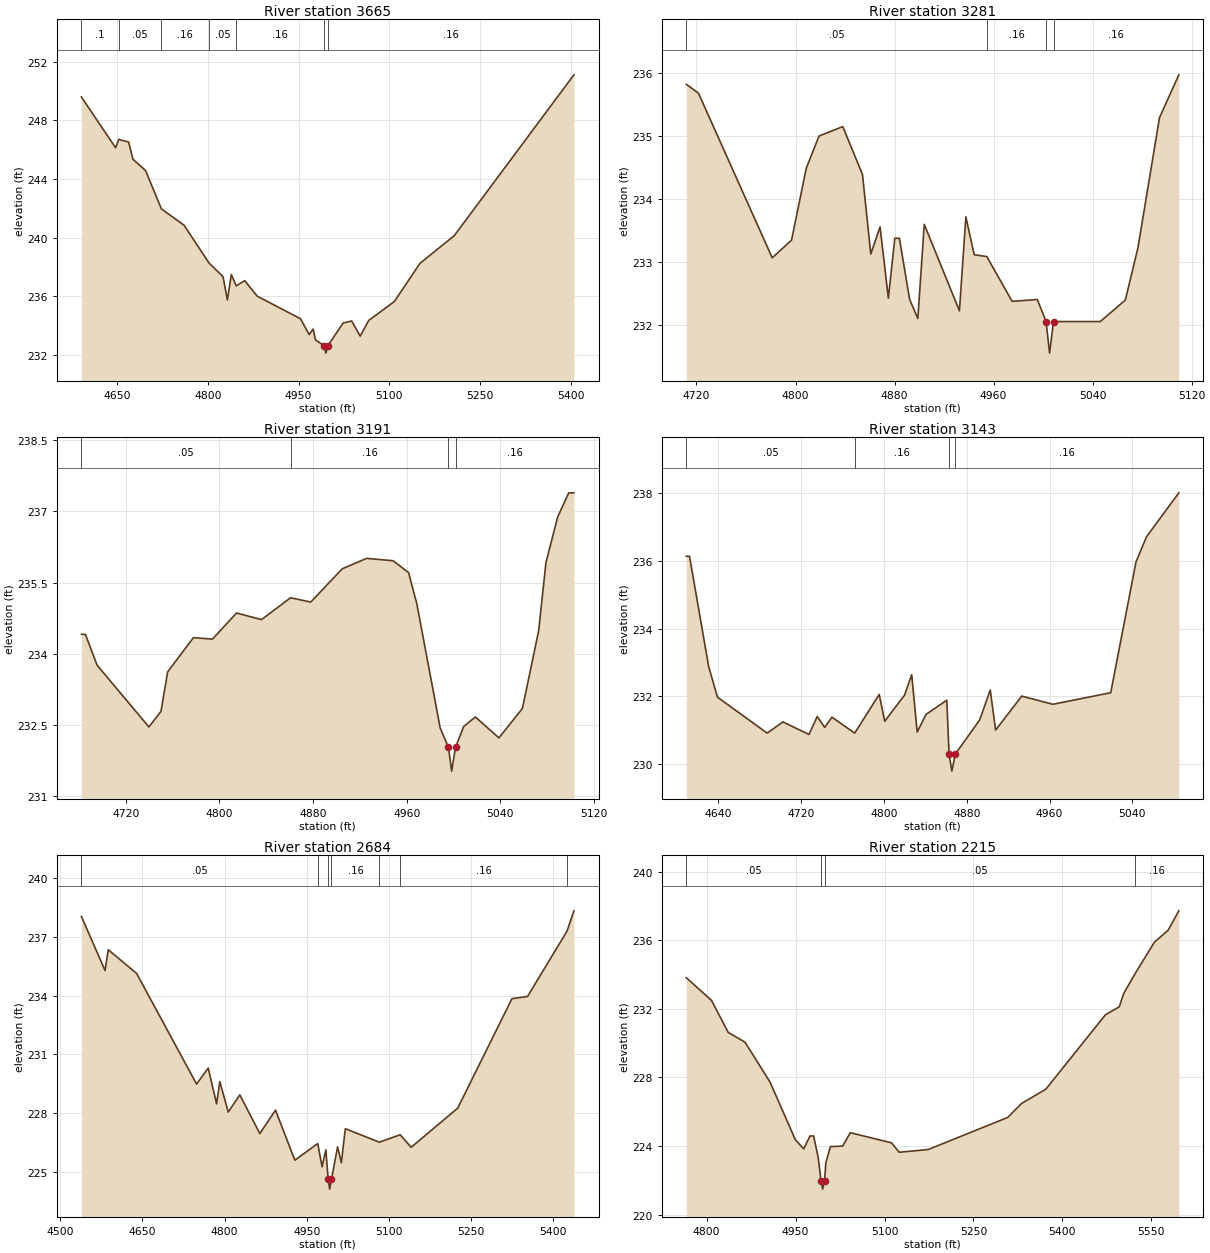
Type RM Length L Ch R = 1 ,3665    ,384,384,384
BEGIN DESCRIPTION:
UNT05324 IN WICK 7.0
END DESCRIPTION:
XS GIS Cut Line= 3
       3587292.1     10220791.64      3587542.11     10220491.64
      3587842.12     10220191.63
#Sta/Elev= 30
  4590.7  249.59  4647.3  246.13  4652.5   246.7  4668.8  246.52    4676  245.35
  4696.8  244.58    4723  241.97  4760.6  240.85    4802  238.27    4825  237.35
  4832.2  235.76  4838.7  237.49  4846.9  236.72  4860.8  237.08  4881.6  236.02
  4953.2  234.48  4967.5   233.4  4974.1  233.78    4978  233.04  4992.4  232.64
  4995.1  232.14  4998.4  232.64  5023.6  234.19  5037.8  234.33  5051.9   233.3
  5066.1  234.37  5108.5  235.66  5150.9  238.26  5207.5  240.14  5405.5   251.1
#Mann= 7 ,-1 , 0
  4590.7      .1       0  4652.5     .05       0    4723     .16       0
    4802     .05       0  4846.9     .16       0  4992.4     .07       0
  4998.4     .16       0
Bank Sta=4992.4,4998.4
XS Rating Curve= 0 ,0
Exp/Cntr=0.3,0.1

Type RM Length L Ch R = 1 ,3281    ,90,90,90
BEGIN DESCRIPTION:
Mapping XS 030c8faa
END DESCRIPTION:
XS GIS Cut Line= 5
      3587587.69     10220860.94      3587699.62     10220799.13
       3587732.6     10220769.62       3587751.7     10220703.65
      3587779.48     10220549.13
#Sta/Elev= 30
  4711.8  235.82  4721.6  235.68  4781.2  233.07  4796.8  233.35  4808.7  234.49
    4819     235  4838.2  235.15  4854.1  234.39  4860.8  233.13  4868.3  233.56
    4875  232.43  4880.2  233.38  4883.9  233.38  4892.2  232.41  4898.8  232.11
    4904   233.6  4932.4  232.23  4937.6  233.72  4944.3  233.12  4954.5  233.09
    4975  232.38  4995.3  232.41  5002.4  232.06  5005.2  231.56  5008.4  232.06
  5046.1  232.06  5066.4   232.4  5076.6  233.23    5094  235.29  5109.6  235.97
#Mann= 4 ,-1 , 0
  4711.8     .05       0  4954.5     .16       0  5002.4     .07       0
  5008.4     .16       0
Bank Sta=5002.4,5008.4
XS Rating Curve= 0 ,0
Exp/Cntr=0.3,0.1

Type RM Length L Ch R = 1 ,3191    ,48,48,48
BEGIN DESCRIPTION:
Mapping XS 53dc0e6f
END DESCRIPTION:
XS GIS Cut Line= 6
      3587641.17      10220890.8      3587748.23     10220833.86
      3587798.58     10220783.51      3587812.46     10220731.42
      3587817.67      10220696.7      3587829.83     10220557.81
#Sta/Elev= 30
    4682  234.41  4685.4  234.41  4695.4  233.76  4739.7  232.46    4750  232.79
  4755.7  233.62  4777.7  234.34    4794  234.31  4814.6  234.86  4835.9  234.72
  4860.7  235.18    4878  235.09  4904.9  235.79  4925.7  236.01  4948.4  235.96
  4961.6  235.71  4968.6  235.06  4988.6  232.44  4995.7  232.03  4998.4  231.53
  5001.7  232.03  5008.7  232.47  5018.7  232.67  5038.8  232.23  5058.9  232.85
  5072.8  234.49    5079  235.92    5089  236.88  5098.5  237.39  5102.9  237.39
#Mann= 4 ,-1 , 0
    4682     .05       0  4860.7     .16       0  4995.7     .07       0
  5001.7     .16       0
Bank Sta=4995.7,5001.7
XS Rating Curve= 0 ,0
Exp/Cntr=0.3,0.1

Type RM Length L Ch R = 1 ,3143    ,459,459,459
BEGIN DESCRIPTION:
Mapping XS 995fb44a
END DESCRIPTION:
XS GIS Cut Line= 6
      3587671.07     10220924.12      3587786.58      10220897.6
      3587819.13     10220866.35      3587842.57     10220797.34
      3587858.19     10220732.23      3587872.51     10220560.41
#Sta/Elev= 30
    4609  236.13  4612.1  236.13  4630.6  232.88  4639.1  231.98  4687.1  230.92
  4702.4  231.25  4727.5  230.88  4735.5  231.41  4742.7  231.09  4749.7  231.39
  4771.7  230.92  4795.4  232.06  4800.7  231.27  4819.9  232.04  4826.8  232.64
  4832.1  230.95  4840.6  231.47  4860.7  231.89  4862.9   230.3  4865.6   229.8
  4868.9   230.3  4892.5  231.31  4902.7  232.19  4907.9  231.01  4933.1  232.01
  4963.2  231.77  5019.1  232.11  5043.5  235.96  5053.6   236.7  5084.9     238
#Mann= 4 ,-1 , 0
    4609     .05       0  4771.7     .16       0  4862.9     .07       0
  4868.9     .16       0
Bank Sta=4862.9,4868.9
XS Rating Curve= 0 ,0
Exp/Cntr=0.3,0.1

Type RM Length L Ch R = 1 ,2684    ,469,469,469
BEGIN DESCRIPTION:
UNT05324 IN WICK 5.0
END DESCRIPTION:
XS GIS Cut Line= 3
      3587551.09     10221309.84      3587832.34     10221132.76
      3588242.09     10220741.66
#Sta/Elev= 30
  4538.6  238.04  4581.7  235.28  4587.6  236.34  4639.3  235.13  4748.8  229.47
    4770  230.29  4785.3  228.46  4791.2   229.6  4806.5  228.04  4827.7  228.92
  4864.2  226.94  4892.8  228.14  4928.1  225.58  4969.9  226.43  4977.8  225.24
  4984.7  226.11  4988.9   224.6  4991.7   224.1  4994.9   224.6  5006.1  226.26
    5013  225.45  5020.2  227.19  5082.4   226.5  5120.4  226.88  5140.4  226.24
  5225.3  228.24  5324.4  233.84  5352.7  233.95  5424.8  237.29  5437.4  238.33
#Mann= 7 ,-1 , 0
  4538.6     .05       0  4969.9     .16       0  4988.9     .07       0
  4994.9     .16       0  5082.4     .05       0  5120.4     .16       0
  5424.8     .05       0
Bank Sta=4988.9,4994.9
XS Rating Curve= 0 ,0
Exp/Cntr=0.3,0.1

Type RM Length L Ch R = 1 ,2215    ,235,235,235
BEGIN DESCRIPTION:
UNT05324 IN WICK 4.0
END DESCRIPTION:
XS GIS Cut Line= 3
       3588042.1     10221541.65      3588192.11     10221391.64
       3588342.1     10220791.65
#Sta/Elev= 30
  4765.7  233.82  4808.1   232.5  4836.4  230.63  4864.7  230.06  4907.1  227.72
  4949.6  224.37  4963.7  223.84  4974.3  224.59  4980.4  224.59  4988.1  223.34
  4992.9  221.99  4995.6  221.49  4998.9  221.99    5001  223.03  5008.8  223.97
  5029.4     224  5042.3  224.78  5111.8  224.19  5124.7  223.64  5173.7   223.8
  5307.7  225.67  5330.9  226.48  5372.1  227.32  5472.6  231.66  5495.8  232.12
  5503.5  232.91  5523.2  234.09  5555.1  235.89  5578.3  236.59  5596.3  237.72
#Mann= 4 ,-1 , 0
  4765.7     .05       0  4992.9    .035       0  4998.9     .05       0
  5523.2     .16       0
Bank Sta=4992.9,4998.9
XS Rating Curve= 0 ,0
Exp/Cntr=0.3,0.1

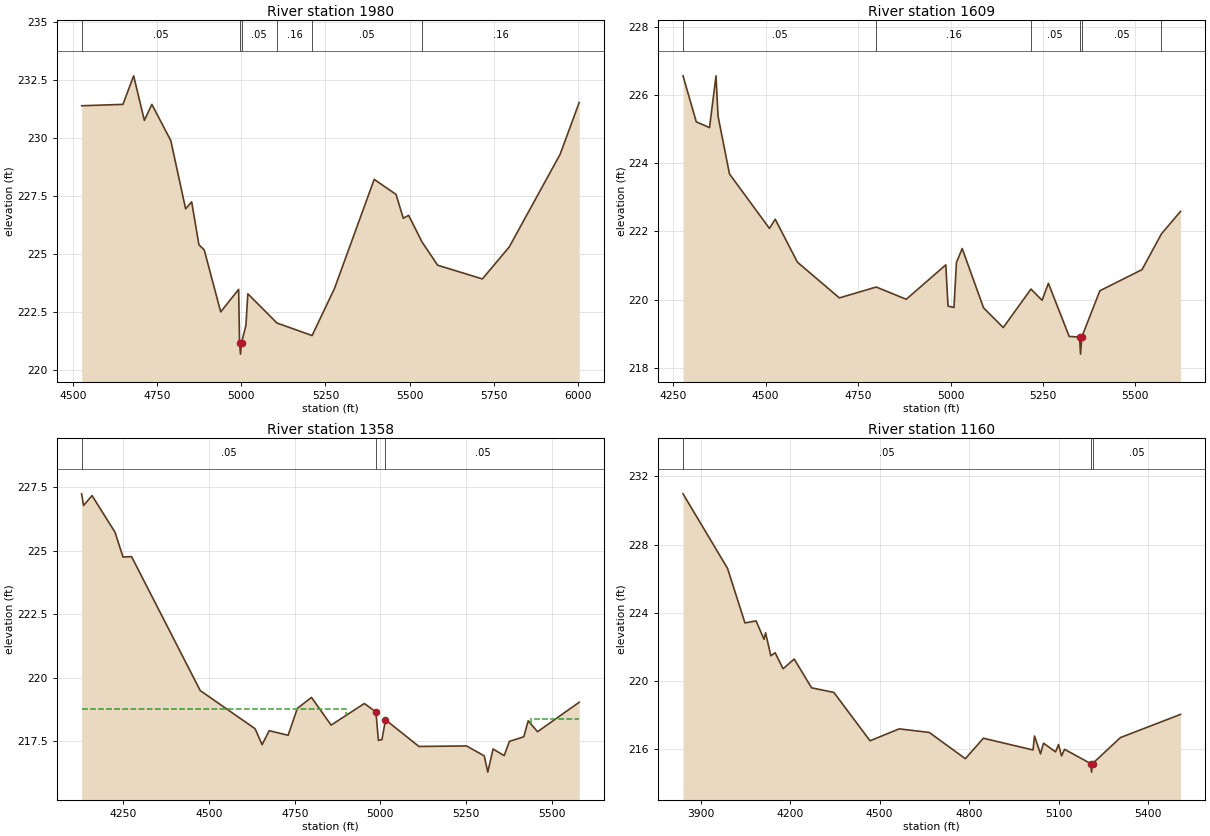
Type RM Length L Ch R = 1 ,1980    ,371,371,371
BEGIN DESCRIPTION:
UNT05324 IN WICK 3.0
END DESCRIPTION:
XS GIS Cut Line= 4
      3587976.49     10221785.43      3588268.19     10221681.25
       3588691.8      10220938.2       3588650.2     10220626.13
#Sta/Elev= 30
  4524.8  231.39  4647.6  231.45  4679.4  232.68  4711.3  230.76  4733.6  231.45
  4789.9  229.89    4834  226.95    4852  227.25  4873.6   225.4  4889.4  225.18
  4938.4  222.51  4991.7  223.48  4994.4  221.19  4997.2  220.69  5000.4  221.19
  5013.3  221.92  5019.1  223.29  5105.8  222.03  5210.2  221.49  5276.9  223.52
    5395  228.22  5459.9  227.57  5481.5  226.54  5497.3  226.67  5537.3  225.52
  5583.7  224.52  5716.7  223.93  5796.7  225.31    5948   229.3  6004.7  231.53
#Mann= 6 ,-1 , 0
  4524.8     .05       0  4994.4    .035       0  5000.4     .05       0
  5105.8     .16       0  5210.2     .05       0  5537.3     .16       0
Bank Sta=4994.4,5000.4
XS Rating Curve= 0 ,0
Exp/Cntr=0.3,0.1

Type RM Length L Ch R = 1 ,1609    ,251,251,251
BEGIN DESCRIPTION:
Mapping XS 503ec909
END DESCRIPTION:
XS GIS Cut Line= 4
      3588175.81     10221991.05      3588514.31     10221852.17
      3588813.79     10221231.52      3588737.41     10220951.14
#Sta/Elev= 30
  4276.5  226.57  4312.4  225.22  4348.2  225.05  4365.8  226.57  4371.2  225.39
  4402.2  223.69  4510.3  222.09  4525.9  222.36  4585.9   221.1  4699.4  220.05
    4799  220.37  4880.3  220.01  4987.2  221.02  4993.3  219.81  5009.4  219.77
    5016  221.09  5031.6   221.5  5089.3  219.76  5142.6  219.18  5217.6  220.31
  5247.6  219.98  5264.7  220.48    5321  218.92  5348.9   218.9  5351.7   218.4
  5354.9   218.9  5403.9  220.26  5517.9  220.88  5570.4  221.93  5622.1  222.59
#Mann= 6 ,-1 , 0
  4276.5     .05       0    4799     .16       0  5217.6     .05       0
  5348.9     .07       0  5354.9     .05       0  5570.4     .16       0
Bank Sta=5348.9,5354.9
XS Rating Curve= 0 ,0
Exp/Cntr=0.3,0.1

Type RM Length L Ch R = 1 ,1358    ,198,198,198
BEGIN DESCRIPTION:
Mapping XS b1516c1d
END DESCRIPTION:
XS GIS Cut Line= 4
      3588371.09     10222108.25      3588818.13     10221938.98
      3588978.72     10221274.92      3588891.93     10220997.18
#Sta/Elev= 30
  4128.2  227.23  4133.7  226.77  4158.5  227.16  4225.5  225.72    4249  224.74
  4273.8  224.76  4474.2  219.49  4634.3  217.99  4654.9  217.36  4675.5  217.91
  4730.8  217.73  4757.8  218.79    4799  219.22  4856.3  218.13  4953.3  218.98
    4987  218.65  4994.4  217.53  5004.7  217.56    5015  218.34  5112.6  217.29
  5251.6  217.31  5303.3  216.92  5313.6  216.28  5328.9  217.19  5361.4  216.93
  5376.7  217.49  5418.6  217.67  5431.6   218.3  5458.9  217.87  5580.4  219.03
#Mann= 3 , 0 , 0
  4128.2     .05       0    4987     .03       0    5015     .05       0
#XS Ineff= 2 , 0
            4900  218.75 5439.09          218.39
Permanent Ineff=
       F       F
#Block Obstruct= 2 , 0
                         5005.02          217.56
Bank Sta=4987,5015
XS Rating Curve= 0 ,0
Exp/Cntr=0.3,0.1

Type RM Length L Ch R = 1 ,1160    ,0,0,0
BEGIN DESCRIPTION:
UNT05324 IN WICK 1.0
END DESCRIPTION:
XS GIS Cut Line= 4
      3588442.08     10222241.65      3589039.48     10222047.49
      3589134.97      10221283.6      3588986.54      10221058.3
#Sta/Elev= 30
  3840.8  230.98  3989.9  226.61  4048.5   223.4  4085.7  223.52  4112.4  222.44
  4117.6  222.82  4135.2  221.47  4149.6  221.65  4176.3  220.71  4213.5  221.28
  4271.9  219.59  4346.5  219.32  4467.7  216.48  4565.6  217.18  4666.3  216.97
  4787.3  215.43  4847.7  216.63  5014.1  215.94  5019.1  216.76  5039.2  215.71
  5049.3  216.34  5089.6  215.83  5099.7  216.26  5109.8  215.59  5119.8  215.98
  5207.5  215.14  5210.3  214.64  5213.5  215.14  5307.3  216.67  5508.6  218.03
#Mann= 3 ,-1 , 0
  3840.8     .05       0  5207.5     .03       0  5213.5     .05       0
Bank Sta=5207.5,5213.5
XS Rating Curve= 0 ,0
Exp/Cntr=0.3,0.1

Chan Stop Cuts=-1
Use User Specified Reach Order=0
Composite Channel Slope=5