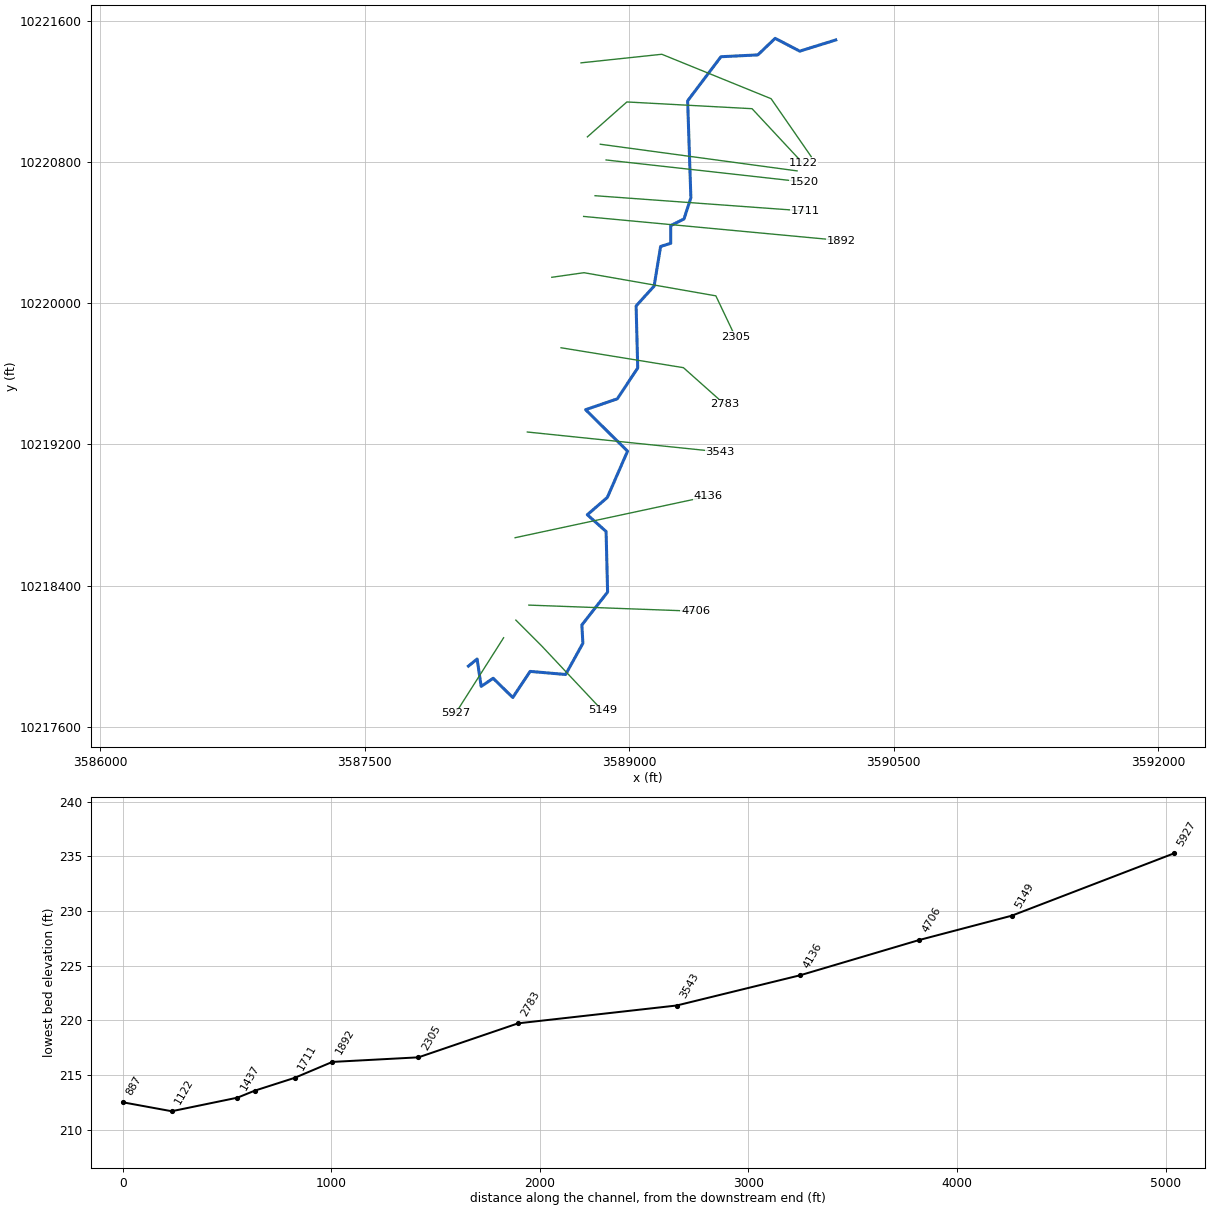
--- BRUSHYCREEKTRIB2.prj (project) ---

Proj Title=BRUSHY CREEK TRIB 2
Current Plan=p01
Default Exp/Contr=0.3,0.1
English Units
Geom File=g01
Flow File=f01
Plan File=p01
Y Axis Title=Elevation
X Axis Title(PF)=Main Channel Distance
X Axis Title(XS)=Station
BEGIN DESCRIPTION:
UNT05323 IN WICK
END DESCRIPTION:
DSS Export Rating Curves= 0
DSS Export Rating Curve Sorted= 0
DSS Export Volume Flow Curves= 0
DXF OffsetX= 0
DXF OffsetY= 0
DXF ScaleX= 1
DXF ScaleY= 10

--- BRUSHYCREEKTRIB2.p01 (plan) ---

Plan Title=Multiple Run
Short Identifier=Multiple
Geom File=g01
Flow File=f01
Subcritical Flow
K Sum by GR= 0
Std Step Tol= 0.01
Critical Tol= 0.01
Num of Std Step Trials= 20
Max Error Tol= 0.3
Flow Tol Ratio= 0.001
Split Flow NTrial= 30
Split Flow Tol= 0.02
Split Flow Ratio= 0.02
Log Output Level= 0
Friction Slope Method= 1
Unsteady Friction Slope Method= 2
Unsteady Bridges Friction Slope Method= 1
Parabolic Critical Depth
Global Vel Dist=  1 , 1 , 1
Global Log Level= 0
CheckData=True
Encroach Param= -1, 0, 0, 0
BEGIN DESCRIPTION:
Multiple Run
END DESCRIPTION:

--- BRUSHYCREEKTRIB2.f01 (steady flow) ---

Flow Title=Multiple
Program Version=4.10
Number of Profiles= 7
Profile Names=10-year,25-year,50-year,1pct_min,100-year,1pct_plu,500-year
River Rch & RM=UNT05323 IN WICK,Reach-1         ,5927
     397     523     623     545     737     997    1032
River Rch & RM=BRUSHYCRTR2,Reach-1         ,5927
     397     523     623     545     737     997    1032
Boundary for River Rch & Prof#=BRUSHYCRTR2,Reach-1         , 1
Up Type= 0
Dn Type= 3
Dn Slope=0.005
Boundary for River Rch & Prof#=BRUSHYCRTR2,Reach-1         , 2
Up Type= 0
Dn Type= 3
Dn Slope=0.005
Boundary for River Rch & Prof#=BRUSHYCRTR2,Reach-1         , 3
Up Type= 0
Dn Type= 3
Dn Slope=0.005
Boundary for River Rch & Prof#=BRUSHYCRTR2,Reach-1         , 4
Up Type= 0
Dn Type= 3
Dn Slope=0.005
Boundary for River Rch & Prof#=BRUSHYCRTR2,Reach-1         , 5
Up Type= 0
Dn Type= 3
Dn Slope=0.005
Boundary for River Rch & Prof#=BRUSHYCRTR2,Reach-1         , 6
Up Type= 0
Dn Type= 3
Dn Slope=0.005
Boundary for River Rch & Prof#=BRUSHYCRTR2,Reach-1         , 7
Up Type= 0
Dn Type= 3
Dn Slope=0.005
DSS Import GetInterval= 0
DSS Import GetPeak= 0
DSS Import FillOption= 0

--- BRUSHYCREEKTRIB2.g01 (geometry) ---

Geom Title=Existing Conditions
Program Version=4.10

River Reach=BRUSHYCRTR2     ,Reach-1
Reach XY= 30
      3588088.48     10217943.58      3588137.83     10217983.74
      3588160.81     10217828.45      3588228.73     10217874.53
      3588340.15      10217765.6      3588438.59     10217913.52
      3588639.97       10217896.      3588737.94     10218073.03
      3588731.97     10218176.63      3588878.06     10218363.06
      3588869.39     10218706.41      3588763.03     10218801.16
      3588876.51     10218899.31      3588991.15     10219161.41
      3588753.19     10219396.51      3588933.13     10219458.12
      3589048.93     10219632.93      3589039.75     10219984.72
      3589141.82     10220096.74      3589178.74     10220321.42
      3589236.28     10220339.51      3589236.04     10220439.65
      3589311.38     10220477.32      3589350.46     10220597.39
      3589332.02     10221146.56      3589520.97     10221396.68
      3589730.13     10221406.94      3589828.48     10221500.89
      3589968.09     10221428.25      3590172.11     10221491.64

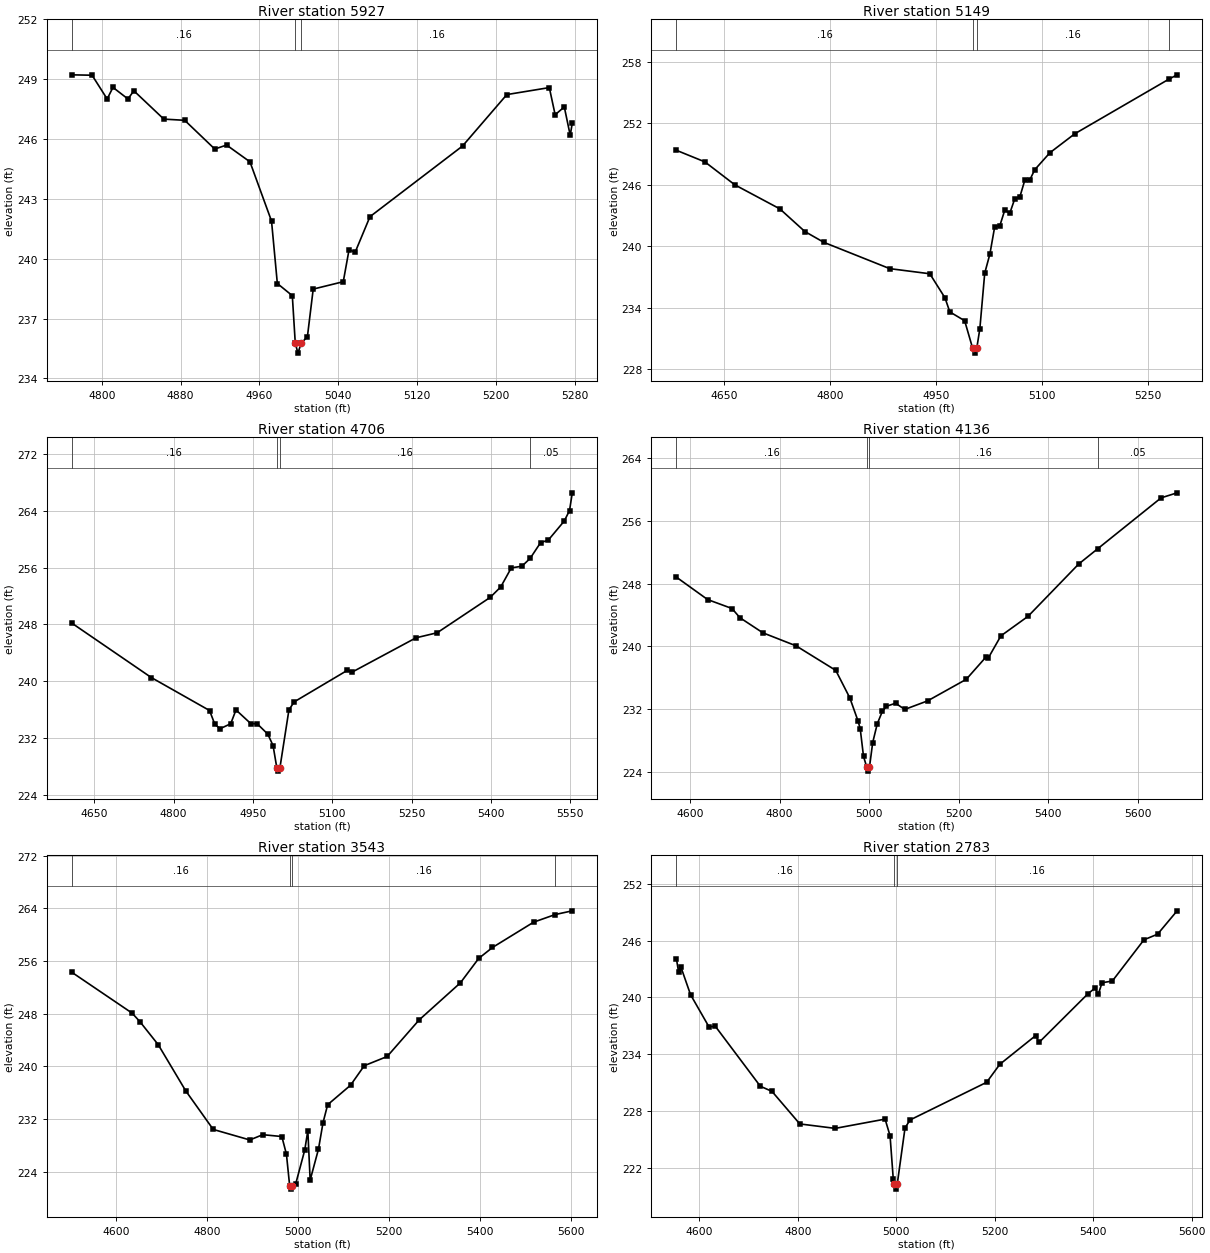
Type RM Length L Ch R = 1 ,5927    ,778,778,778
BEGIN DESCRIPTION:
UNT05323 IN WICK 10.0
END DESCRIPTION:
XS GIS Cut Line= 2
      3588288.22     10218104.32      3588015.44     10217675.66
#Sta/Elev= 30
  4769.4  249.22  4790.2   249.2  4805.5  248.01  4811.4  248.59  4826.6  248.01
  4832.6  248.42    4863     247  4884.2  246.94  4914.7   245.5  4926.7   245.7
  4950.4  244.86  4972.3  241.89  4978.2  238.76  4993.4  238.15  4996.4  235.77
  4999.1  235.27  5002.4  235.77  5008.7  236.09  5014.6  238.48  5045.1  238.85
    5051  240.46  5057.1  240.32  5072.2  242.11  5166.1  245.65  5211.1  248.23
  5254.2  248.58  5260.1  247.22  5269.4  247.61  5275.4  246.19  5277.5   246.8
#Mann= 3 ,-1 , 0
  4769.4     .16       0  4996.4     .07       0  5002.4     .16       0
Bank Sta=4996.4,5002.4
XS Rating Curve= 0 ,0
Exp/Cntr=0.3,0.1

Type RM Length L Ch R = 1 ,5149    ,443,443,443
BEGIN DESCRIPTION:
UNT05323 IN WICK 9.0
END DESCRIPTION:
XS GIS Cut Line= 3
      3588357.69     10218204.17      3588505.25      10218056.6
      3588847.61     10217692.58
#Sta/Elev= 30
  4582.6  249.35  4622.9  248.22  4665.3  245.98  4728.9  243.64  4764.3  241.43
  4791.3  240.37  4884.4  237.81  4941.1  237.31  4962.6  234.96  4969.4  233.59
  4990.4  232.73  5001.6  230.07  5004.4  229.57  5007.6  230.07  5011.9  231.95
  5018.8  237.37  5026.1  239.23  5032.9  241.89  5040.2     242  5047.1   243.5
  5054.4  243.24  5061.3  244.62  5068.6  244.83  5075.4  246.41  5082.7  246.48
  5089.6  247.46    5111  249.11  5146.2  250.96  5278.9  256.27    5291  256.71
#Mann= 4 ,-1 , 0
  4582.6     .16       0  5001.6     .07       0  5007.6     .16       0
  5278.9     .05       0
Bank Sta=5001.6,5007.6
XS Rating Curve= 0 ,0
Exp/Cntr=0.3,0.1

Type RM Length L Ch R = 1 ,4706    ,570,570,570
BEGIN DESCRIPTION:
UNT05323 IN WICK 8.0
END DESCRIPTION:
XS GIS Cut Line= 2
      3588431.48     10218289.17      3589377.34     10218254.46
#Sta/Elev= 30
  4607.2   248.2  4757.9  240.52    4868  235.88    4878  233.94    4888  233.32
    4908  234.02    4918  235.96  4945.9  234.04  4958.1  234.01  4978.1  232.56
  4988.1  230.94  4995.1  227.85  4997.8  227.35  5001.1  227.85  5018.1  235.98
  5028.1   237.1  5128.2  241.52  5138.2  241.31  5258.3  246.11  5298.3  246.82
  5398.4  251.79  5418.4  253.26  5438.4  255.95  5458.4  256.18    5474  257.28
  5493.8   259.5  5508.4  259.86  5538.5  262.54  5548.5  264.02  5553.7  266.51
#Mann= 4 ,-1 , 0
  4607.2     .16       0  4995.1     .07       0  5001.1     .16       0
    5474     .05       0
Bank Sta=4995.1,5001.1
XS Rating Curve= 0 ,0
Exp/Cntr=0.3,0.1

Type RM Length L Ch R = 1 ,4136    ,593,593,593
BEGIN DESCRIPTION:
UNT05323 IN WICK 7.0
END DESCRIPTION:
XS GIS Cut Line= 2
      3588353.34     10218671.11      3589447.11     10218905.49
#Sta/Elev= 30
  4569.3  248.81    4639  245.96  4693.5  244.82  4711.2  243.65  4762.4  241.73
  4836.7  240.07  4925.3  236.95  4956.7  233.45  4974.8  230.55  4979.9  229.54
  4987.3     226  4994.6  224.63  4997.3  224.13  5000.6  224.63  5007.8  227.76
    5018  230.15  5029.3  231.72  5038.5  232.38  5058.9  232.77  5079.4  231.98
  5130.5  233.07  5216.8  235.81  5261.1  238.66  5266.2  238.54  5294.2  241.34
  5354.9  243.83    5468  250.48  5510.6  252.43  5652.1   258.9  5687.9  259.54
#Mann= 4 ,-1 , 0
  4569.3     .16       0  4994.6     .07       0  5000.6     .16       0
  5510.6     .05       0
Bank Sta=4994.6,5000.6
XS Rating Curve= 0 ,0
Exp/Cntr=0.3,0.1

Type RM Length L Ch R = 1 ,3543    ,760,760,760
BEGIN DESCRIPTION:
UNT05323 IN WICK 6.0
END DESCRIPTION:
XS GIS Cut Line= 2
       3588422.8     10219270.07      3589516.49     10219157.23
#Sta/Elev= 30
  4502.5  254.33  4635.4   248.1  4652.6   246.8  4692.8   243.3  4753.1   236.3
  4813.5  230.43  4893.9  228.83  4922.3  229.63  4964.2  229.35  4974.3  226.67
  4981.4  221.86  4984.1  221.36  4987.4  221.86  4994.4  222.09  5014.5  227.29
  5021.3  230.25  5026.4  222.73  5044.7  227.45  5054.7  231.47  5064.8  234.18
    5115  237.14  5145.2  240.11  5195.5  241.51  5265.8  247.07  5356.3   252.7
  5396.5  256.41  5426.7  258.07  5517.2  261.92  5564.7  263.08    5602  263.64
#Mann= 4 ,-1 , 0
  4502.5     .16       0  4981.4     .07       0  4987.4     .16       0
  5564.7     .05       0
Bank Sta=4981.4,4987.4
XS Rating Curve= 0 ,0
Exp/Cntr=0.3,0.1

Type RM Length L Ch R = 1 ,2783    ,478,478,478
BEGIN DESCRIPTION:
UNT05323 IN WICK 4.0
END DESCRIPTION:
XS GIS Cut Line= 3
      3588613.79      10219747.5       3589308.2     10219634.66
      3589542.42     10219426.46
#Sta/Elev= 30
  4553.6  244.08    4558  242.68    4563  243.16  4582.3  240.28  4619.5   236.9
  4632.9  236.92  4724.1   230.6  4747.7  230.06  4804.2  226.62  4876.1  226.15
  4977.4  227.13  4987.5  225.37    4994  220.81    4996  220.23  4998.8  219.73
    5002  220.23  5017.9   226.2  5028.1  227.04  5183.7  231.02  5210.4  232.92
  5283.3  235.96    5290  235.23  5389.5  240.38  5403.7  240.97  5410.4  240.31
    5418  241.54  5438.9  241.72  5503.2  246.08  5530.8  246.67  5570.5  249.14
#Mann= 3 ,-1 , 0
  4553.6     .16       0    4996     .07       0    5002     .16       0
Bank Sta=4996,5002
XS Rating Curve= 0 ,0
Exp/Cntr=0.3,0.1

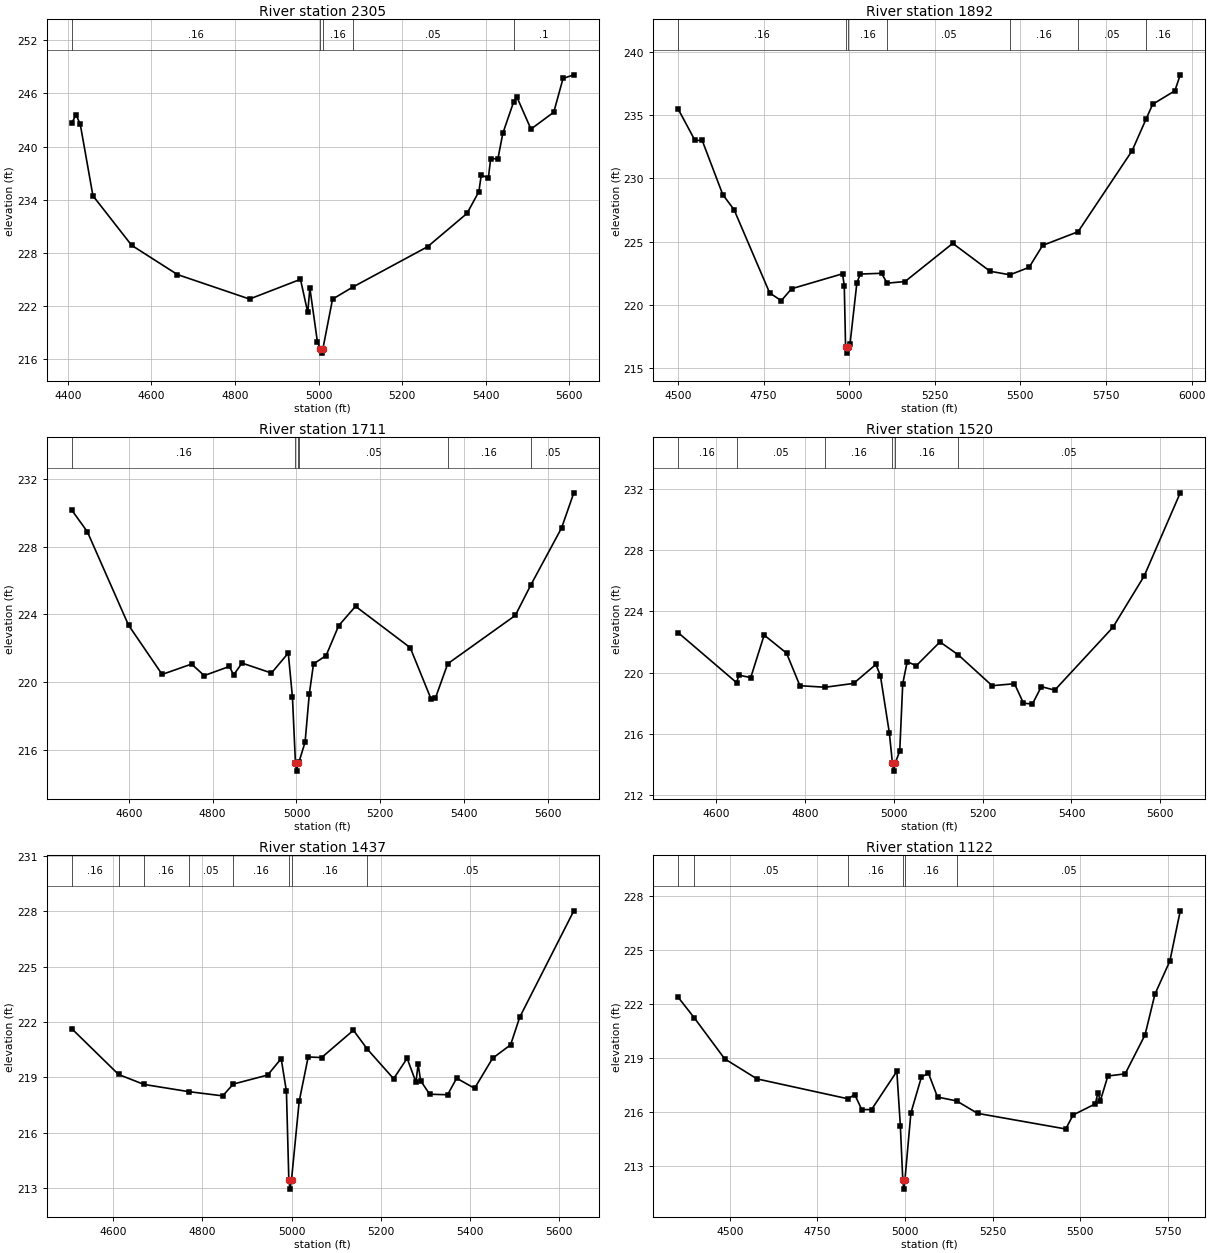
Type RM Length L Ch R = 1 ,2305    ,413,413,413
BEGIN DESCRIPTION:
UNT05323 IN WICK 3.0
END DESCRIPTION:
XS GIS Cut Line= 4
      3588561.66     10220146.81      3588743.97     10220172.85
      3589492.11     10220041.64      3589603.32     10219808.31
#Sta/Elev= 30
    4409  242.63  4419.6   243.6  4429.7  242.49    4460  234.42  4552.6  228.82
  4662.3  225.51  4834.9  222.74  4956.8  224.97  4974.2  221.23  4979.3  223.98
  4997.4  217.88  5004.5  217.12  5007.3  216.62  5010.5  217.12  5033.6  222.73
  5082.3   224.1  5261.1  228.66  5355.5  232.43    5384   234.9  5389.5  236.75
  5406.7  236.47  5412.2  238.64  5429.4  238.59  5441.3   241.5  5467.1  245.04
  5474.6  245.63  5508.6  241.97  5563.2  243.88  5585.4   247.7  5611.2  248.11
#Mann= 5 ,-1 , 0
    4409     .16       0  5004.5     .07       0  5010.5     .16       0
  5082.3     .05       0  5467.1      .1       0
Bank Sta=5004.5,5010.5
XS Rating Curve= 0 ,0
Exp/Cntr=0.3,0.1

Type RM Length L Ch R = 1 ,1892    ,181,181,181
BEGIN DESCRIPTION:
UNT05323 IN WICK 2.0
END DESCRIPTION:
XS GIS Cut Line= 2
      3588742.13     10220491.64      3590202.27     10220355.15
#Sta/Elev= 30
  4500.3  235.47  4549.7  232.98  4570.6  232.99  4630.8  228.71  4663.7  227.52
  4767.7  220.95  4801.6  220.34  4831.7  221.28  4980.5  222.46  4985.6  221.53
  4989.4   216.7  4992.2   216.2  4995.4   216.7  5002.5  216.95  5022.5  221.76
  5032.6  222.44  5094.5   222.5  5110.8  221.72  5163.1  221.85  5302.4  224.86
  5411.4  222.66  5469.4  222.38  5525.4  222.97  5564.9   224.7  5668.4  225.78
    5826  232.16  5867.5   234.7  5886.3  235.84  5951.1   236.9  5966.8  238.16
#Mann= 7 ,-1 , 0
  4500.3     .16       0  4989.4     .07       0  4995.4     .16       0
  5110.8     .05       0  5469.4     .16       0  5668.4     .05       0
  5867.5     .16       0
Bank Sta=4989.4,4995.4
XS Rating Curve= 0 ,0
Exp/Cntr=0.3,0.1

Type RM Length L Ch R = 1 ,1711    ,191,191,191
BEGIN DESCRIPTION:
Mapping XS aac67694
END DESCRIPTION:
XS GIS Cut Line= 2
      3588806.86     10220609.13      3590001.31     10220522.32
#Sta/Elev= 30
  4463.8  230.16  4501.1  228.88  4599.4  223.36  4679.6  220.45  4749.8  221.06
  4779.9  220.38    4840  220.92  4850.1  220.42  4870.1  221.12  4940.3  220.53
  4980.4  221.71  4990.4  219.09  4997.5  215.24  5000.2  214.74  5003.5  215.24
  5005.8  215.27  5020.5  216.45  5030.5  219.28  5040.6  221.07  5070.6  221.56
  5100.7  223.33  5140.8  224.47  5271.2  222.03  5321.1  218.99  5331.3  219.05
  5360.7  221.08  5521.8  223.93  5559.3  225.75  5632.1  229.09  5661.4  231.17
#Mann= 6 ,-1 , 0
  4463.8     .16       0  4997.5     .07       0  5003.5     .16       0
  5005.8     .05       0  5360.7     .16       0  5559.3     .05       0
Bank Sta=4997.5,5003.5
XS Rating Curve= 0 ,0
Exp/Cntr=0.3,0.1

Type RM Length L Ch R = 1 ,1520    ,83,83,83
BEGIN DESCRIPTION:
Mapping XS e80d886d
END DESCRIPTION:
XS GIS Cut Line= 2
      3588869.62     10220811.65      3589992.88     10220686.65
#Sta/Elev= 30
  4514.6  222.62  4646.2  219.35  4651.6  219.84  4678.1  219.68  4708.3  222.46
  4758.6  221.28  4788.8  219.15  4845.7  219.05  4909.5   219.3  4959.8  220.54
  4969.9  219.81    4990  216.08  4997.1  214.07  4999.8  213.57  5003.1  214.07
  5013.5   214.9  5020.2  219.28  5030.3  220.73  5050.4  220.45    5104  222.01
    5145  221.17  5221.4  219.15  5271.7  219.28  5291.9  218.01    5312  217.95
  5332.1  219.09  5362.3  218.86  5493.1  222.96  5563.5  226.31  5644.8  231.75
#Mann= 6 ,-1 , 0
  4514.6     .16       0  4646.2     .05       0  4845.7     .16       0
  4997.1     .07       0  5003.1     .16       0    5145     .05       0
Bank Sta=4997.1,5003.1
XS Rating Curve= 0 ,0
Exp/Cntr=0.3,0.1

Type RM Length L Ch R = 1 ,1437    ,315,315,315
BEGIN DESCRIPTION:
Mapping XS 22dd5180
END DESCRIPTION:
XS GIS Cut Line= 2
      3588836.34      10220900.8      3589952.67     10220749.76
#Sta/Elev= 30
  4506.5  221.64  4611.8  219.15  4668.8  218.61    4769  218.22  4845.3  217.99
  4869.1  218.63  4946.2  219.12  4976.5  220.01  4988.3  218.24  4993.7  213.43
  4996.4  212.93  4999.7  213.43  5016.9  217.69  5037.1   220.1  5067.3  220.07
  5138.6  221.55  5169.6  220.53  5228.8  218.92  5259.1  220.03  5278.8  218.73
  5283.8  219.71  5289.3  218.82  5309.5  218.08  5349.9  218.05  5370.1  218.95
  5410.4   218.4  5450.8  220.03  5491.2  220.76  5511.7  222.26    5633  228.03
#Mann= 8 ,-1 , 0
  4506.5     .16       0  4611.8     .05       0  4668.8     .16       0
    4769     .05       0  4869.1     .16       0  4993.7     .07       0
  4999.7     .16       0  5169.6     .05       0
Bank Sta=4993.7,4999.7
XS Rating Curve= 0 ,0
Exp/Cntr=0.3,0.1

Type RM Length L Ch R = 1 ,1122    ,235,235,235
BEGIN DESCRIPTION:
Mapping XS 1b6feffd
END DESCRIPTION:
XS GIS Cut Line= 4
      3588763.47     10220942.48      3588987.41     10221140.38
      3589697.48     10221102.19      3589985.67     10220793.16
#Sta/Elev= 30
  4352.7  222.38  4398.5  221.24  4485.4  218.95  4577.7  217.83  4837.5  216.72
  4856.5  216.96  4876.6  216.12  4904.5  216.12  4976.7  218.25  4986.7  215.23
  4993.7  212.19  4996.5  211.69  4999.7  212.19  5016.8  215.93  5046.8  217.93
  5066.8  218.15  5092.7  216.82  5147.4   216.6    5207  215.91  5458.5  215.04
  5479.5  215.82    5543  216.44  5550.3  217.07  5557.2  216.61  5578.7  217.99
    5628  218.11  5684.7  220.28    5713  222.55  5755.5  224.39  5785.2  227.19
#Mann= 6 ,-1 , 0
  4352.7     .16       0  4398.5     .05       0  4837.5     .16       0
  4993.7     .07       0  4999.7     .16       0  5147.4     .05       0
Bank Sta=4993.7,4999.7
XS Rating Curve= 0 ,0
Exp/Cntr=0.3,0.1

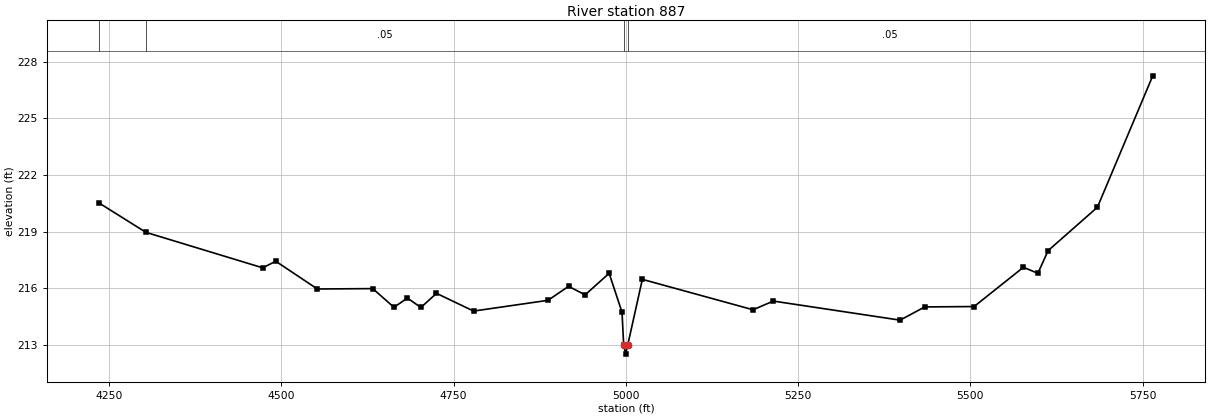
Type RM Length L Ch R = 1 ,887     ,0,0,0
BEGIN DESCRIPTION:
UNT05323 IN WICK 1.0
END DESCRIPTION:
XS GIS Cut Line= 4
      3588727.31     10221361.99      3589185.64      10221410.6
      3589805.43     10221158.86      3590032.86     10220830.74
#Sta/Elev= 30
  4235.6  220.51  4303.4  218.96    4473  217.08  4491.8  217.43  4552.2  215.96
  4632.6  215.98  4663.4  214.99  4682.9  215.48  4702.5  214.98  4725.1  215.73
    4779  214.79    4887  215.36  4916.8   216.1  4940.9  215.65  4975.7  216.79
  4994.4  214.73  4996.8  213.01  4999.6  212.51  5002.8  213.01  5023.9  216.47
  5184.6  214.86    5214  215.32    5398  214.31  5433.8  215.01  5505.4  215.03
    5577  217.11    5598  216.79  5612.8  217.99  5684.4  220.29  5764.7  227.25
#Mann= 4 ,-1 , 0
  4235.6     .16       0  4303.4     .05       0  4996.8    .035       0
  5002.8     .05       0
Bank Sta=4996.8,5002.8
XS Rating Curve= 0 ,0
Exp/Cntr=0.3,0.1

Chan Stop Cuts=-1
Use User Specified Reach Order=0
Composite Channel Slope=5