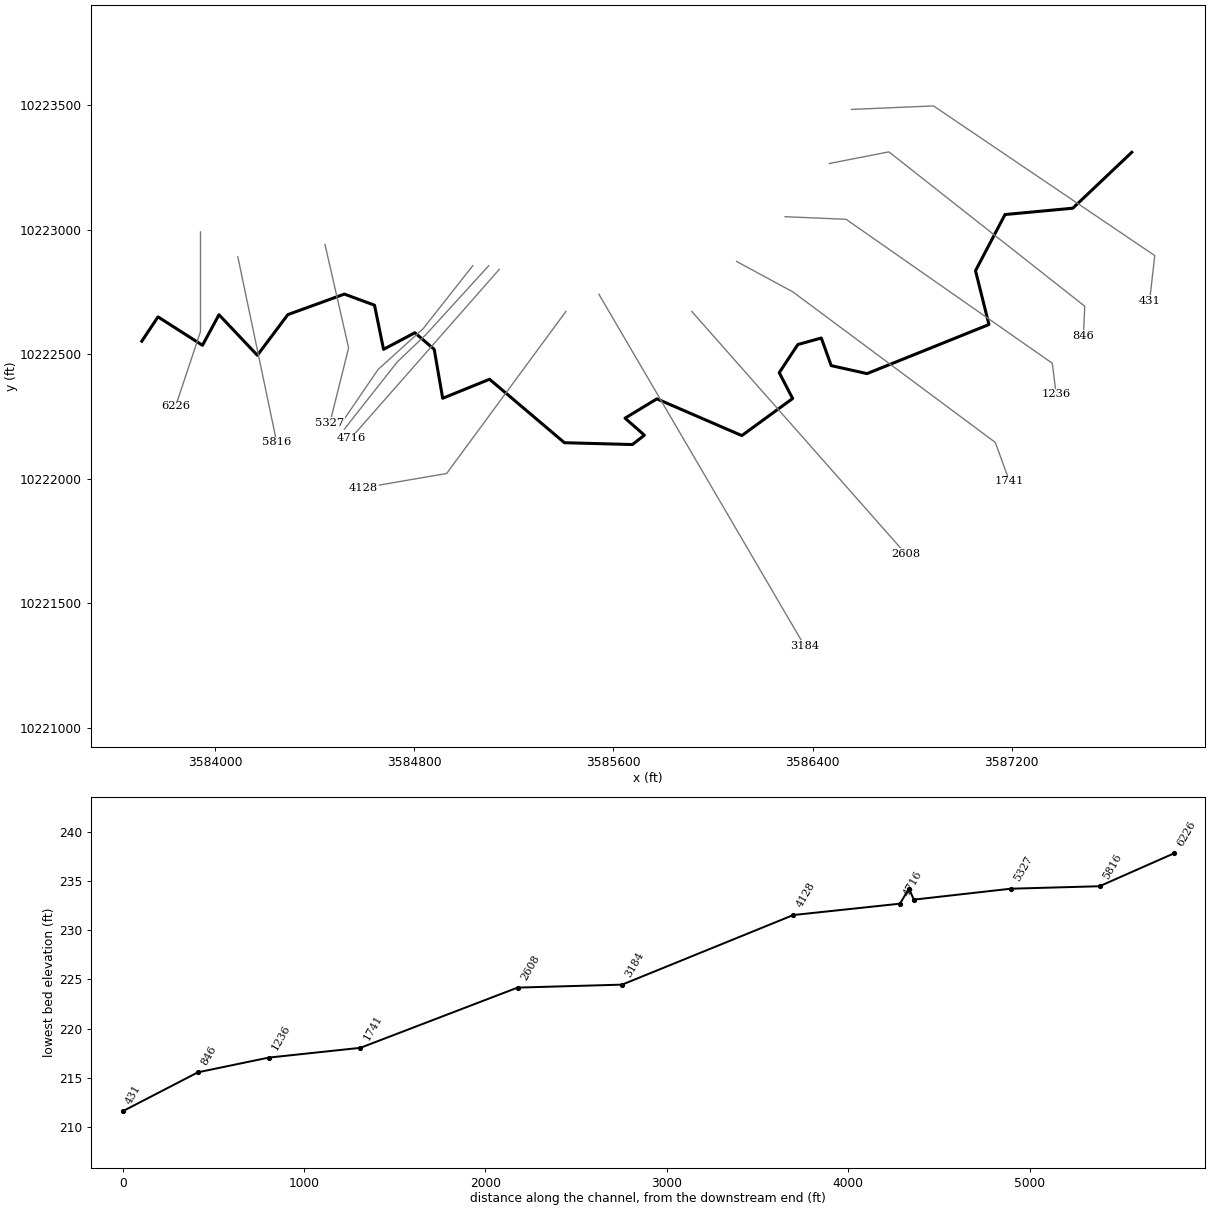
--- BRUSHYCREEKTRIB4.prj (project) ---

Proj Title=BRUSHY CREEK TRIB 4
Current Plan=p01
Default Exp/Contr=0.3,0.1
English Units
Geom File=g01
Flow File=f01
Plan File=p01
Y Axis Title=Elevation
X Axis Title(PF)=Main Channel Distance
X Axis Title(XS)=Station
BEGIN DESCRIPTION:
UNT0511 IN WICK
END DESCRIPTION:
DSS Export Rating Curves= 0
DSS Export Rating Curve Sorted= 0
DSS Export Volume Flow Curves= 0
DXF OffsetX= 0
DXF OffsetY= 0
DXF ScaleX= 1
DXF ScaleY= 10

--- BRUSHYCREEKTRIB4.p01 (plan) ---

Plan Title=Multiple Run
Short Identifier=Multiple
Geom File=g01
Flow File=f01
Subcritical Flow
K Sum by GR= 0
Std Step Tol= 0.01
Critical Tol= 0.01
Num of Std Step Trials= 20
Max Error Tol= 0.3
Flow Tol Ratio= 0.001
Split Flow NTrial= 30
Split Flow Tol= 0.02
Split Flow Ratio= 0.02
Log Output Level= 0
Friction Slope Method= 1
Unsteady Friction Slope Method= 2
Unsteady Bridges Friction Slope Method= 1
Parabolic Critical Depth
Global Vel Dist=  1 , 1 , 1
Global Log Level= 0
CheckData=True
Encroach Param= -1, 0, 0, 0
BEGIN DESCRIPTION:
Multiple Run
END DESCRIPTION:

--- BRUSHYCREEKTRIB4.f01 (steady flow) ---

Flow Title=Multiple
Program Version=4.10
Number of Profiles= 7
Profile Names=10-year,25-year,50-year,1pct_min,100-year,1pct_plu,500-year
River Rch & RM=UNT0511 IN WICK,Reach-1         ,6226
     687     936    1140    1019    1377    1863    2014
River Rch & RM=UNT0511 IN WICK,Reach-1         ,3184
     731     998    1218    1089    1473    1992    2159
River Rch & RM=BRUSHYCRTR4,Reach-1         ,6226
     687     936    1140    1019    1377    1863    2014
River Rch & RM=BRUSHYCRTR4,Reach-1         ,3184
     731     998    1218    1089    1473    1992    2159
Boundary for River Rch & Prof#=BRUSHYCRTR4,Reach-1         , 1
Up Type= 0
Dn Type= 3
Dn Slope=0.005
Boundary for River Rch & Prof#=BRUSHYCRTR4,Reach-1         , 2
Up Type= 0
Dn Type= 3
Dn Slope=0.005
Boundary for River Rch & Prof#=BRUSHYCRTR4,Reach-1         , 3
Up Type= 0
Dn Type= 3
Dn Slope=0.005
Boundary for River Rch & Prof#=BRUSHYCRTR4,Reach-1         , 4
Up Type= 0
Dn Type= 3
Dn Slope=0.005
Boundary for River Rch & Prof#=BRUSHYCRTR4,Reach-1         , 5
Up Type= 0
Dn Type= 3
Dn Slope=0.005
Boundary for River Rch & Prof#=BRUSHYCRTR4,Reach-1         , 6
Up Type= 0
Dn Type= 3
Dn Slope=0.005
Boundary for River Rch & Prof#=BRUSHYCRTR4,Reach-1         , 7
Up Type= 0
Dn Type= 3
Dn Slope=0.005
DSS Import GetInterval= 0
DSS Import GetPeak= 0
DSS Import FillOption= 0

--- BRUSHYCREEKTRIB4.g01 (geometry) ---

Geom Title=Existing Conditions
Program Version=4.10

River Reach=BRUSHYCRTR4     ,Reach-1
Reach XY= 30
      3583706.49     10222553.03      3583771.46     10222650.76
      3583950.13     10222536.54      3584016.37     10222659.37
      3584170.46     10222496.45      3584292.92     10222659.77
      3584519.86     10222742.18      3584641.04     10222697.57
      3584677.23     10222520.31      3584802.93     10222586.98
      3584880.71     10222520.31      3584914.73     10222323.78
      3585102.93     10222400.17      3585403.66     10222145.39
      3585676.74     10222138.01       3585724.8     10222175.62
      3585647.11      10222243.9       3585774.8      10222321.5
      3586116.02     10222173.97      3586320.14     10222322.92
      3586266.23     10222426.55        3586341.     10222539.63
      3586435.21     10222565.92      3586474.98     10222454.94
      3586618.96     10222422.84      3587108.45      10222619.9
      3587054.49     10222836.08      3587173.05     10223061.69
       3587445.1     10223087.09      3587682.11     10223311.64

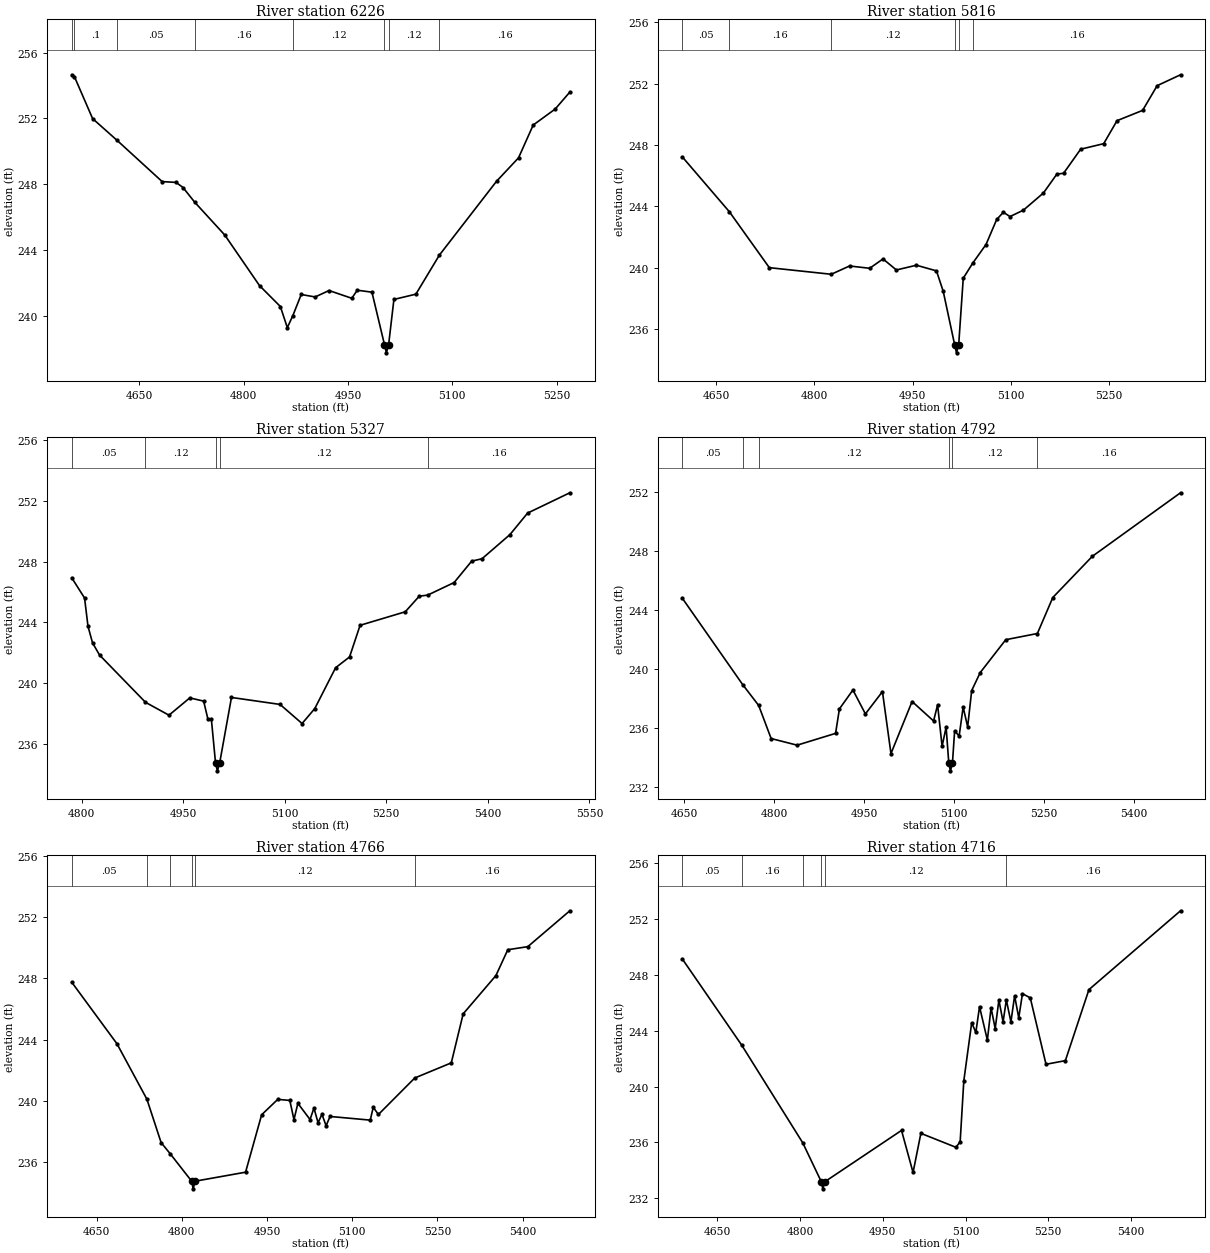
Type RM Length L Ch R = 1 ,6226    ,410,410,410
BEGIN DESCRIPTION:
UNT0511 IN WICK 11.0
END DESCRIPTION:
XS GIS Cut Line= 3
      3583942.11     10222991.68      3583942.11     10222591.64
      3583842.09     10222291.61
#Sta/Elev= 30
  4552.7  254.65  4556.6  254.53  4582.7  251.99  4617.9  250.67  4682.7  248.17
  4702.7  248.12  4712.7  247.81  4729.5  246.92  4772.7  244.93  4822.7  241.86
  4852.7  240.59  4862.7  239.31  4870.7  240.04  4882.7  241.32  4902.7  241.17
  4922.7  241.56  4955.4  241.09  4963.3  241.58  4984.4  241.46  5002.4  238.28
  5005.2  237.78  5008.4  238.28    5016  241.02  5047.6  241.34  5081.4  243.71
  5163.6  248.19  5195.2  249.61  5216.3   251.6  5247.9  252.57    5269   253.6
#Mann= 8 ,-1 , 0
  4552.7     .05       0  4556.6      .1       0  4617.9     .05       0
  4729.5     .16       0  4870.7     .12       0  5002.4     .07       0
  5008.4     .12       0  5081.4     .16       0
Bank Sta=5002.4,5008.4
XS Rating Curve= 0 ,0
Exp/Cntr=0.3,0.1

Type RM Length L Ch R = 1 ,5816    ,489,489,489
BEGIN DESCRIPTION:
UNT0511 IN WICK 10.0
END DESCRIPTION:
XS GIS Cut Line= 2
      3584092.11     10222891.62      3584248.31     10222146.72
#Sta/Elev= 30
  4598.4  247.21  4670.2  243.64  4731.2     240  4825.8  239.57  4853.8  240.11
  4884.5  239.96  4904.9  240.57  4925.3  239.85    4956  240.16  4986.6  239.79
  4996.9  238.46  5014.5  234.95  5017.2  234.45  5020.5  234.95  5027.5  239.31
  5041.9  240.29  5062.3  241.51  5078.6  243.14  5088.8  243.61    5099  243.33
  5119.5  243.75  5150.1  244.87  5170.6   246.1  5180.8  246.15  5206.9  247.72
  5242.1  248.08  5262.5  249.58  5301.6  250.25  5323.8  251.86  5359.5  252.57
#Mann= 6 ,-1 , 0
  4598.4     .05       0  4670.2     .16       0  4825.8     .12       0
  5014.5     .07       0  5020.5     .12       0  5041.9     .16       0
Bank Sta=5014.5,5020.5
XS Rating Curve= 0 ,0
Exp/Cntr=0.3,0.1

Type RM Length L Ch R = 1 ,5327    ,535,535,535
BEGIN DESCRIPTION:
UNT0511 IN WICK 9.0
END DESCRIPTION:
XS GIS Cut Line= 3
      3584442.11      10222941.6      3584536.96     10222526.21
      3584462.08     10222225.78
#Sta/Elev= 30
  4785.4  246.93  4804.3   245.6  4809.4  243.73  4816.1  242.64  4826.4  241.84
  4894.3  238.72    4929  237.87  4959.7  239.01  4980.2   238.8  4986.4  237.63
  4991.6  237.62  4997.8   234.7  5000.5   234.2  5003.8   234.7  5021.3  239.04
  5093.1  238.58  5125.6  237.32  5144.4  238.31  5175.1     241  5195.7  241.71
  5211.3   243.8    5278  244.69  5298.7  245.72  5311.1  245.79  5350.2  246.62
  5376.1  248.03  5391.4  248.19  5432.6  249.78  5458.7   251.2  5521.1  252.54
#Mann= 5 ,-1 , 0
  4785.4     .05       0  4894.3     .12       0  4997.8     .07       0
  5003.8     .12       0  5311.1     .16       0
Bank Sta=4997.8,5003.8
XS Rating Curve= 0 ,0
Exp/Cntr=0.3,0.1

Type RM Length L Ch R = 1 ,4792    ,26,26,26
BEGIN DESCRIPTION:
Mapping XS fbbc2a0a
END DESCRIPTION:
XS GIS Cut Line= 4
      3585035.66     10222856.37        3584836.     10222602.89
      3584655.44     10222439.69      3584506.64     10222221.68
#Sta/Elev= 30
  4647.3  244.78  4747.8  238.93  4774.4  237.52  4795.1  235.28  4838.4  234.83
  4902.5  235.63  4908.9  237.29  4931.4  238.57  4952.2  236.95  4980.6  238.46
  4994.8  234.26    5030  237.79  5065.8  236.47  5072.5  237.56    5080  234.76
  5086.7  236.05  5091.2  233.59  5093.9  233.09  5097.2  233.59  5100.9   235.8
  5108.4  235.45  5115.1  237.41  5122.6  236.07  5129.3  238.53  5143.5  239.75
  5186.1  241.98  5238.8   242.4  5264.5  244.84  5330.3  247.63  5477.3  251.94
#Mann= 6 ,-1 , 0
  4647.3     .05       0  4747.8     .16       0  4774.4     .12       0
  5091.2     .07       0  5097.2     .12       0  5238.8     .16       0
Bank Sta=5091.2,5097.2
XS Rating Curve= 0 ,0
Exp/Cntr=0.3,0.1

Type RM Length L Ch R = 1 ,4766    ,50,50,50
BEGIN DESCRIPTION:
Mapping XS a6699599
END DESCRIPTION:
XS GIS Cut Line= 4
      3585099.91     10222856.39      3584848.15     10222580.32
      3584731.83     10222469.21      3584520.05     10222200.15
#Sta/Elev= 30
  4606.2  247.75  4685.8  243.72  4738.5  240.09  4763.5  237.25  4779.7  236.51
  4817.3  234.72    4820  234.22  4823.3  234.72  4912.2  235.31  4940.5  239.07
  4968.9  240.08  4990.1  240.01  4997.4  238.75  5004.3  239.82  5025.7  238.76
  5032.6  239.51  5039.8  238.55  5046.7   239.1    5054  238.35  5060.9  238.96
  5131.7  238.72    5137  239.56  5146.1  239.09  5210.1  241.48  5274.4  242.47
  5295.3  245.68    5353  248.19  5373.9  249.88  5409.1  250.08  5483.1  252.43
#Mann= 6 ,-1 , 0
  4606.2     .05       0  4738.5     .16       0  4779.7     .12       0
  4817.3     .07       0  4823.3     .12       0  5210.1     .16       0
Bank Sta=4817.3,4823.3
XS Rating Curve= 0 ,0
Exp/Cntr=0.3,0.1

Type RM Length L Ch R = 1 ,4716    ,588,588,588
BEGIN DESCRIPTION:
UNT0511 IN WICK 8.0
END DESCRIPTION:
XS GIS Cut Line= 2
      3585142.11     10222841.65      3584546.17     10222163.49
#Sta/Elev= 30
  4586.9  249.11  4694.3  242.96    4805  235.97  4838.7  233.18  4841.4  232.68
  4844.7  233.18    4984  236.86  5004.9  233.85  5019.1  236.65  5082.7  235.65
  5090.3  236.05  5096.9   240.4  5111.2  244.56  5118.7  243.87  5125.4  245.71
  5139.6  243.32  5146.3  245.63  5153.8  244.14  5160.5  246.18  5168.1  244.62
    5174  246.19  5182.3  244.62    5189  246.49  5196.5  244.91  5203.2  246.64
  5217.4  246.34  5245.9  241.59    5281  241.85  5323.7  246.93  5489.7  252.57
#Mann= 6 ,-1 , 0
  4586.9     .05       0  4694.3     .16       0    4805     .12       0
  4838.7     .07       0  4844.7     .12       0    5174     .16       0
Bank Sta=4838.7,4844.7
XS Rating Curve= 0 ,0
Exp/Cntr=0.3,0.1

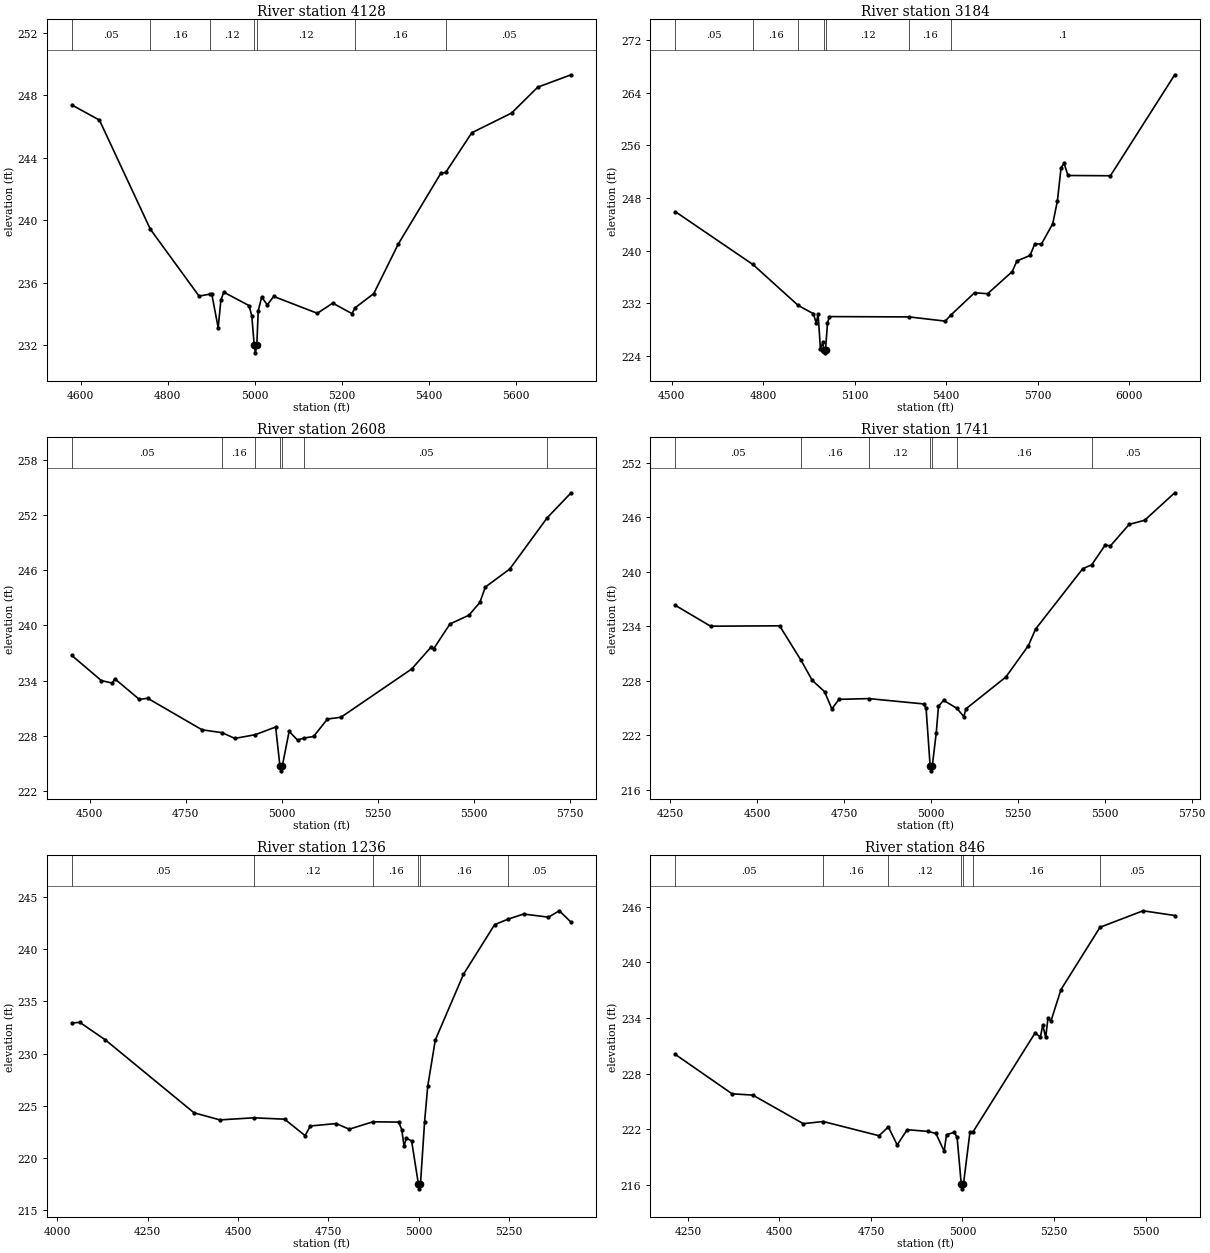
Type RM Length L Ch R = 1 ,4128    ,944,944,944
BEGIN DESCRIPTION:
UNT0511 IN WICK 7.0
END DESCRIPTION:
XS GIS Cut Line= 3
      3585409.74     10222672.74       3584930.6     10222021.74
      3584597.31     10221964.45
#Sta/Elev= 30
  4579.9  247.39  4643.3  246.42  4760.2  239.44  4872.1  235.16  4897.7  235.29
  4901.4  235.27    4916  233.14  4922.2  234.91  4928.9  235.41    4987  234.55
  4993.2  233.88  4998.7  232.03  5001.4  231.53  5004.7  232.03  5007.9  234.21
  5015.8   235.1  5028.7   234.6  5043.4  235.14  5143.6  234.06  5179.1  234.71
  5223.1  234.04  5230.3  234.41  5273.2  235.32  5329.5  238.49  5427.3  243.02
  5438.4  243.07  5498.3  245.61  5589.6  246.87  5649.9  248.53  5726.4  249.32
#Mann= 7 ,-1 , 0
  4579.9     .05       0  4760.2     .16       0  4897.7     .12       0
  4998.7     .07       0  5004.7     .12       0  5230.3     .16       0
  5438.4     .05       0
Bank Sta=4998.7,5004.7
XS Rating Curve= 0 ,0
Exp/Cntr=0.3,0.1

Type RM Length L Ch R = 1 ,3184    ,576,576,576
BEGIN DESCRIPTION:
UNT0511 IN WICK 6.0
END DESCRIPTION:
XS GIS Cut Line= 2
      3585542.12     10222741.62      3586367.62     10221329.85
#Sta/Elev= 30
  4512.8  245.92  4766.6   237.9  4914.9  231.68  4964.5  230.42  4974.3  228.98
  4980.1  230.43  4987.7  225.09  4995.8  226.08  4998.6  224.97  5001.4  224.47
  5004.6  224.97  5010.9  228.98  5017.3  229.98    5279  229.93  5396.7  229.29
  5413.9  230.17  5492.5   233.6  5535.5  233.46  5615.7  236.81  5631.4  238.44
  5674.3  239.27    5690  241.05  5711.5     241  5748.7   244.1  5763.9  247.55
    5776  252.63  5785.9  253.27  5798.6  251.43  5937.6  251.39  6148.2  266.74
#Mann= 7 ,-1 , 0
  4512.8     .05       0  4766.6     .16       0  4914.9     .12       0
  4998.6     .07       0  5004.6     .12       0    5279     .16       0
  5413.9      .1       0
Bank Sta=4998.6,5004.6
XS Rating Curve= 0 ,0
Exp/Cntr=0.3,0.1

Type RM Length L Ch R = 1 ,2608    ,867,867,867
BEGIN DESCRIPTION:
UNT0511 IN WICK 5.0
END DESCRIPTION:
XS GIS Cut Line= 2
      3585915.01     10222672.74      3586774.32     10221698.85
#Sta/Elev= 30
    4454  236.73  4530.8     234  4559.2  233.72  4565.9  234.19  4629.5  231.95
  4651.3  232.07  4792.6  228.64  4845.2  228.32    4878   227.7  4930.7   228.1
  4984.2  228.94  4995.4  224.67  4998.2  224.17  5001.4  224.67  5019.3  228.47
  5041.1  227.52  5057.4  227.73  5082.9  227.91  5118.9  229.81    5154     230
  5338.1  235.26  5388.3  237.63    5395  237.44  5437.6  240.16    5487  241.11
  5515.4   242.5  5529.7  244.18  5593.2  246.14  5690.6  251.72  5752.8  254.44
#Mann= 7 ,-1 , 0
    4454     .05       0  4845.2     .16       0  4930.7     .12       0
  4995.4     .07       0  5001.4     .16       0  5057.4     .05       0
  5690.6      .1       0
Bank Sta=4995.4,5001.4
XS Rating Curve= 0 ,0
Exp/Cntr=0.3,0.1

Type RM Length L Ch R = 1 ,1741    ,505,505,505
BEGIN DESCRIPTION:
UNT0511 IN WICK 4.0
END DESCRIPTION:
XS GIS Cut Line= 4
      3586095.25     10222873.16      3586321.22      10222750.9
      3587133.72     10222146.74      3587191.03     10221990.45
#Sta/Elev= 30
  4265.4  236.29  4366.5     234    4565  234.04  4626.9  230.22  4658.9  228.03
  4694.4  226.78  4715.2  224.89    4736  225.94  4821.3  226.02  4980.1  225.43
  4986.3  224.93    4998  218.56  5000.7  218.06    5004  218.56  5015.6  222.28
  5021.9  225.17  5036.4  225.83  5074.8  224.95  5094.8  224.04  5101.1   224.9
  5215.8   228.4  5280.5  231.86  5301.3  233.69  5436.9  240.34  5462.5  240.76
  5501.6  242.95  5516.2  242.84  5570.3  245.22  5614.8  245.67  5701.3   248.7
#Mann= 7 ,-1 , 0
  4265.4     .05       0  4626.9     .16       0  4821.3     .12       0
    4998     .07       0    5004     .12       0  5074.8     .16       0
  5462.5     .05       0
Bank Sta=4998,5004
XS Rating Curve= 0 ,0
Exp/Cntr=0.3,0.1

Type RM Length L Ch R = 1 ,1236    ,390,390,390
BEGIN DESCRIPTION:
UNT0511 IN WICK 3.0
END DESCRIPTION:
XS GIS Cut Line= 4
      3586289.93     10223052.99      3586534.77     10223042.57
      3587362.89     10222464.45      3587378.52     10222339.43
#Sta/Elev= 30
  4040.2  232.93  4062.4  232.98  4132.5  231.32  4378.2  224.34  4449.7  223.66
  4542.8  223.86  4628.6  223.73  4685.3  222.16  4700.1  223.08  4771.6  223.31
  4807.4  222.77  4873.2  223.48  4944.3  223.45  4952.8  222.72  4959.2  221.12
  4965.3  221.93  4980.1  221.64  4998.6  217.57  5001.3  217.07  5004.6  217.57
  5015.9  223.47  5024.6  226.88  5045.5  231.29  5123.5  237.58  5209.5  242.32
  5245.3  242.83  5289.8  243.34  5358.5  243.04  5388.7  243.65  5421.2  242.55
#Mann= 6 ,-1 , 0
  4040.2     .05       0  4542.8     .12       0  4873.2     .16       0
  4998.6     .07       0  5004.6     .16       0  5245.3     .05       0
Bank Sta=4998.6,5004.6
XS Rating Curve= 0 ,0
Exp/Cntr=0.3,0.1

Type RM Length L Ch R = 1 ,846     ,415,415,415
BEGIN DESCRIPTION:
UNT0511 IN WICK 2.0
END DESCRIPTION:
XS GIS Cut Line= 4
      3586467.09     10223266.53      3586706.64      10223313.4
       3587493.1     10222693.61      3587487.95     10222575.25
#Sta/Elev= 30
  4215.9  230.07  4370.7  225.83  4427.3  225.69  4565.1  222.61  4619.7  222.84
    4772  221.31  4797.6  222.26  4821.7  220.31  4848.9  221.96  4906.7  221.77
  4927.5  221.55    4950  219.64  4956.4  221.42  4977.2  221.67  4985.3  221.16
  4996.7  216.08  4999.4  215.58  5002.7  216.08  5020.5  221.71  5028.3  221.69
  5198.5   232.4  5212.9  231.95  5219.3  233.24  5227.4  231.93  5233.7  234.03
  5241.8  233.69  5269.1  237.07  5375.7  243.79  5493.3  245.57  5579.8  245.06
#Mann= 7 ,-1 , 0
  4215.9     .05       0  4619.7     .16       0  4797.6     .12       0
  4996.7     .07       0  5002.7     .12       0  5028.3     .16       0
  5375.7     .05       0
Bank Sta=4996.7,5002.7
XS Rating Curve= 0 ,0
Exp/Cntr=0.3,0.1

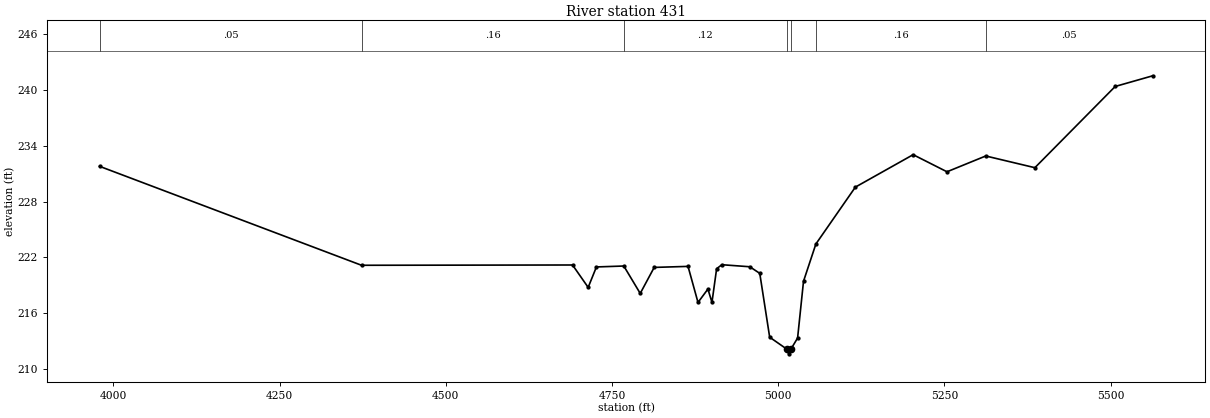
Type RM Length L Ch R = 1 ,431     ,0,0,0
BEGIN DESCRIPTION:
UNT0511 IN WICK 1.0
END DESCRIPTION:
XS GIS Cut Line= 4
      3586557.11     10223483.86      3586885.89     10223497.86
      3587774.35     10222896.74      3587753.64     10222715.51
#Sta/Elev= 30
  3979.2  231.81  4373.3  221.16  4690.7  221.19  4714.2  218.78  4726.6  220.98
  4767.8  221.08  4792.5  218.13  4813.5  220.93  4864.4  221.04  4879.4  217.16
  4894.3   218.6  4900.4  217.17  4907.4  220.79  4915.3  221.22  4957.3     221
  4972.3  220.29  4987.2  213.42  5013.1  212.13  5015.8  211.63  5019.1  212.13
  5029.2  213.33  5038.1  219.44  5056.7  223.45  5116.1  229.57    5203  233.06
  5253.9  231.22  5312.2  232.92  5386.1  231.66  5506.9   240.4  5563.4  241.55
#Mann= 7 ,-1 , 0
  3979.2     .05       0  4373.3     .16       0  4767.8     .12       0
  5013.1     .07       0  5019.1     .12       0  5056.7     .16       0
  5312.2     .05       0
Bank Sta=5013.1,5019.1
XS Rating Curve= 0 ,0
Exp/Cntr=0.3,0.1

Chan Stop Cuts=-1
Use User Specified Reach Order=0
Composite Channel Slope=5