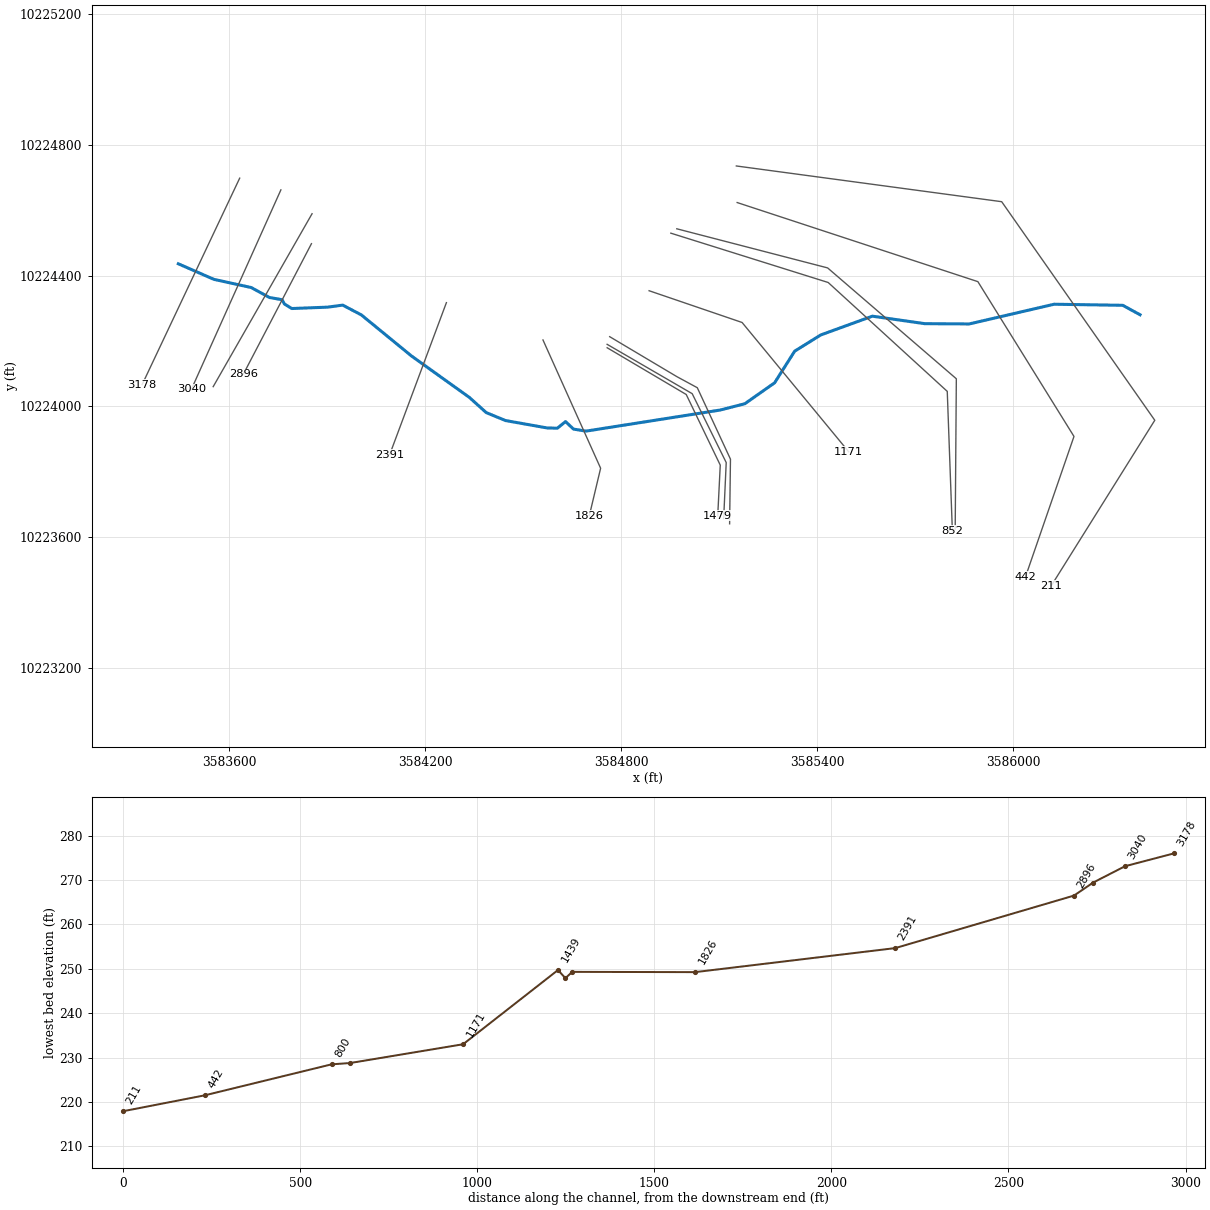
--- BRUSHYCREEKTRIB5.prj (project) ---

Proj Title=BRUSHY CREEK TRIB 5
Current Plan=p01
Default Exp/Contr=0.3,0.1
English Units
Geom File=g01
Flow File=f01
Plan File=p01
Y Axis Title=Elevation
X Axis Title(PF)=Main Channel Distance
X Axis Title(XS)=Station
BEGIN DESCRIPTION:
UNT112 IN WICK
END DESCRIPTION:
DSS Export Rating Curves= 0
DSS Export Rating Curve Sorted= 0
DSS Export Volume Flow Curves= 0
DXF Filename=UNT112 IN WICK.
DXF OffsetX= 0
DXF OffsetY= 0
DXF ScaleX= 1
DXF ScaleY= 10

--- BRUSHYCREEKTRIB5.p01 (plan) ---

Plan Title=Multiple Run
Short Identifier=Multiple
Geom File=g01
Flow File=f01
Subcritical Flow
K Sum by GR= 0
Std Step Tol= 0.01
Critical Tol= 0.01
Num of Std Step Trials= 20
Max Error Tol= 0.3
Flow Tol Ratio= 0.001
Split Flow NTrial= 30
Split Flow Tol= 0.02
Split Flow Ratio= 0.02
Log Output Level= 0
Friction Slope Method= 1
Unsteady Friction Slope Method= 2
Unsteady Bridges Friction Slope Method= 1
Parabolic Critical Depth
Global Vel Dist=  1 , 1 , 1
Global Log Level= 0
CheckData=True
Encroach Param= -1, 0, 0, 0
BEGIN DESCRIPTION:
Multiple Run
END DESCRIPTION:

--- BRUSHYCREEKTRIB5.f01 (steady flow) ---

Flow Title=Multiple
Program Version=4.10
Number of Profiles= 7
Profile Names=10-year,25-year,50-year,1pct_min,100-year,1pct_plu,500-year
River Rch & RM=UNT112 IN WICK,Reach-1         ,3178
     163     204     235     200     270     365     356
River Rch & RM=BRUSHYCRTR5,Reach-1         ,3178
     163     204     235     200     270     365     356
Boundary for River Rch & Prof#=BRUSHYCRTR5,Reach-1         , 1
Up Type= 0
Dn Type= 3
Dn Slope=0.005
Boundary for River Rch & Prof#=BRUSHYCRTR5,Reach-1         , 2
Up Type= 0
Dn Type= 3
Dn Slope=0.005
Boundary for River Rch & Prof#=BRUSHYCRTR5,Reach-1         , 3
Up Type= 0
Dn Type= 3
Dn Slope=0.005
Boundary for River Rch & Prof#=BRUSHYCRTR5,Reach-1         , 4
Up Type= 0
Dn Type= 3
Dn Slope=0.005
Boundary for River Rch & Prof#=BRUSHYCRTR5,Reach-1         , 5
Up Type= 0
Dn Type= 3
Dn Slope=0.005
Boundary for River Rch & Prof#=BRUSHYCRTR5,Reach-1         , 6
Up Type= 0
Dn Type= 3
Dn Slope=0.005
Boundary for River Rch & Prof#=BRUSHYCRTR5,Reach-1         , 7
Up Type= 0
Dn Type= 3
Dn Slope=0.005
DSS Import GetInterval= 0
DSS Import GetPeak= 0
DSS Import FillOption= 0

--- BRUSHYCREEKTRIB5.g01 (geometry) ---

Geom Title=Existing Conditions
Program Version=4.10

River Reach=BRUSHYCRTR5     ,Reach-1
Reach XY= 30
      3583443.57      10224436.7      3583552.25     10224389.13
      3583666.83     10224363.96      3583722.38     10224333.58
      3583761.45     10224326.63      3583768.39     10224313.61
      3583790.96     10224299.72      3583900.98     10224303.92
      3583946.82     10224310.17      3584003.76     10224280.31
      3584157.23     10224154.62      3584334.31     10224027.88
       3584386.4     10223981.01      3584445.43      10223956.7
      3584572.94     10223934.05      3584604.19     10223933.35
      3584629.19     10223953.49       3584653.5     10223930.57
      3584691.69     10223924.32      3585102.63     10223988.91
      3585178.15     10224008.18       3585269.3     10224072.24
      3585330.76     10224169.12      3585410.33     10224218.65
      3585568.57     10224276.29      3585729.01     10224253.37
      3585865.08     10224252.47       3586125.2     10224312.87
      3586335.27     10224309.57      3586388.28     10224280.59

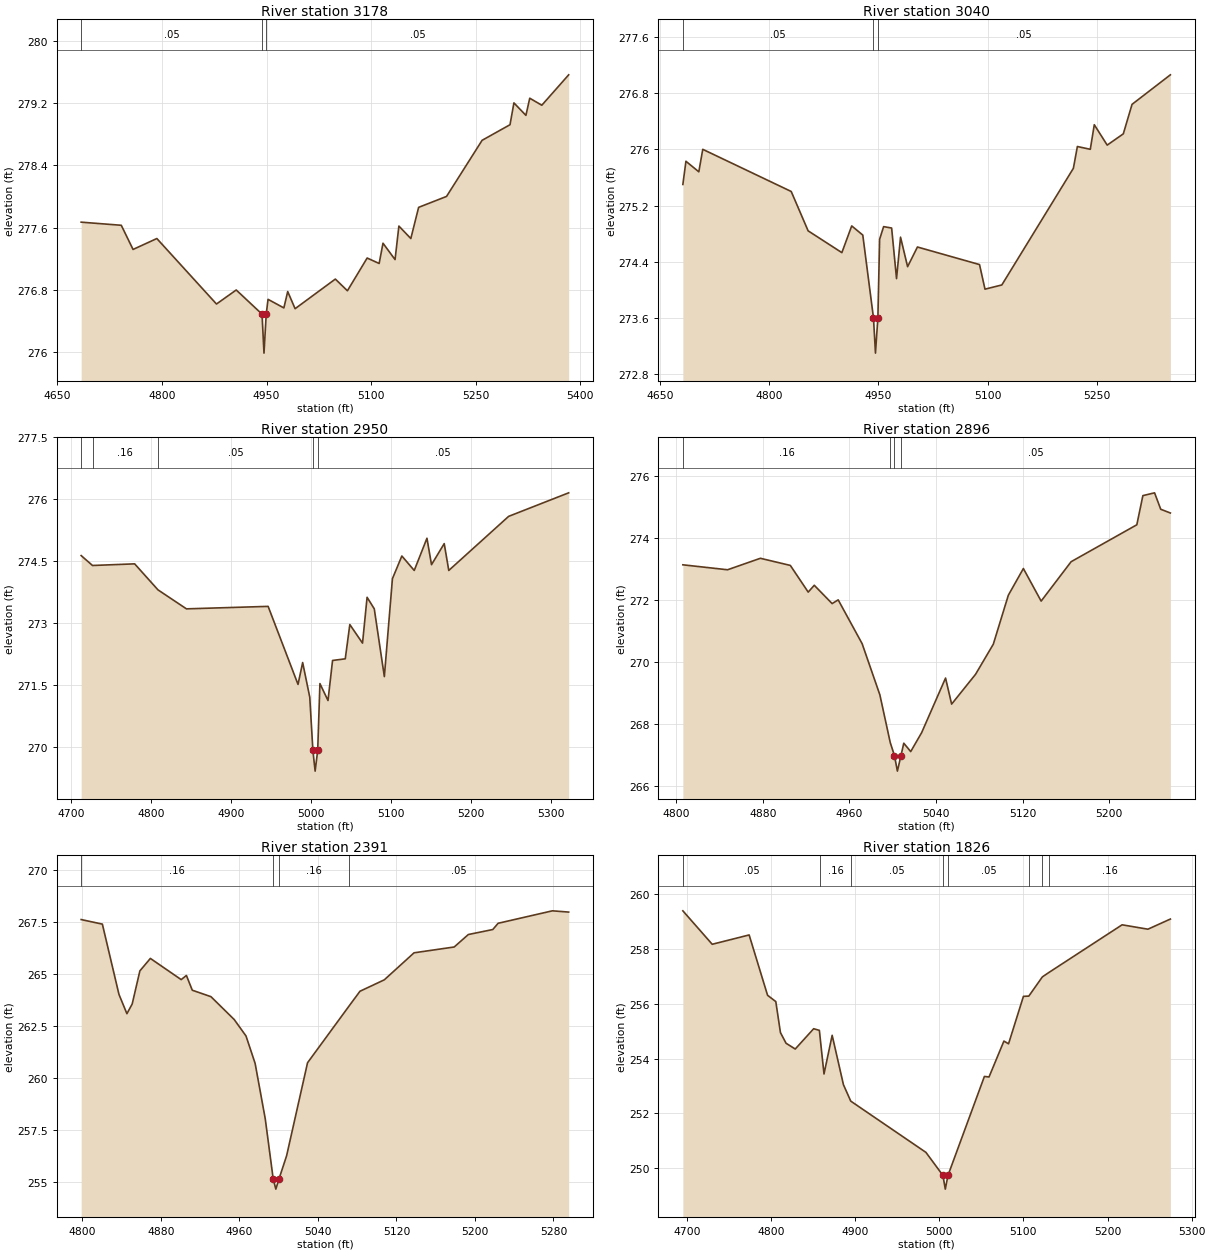
Type RM Length L Ch R = 1 ,3178    ,138,138,138
BEGIN DESCRIPTION:
UNT112 IN WICK 7.0
END DESCRIPTION:
XS GIS Cut Line= 2
      3583631.49     10224698.92       3583332.9     10224067.01
#Sta/Elev= 30
  4684.3  277.67  4741.8  277.63  4758.7  277.32  4792.8  277.46  4878.3  276.62
  4906.6   276.8  4943.6  276.49  4946.4  275.99  4949.6  276.49  4952.2  276.68
  4974.9  276.57  4980.4  276.78    4991  276.56  5048.7  276.94    5066  276.79
  5094.3  277.21  5111.5  277.14    5117   277.4  5134.3  277.19  5139.8  277.62
  5156.9  277.46  5168.1  277.86  5208.1     278  5259.1  278.72  5299.1  278.92
  5304.7   279.2  5321.9  279.04  5327.4  279.26  5344.7  279.17  5383.2  279.56
#Mann= 3 ,-1 , 0
  4684.3     .05       0  4943.6     .03       0  4949.6     .05       0
Bank Sta=4943.6,4949.6
XS Rating Curve= 0 ,0
Exp/Cntr=0.3,0.1

Type RM Length L Ch R = 1 ,3040    ,90,90,90
BEGIN DESCRIPTION:
Mapping XS db4ea93f
END DESCRIPTION:
XS GIS Cut Line= 2
      3583757.64     10224663.04      3583483.76     10224052.67
#Sta/Elev= 30
  4681.7   275.5  4685.9  275.83  4703.6  275.68    4709     276  4830.4   275.4
  4853.6  274.84  4899.9  274.53  4913.4  274.91  4928.6  274.78  4943.3   273.6
    4946   273.1  4949.3   273.6  4951.7  274.72  4957.2   274.9  4968.2  274.88
  4974.9  274.16  4980.4  274.75  4990.1  274.33  5003.6  274.61  5088.8  274.36
  5096.3  274.01  5119.4  274.07  5217.6  275.73  5223.1  276.04  5240.8     276
  5246.3  276.35    5264  276.06  5286.1  276.22  5298.1  276.64  5350.7  277.06
#Mann= 3 ,-1 , 0
  4681.7     .05       0  4943.3     .03       0  4949.3     .05       0
Bank Sta=4943.3,4949.3
XS Rating Curve= 0 ,0
Exp/Cntr=0.3,0.1

Type RM Length L Ch R = 1 ,2950    ,54,54,54
BEGIN DESCRIPTION:
Mapping XS df2e8c69
END DESCRIPTION:
XS GIS Cut Line= 2
      3583853.07     10224589.96      3583550.36     10224060.49
#Sta/Elev= 30
  4712.3  274.64  4726.5   274.4  4779.2  274.44  4808.4  273.81    4844  273.35
  4946.2  273.41  4983.6  271.52  4989.4  272.05  4998.3  271.21  5002.2  269.92
    5005  269.42  5008.2  269.92    5011  271.54  5021.1  271.13  5026.8   272.1
  5042.7  272.14  5048.4  272.97  5064.3  272.52    5070  273.63    5079  273.35
  5091.6  271.71  5101.7  274.08  5113.5  274.63    5129  274.28  5144.9  275.06
  5150.6  274.42  5166.5  274.93  5172.2  274.28  5247.1  275.59  5322.2  276.16
#Mann= 5 ,-1 , 0
  4712.3     .05       0  4726.5     .16       0  4808.4     .05       0
  5002.2     .03       0  5008.2     .05       0
Bank Sta=5002.2,5008.2
XS Rating Curve= 0 ,0
Exp/Cntr=0.3,0.1

Type RM Length L Ch R = 1 ,2896    ,505,505,505
BEGIN DESCRIPTION:
UNT112 IN WICK 6.0
END DESCRIPTION:
XS GIS Cut Line= 2
      3583851.19     10224498.26      3583642.85     10224098.95
#Sta/Elev= 30
  4806.2  273.14  4847.5  272.98  4877.8  273.35  4905.5  273.12    4922  272.26
  4927.6  272.48  4944.1  271.89  4949.7  272.01  4971.8   270.6  4988.2  268.95
  4997.8  267.41  5001.7  266.99  5004.4  266.49  5007.7  266.99  5010.3  267.39
  5016.7  267.12  5026.8  267.73  5048.9  269.49  5054.5  268.65  5076.6  269.61
    5093  270.58  5106.9  272.16  5120.8  273.02  5137.2  271.97  5164.9  273.24
  5225.6  274.43  5231.2  275.37    5242  275.46  5247.7  274.93  5256.6  274.81
#Mann= 4 ,-1 , 0
  4806.2     .16       0  4997.8     .05       0  5001.7     .03       0
  5007.7     .05       0
Bank Sta=5001.7,5007.7
XS Rating Curve= 0 ,0
Exp/Cntr=0.3,0.1

Type RM Length L Ch R = 1 ,2391    ,565,565,565
BEGIN DESCRIPTION:
UNT112 IN WICK 5.0
END DESCRIPTION:
XS GIS Cut Line= 2
      3584264.38      10224317.7      3584090.77     10223852.44
#Sta/Elev= 30
  4798.9  267.62  4820.5   267.4  4837.4  264.02  4845.5  263.09  4850.9  263.56
  4858.7  265.15  4869.4  265.75  4900.8  264.73  4906.1  264.93  4912.1  264.22
  4931.1  263.91  4954.8  262.81  4966.8  262.02  4976.1   260.7  4986.4  258.04
  4994.5  255.15  4997.2  254.65  5000.5  255.15  5008.2  256.26  5029.5  260.73
  5071.8  263.46  5082.9  264.17  5107.7  264.72    5138  266.02  5178.9   266.3
  5193.3   266.9  5218.2  267.14  5223.6  267.44  5278.9  268.04  5295.5  267.98
#Mann= 4 ,-1 , 0
  4798.9     .16       0  4994.5     .07       0  5000.5     .16       0
  5071.8     .05       0
Bank Sta=4994.5,5000.5
XS Rating Curve= 0 ,0
Exp/Cntr=0.3,0.1

Type RM Length L Ch R = 1 ,1826    ,347,347,347
BEGIN DESCRIPTION:
UNT112 IN WICK 4.0
END DESCRIPTION:
XS GIS Cut Line= 3
      3584560.08     10224203.52      3584736.59     10223810.73
      3584702.08     10223665.81
#Sta/Elev= 30
  4695.1  259.39    4730  258.17  4773.9  258.51  4795.8  256.31  4805.6  256.08
  4811.1  254.95  4817.8  254.56  4828.7  254.35  4850.6  255.09  4857.4  255.03
  4858.5  254.71  4862.9  253.44  4872.6  254.85    4886  253.05  4894.7  252.45
  4984.1  250.58  5004.3  249.74  5007.1  249.24  5010.3  249.74  5053.6  253.35
  5059.1  253.33  5076.8  254.64  5082.3  254.54    5100  256.27  5106.4  256.28
  5122.5  256.98  5130.2  257.14  5217.3  258.88    5248  258.72  5274.7  259.09
#Mann= 8 ,-1 , 0
  4695.1     .05       0  4858.5     .16       0  4894.7     .05       0
  5004.3     .04       0  5010.3     .05       0  5106.4     .16       0
  5122.5     .05       0  5130.2     .16       0
Bank Sta=5004.3,5010.3
XS Rating Curve= 0 ,0
Exp/Cntr=0.3,0.1

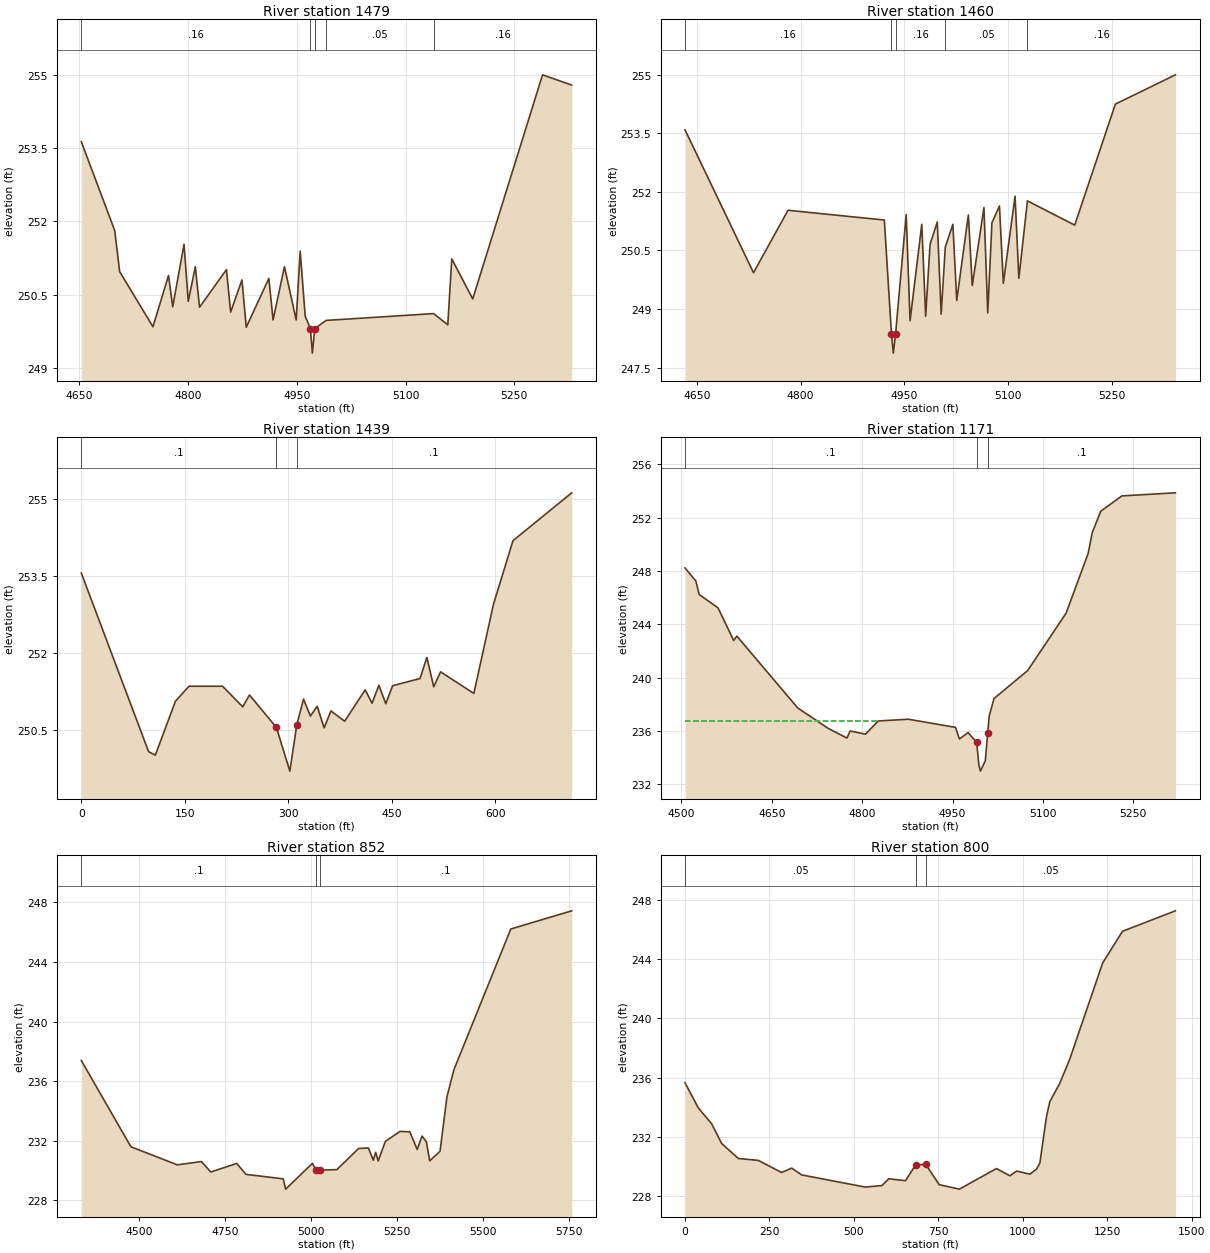
Type RM Length L Ch R = 1 ,1479    ,19,19,19
BEGIN DESCRIPTION:
Mapping XS 9f154a44
END DESCRIPTION:
XS GIS Cut Line= 4
       3584756.6     10224179.63      3584998.74     10224036.42
      3585102.91     10223820.28      3585095.16     10223665.33
#Sta/Elev= 30
  4652.8  253.63  4698.9  251.81  4705.7  250.97  4751.6  249.84  4773.1  250.89
  4778.9  250.25  4794.5  251.53  4800.3  250.36  4810.1  251.07  4815.9  250.24
    4853  251.01  4858.8  250.14  4874.4   250.8  4880.3  249.83  4911.5  250.83
  4917.3  249.98    4933  251.07  4949.2  249.98  4954.7  251.39  4961.6  250.06
  4968.8   249.8  4971.5   249.3  4974.8   249.8  4990.4  249.97  5138.7  250.11
  5158.3  249.88  5163.8  251.23  5192.7  250.41    5289     255  5329.2  254.79
#Mann= 5 ,-1 , 0
  4652.8     .16       0  4968.8    .033       0  4974.8     .16       0
  4990.4     .05       0  5138.7     .16       0
Bank Sta=4968.8,4974.8
XS Rating Curve= 0 ,0
Exp/Cntr=0.3,0.1

Type RM Length L Ch R = 1 ,1460    ,21,21,21
BEGIN DESCRIPTION:
Mapping XS 872a6c9f
END DESCRIPTION:
XS GIS Cut Line= 4
      3584756.51     10224190.09      3585016.97     10224039.03
      3585121.14     10223828.09      3585113.33     10223656.42
#Sta/Elev= 30
  4633.1  253.59    4732  249.93  4781.8  251.53  4920.9  251.28  4931.2  248.37
  4933.9  247.87  4937.2  248.37  4952.5  251.42  4958.1   248.7    4975  251.17
  4980.6  248.82    4987  250.66  4997.4  251.23    5003  248.87    5009  250.59
  5019.9  251.17  5025.5  249.22  5042.3  251.41  5047.9   249.6  5064.8   251.6
  5070.3   248.9  5076.3  251.21  5087.2  251.64  5092.8  249.66  5109.7  251.89
  5115.2  249.79  5127.6  251.77  5195.9  251.15  5254.6  254.25  5341.3     255
#Mann= 5 ,-1 , 0
  4633.1     .16       0  4931.2     .07       0  4937.2     .16       0
    5009     .05       0  5127.6     .16       0
Bank Sta=4931.2,4937.2
XS Rating Curve= 0 ,0
Exp/Cntr=0.3,0.1

Type RM Length L Ch R = 1 ,1439    ,268,268,268
BEGIN DESCRIPTION:
Mapping XS 8468600b
END DESCRIPTION:
XS GIS Cut Line= 5
      3584764.37      10224213.5       3584970.1     10224091.11
       3585032.6     10224057.26      3585134.16     10223838.51
      3585131.55     10223640.56
#Sta/Elev= 30
       0  253.56    97.5  250.09  107.24  250.02  136.49  251.07  155.99  251.36
  204.74  251.36  233.99  250.96  243.74  251.19  282.74  250.56  302.24  249.71
  312.17   250.6   322.1  251.11  332.03  250.78  341.96  250.97  351.89  250.55
  361.83  250.88  381.69  250.68  411.48  251.29  421.42  251.03  431.35  251.38
  441.28  251.02  451.21  251.37  490.94  251.51  500.87  251.92   510.8  251.35
  520.73  251.64  568.96  251.22  597.31  252.95  625.67  254.19  710.75  255.12
#Mann= 3 , 0 , 0
       0      .1       0  282.74     .05       0  312.17      .1       0
Bank Sta=282.74,312.17
XS Rating Curve= 0 ,0
Exp/Cntr=0.3,0.1

Type RM Length L Ch R = 1 ,1171    ,319,319,319
BEGIN DESCRIPTION:
UNT112 IN WICK 2.0
END DESCRIPTION:
XS GIS Cut Line= 3
      3584884.99     10224354.21      3585169.75     10224256.98
      3585496.11     10223861.18
#Sta/Elev= 30
  4505.9  248.22    4524  247.23  4529.3  246.23  4560.6  245.23  4586.7  242.78
  4591.9  243.11  4693.1  237.72  4743.3   236.2  4774.6  235.47  4779.9     236
  4805.4  235.76  4826.7  236.75  4876.6  236.88  4954.8  236.27  4961.3   235.4
  4975.6  235.88    4990  235.14  4993.5  233.49  4996.2  232.99  5004.3  233.77
 5008.23  235.83  5010.8  237.13  5018.7  238.43  5074.6  240.53  5138.5  244.84
    5175  249.31  5181.5  250.82  5195.8  252.47    5231  253.62  5319.8  253.85
#Mann= 3 , 0 , 0
  4505.9      .1       0    4990     .05       0 5008.23      .1       0
#XS Ineff= 2 , 0
         4825.87  236.73
Permanent Ineff=
       F       F
Bank Sta=4990,5008.23
XS Rating Curve= 0 ,0
Exp/Cntr=0.3,0.1

Type RM Length L Ch R = 1 ,852     ,52,52,52
BEGIN DESCRIPTION:
Mapping XS 3178d642
END DESCRIPTION:
XS GIS Cut Line= 4
      3584951.54     10224530.47      3585433.35     10224379.42
      3585797.93     10224046.08      3585813.56     10223618.99
#Sta/Elev= 30
  4331.9  237.39  4476.2   231.6  4611.2  230.39  4681.3  230.61  4708.5  229.91
  4783.8  230.48    4811  229.75  4919.1  229.45  4926.3  228.76  5004.2  230.49
 5015.08  230.02 5027.21  230.03  5075.2  230.07  5138.7  231.49    5167  231.52
  5181.2   230.7    5188  231.23  5195.4  230.65  5216.4  231.97  5258.9  232.63
  5287.3  232.61  5308.9  231.42  5322.9  232.32  5335.5  231.94  5345.3  230.66
  5375.3   231.3  5395.3  234.94  5415.3  236.75  5581.1  246.21  5758.2  247.43
#Mann= 3 , 0 , 0
  4331.9      .1       0 5015.08     .05       0 5027.21      .1       0
#Block Obstruct= 2 , 0
         5018.05  229.83
Bank Sta=5015.08,5027.21
XS Rating Curve= 0 ,0
Exp/Cntr=0.3,0.1

Type RM Length L Ch R = 1 ,800     ,358,358,358
XS GIS Cut Line= 4
     3584969.821    10224543.861     3585431.626     10224424.07
     3585825.724     10224084.66     3585822.251    10223623.722
#Sta/Elev= 30
       0  235.65   39.45  233.95    78.9  232.88  108.49  231.55   157.8  230.54
  216.97  230.41  286.01  229.59   315.6  229.89  345.19  229.43  533.22  228.61
  583.06  228.71     603  229.17  652.85  229.04  682.76  230.11  712.67  230.14
  752.54  228.77  812.36  228.47  922.02  229.86   961.9  229.37  981.84  229.69
 1021.18  229.48 1040.76  229.82 1050.55  230.23 1070.13  233.36 1079.92  234.37
 1109.29   235.6 1138.66  237.22 1236.56  243.74 1295.29  245.88 1451.93  247.26
#Mann= 3 , 0 , 0
       0     .05       0  682.76     .03       0  712.67     .05       0
#XS Ineff= 2 , 0
       0  682.76  230.11  712.67       0  230.14
Permanent Ineff=
       T       T
Bank Sta=682.76,712.67
XS Rating Curve= 0 ,0
Exp/Cntr=0.3,0.1

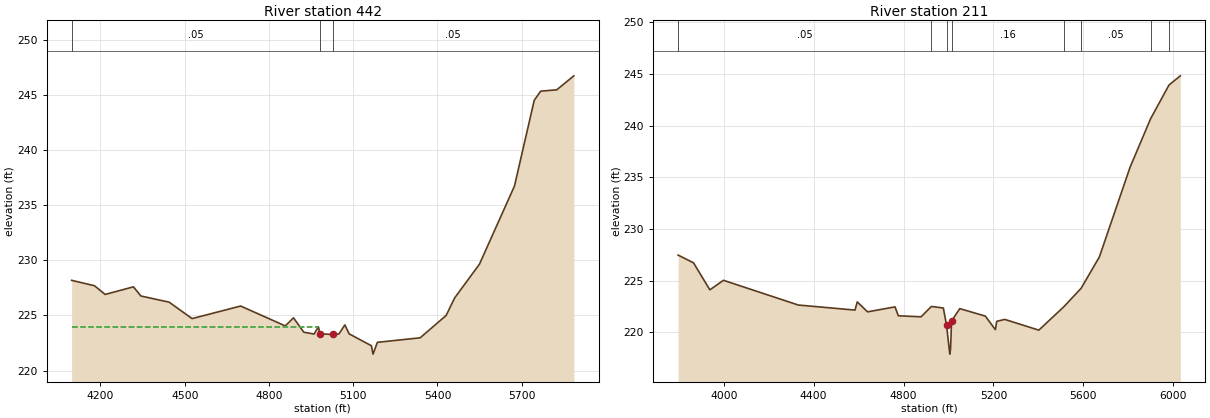
Type RM Length L Ch R = 1 ,442     ,231,231,231
BEGIN DESCRIPTION:
Mapping XS d11b6ed8
END DESCRIPTION:
XS GIS Cut Line= 4
      3585154.68     10224624.21      3585891.68     10224382.02
      3586185.95     10223908.06       3586037.5     10223478.34
#Sta/Elev= 30
  4097.3  228.18  4178.8  227.69  4216.6   226.9  4317.3  227.59  4343.9  226.76
  4444.5   226.2  4526.2  224.71    4699  225.85    4858  224.05  4887.3  224.78
  4923.9  223.48  4960.5  223.31  4975.9  223.96  4981.7  223.34  5026.5  223.27
  5049.1  223.32  5070.3  224.14  5085.4  223.33  5164.8  222.25  5170.5  221.49
  5186.1  222.56  5338.4  222.97    5431     225  5461.1  226.58  5549.4  229.64
  5674.1  236.72  5744.6   244.5  5767.7  245.33  5824.7  245.45  5885.6  246.72
#Mann= 3 , 0 , 0
  4097.3     .05       0  4981.7     .03       0  5026.5     .05       0
#XS Ineff= 2 , 0
       0 4975.31  223.95               0
Permanent Ineff=
       F       F
#Block Obstruct= 2 , 0
                         5092.68          223.38
Bank Sta=4981.7,5026.5
XS Rating Curve= 0 ,0
Exp/Cntr=0.3,0.1

Type RM Length L Ch R = 1 ,211     ,0,0,0
BEGIN DESCRIPTION:
UNT112 IN WICK 1.0
END DESCRIPTION:
XS GIS Cut Line= 4
       3585152.1     10224736.19       3585964.6     10224626.81
      3586433.35     10223957.54       3586116.4     10223450.94
#Sta/Elev= 30
  3797.1  227.48  3865.7  226.73  3938.4  224.12  3998.9  225.04  4331.9  222.65
  4584.1  222.16  4594.2  222.95  4640.1  221.99  4762.2  222.47    4777  221.61
  4878.1  221.51  4924.1  222.51  4977.3  222.36  4991.5  220.69    5006   217.9
  5009.3   218.4  5013.9  221.12  5050.5   222.3  5164.1  221.58  5208.6  220.27
  5214.7  221.07  5250.4  221.26  5402.1  220.22  5513.2  222.48  5590.3  224.27
  5671.5   227.3  5808.3  235.99  5899.7  240.68  5981.3  243.93  6031.6  244.82
#Mann= 8 ,-1 , 0
  3797.1     .05       0  4924.1     .16       0  4991.5     .07       0
  5013.9     .16       0  5513.2      .1       0  5590.3     .05       0
  5899.7     .16       0  5981.3     .05       0
Bank Sta=4991.5,5013.9
XS Rating Curve= 0 ,0
Exp/Cntr=0.3,0.1
Stream Node=UNT112 IN WICK  ,Reach-1         , 0 , 0 ,Upstream end
Stream Node=UNT112 IN WICK  ,Reach-1         , 0 , 1 ,Downstream end

Chan Stop Cuts=-1
Use User Specified Reach Order=0
Composite Channel Slope=5