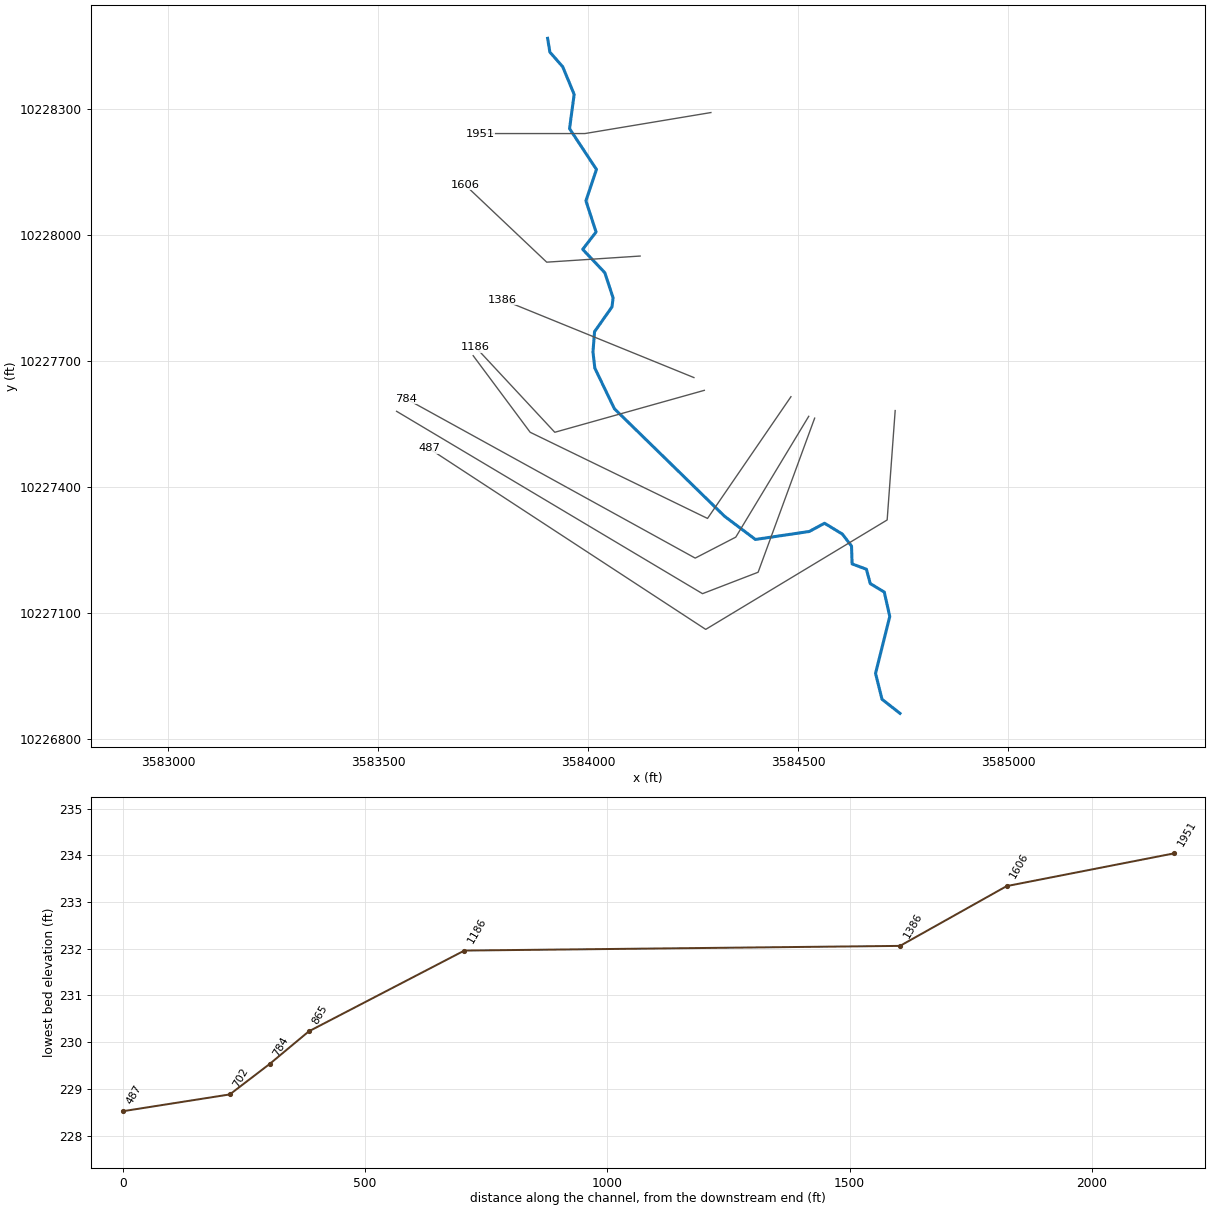
--- BRUSHYCREEKTRIB7.prj (project) ---

Proj Title=BRUSHY CREEK TRIB 7
Current Plan=p01
Default Exp/Contr=0.3,0.1
English Units
Geom File=g01
Flow File=f01
Plan File=p01
Y Axis Title=Elevation
X Axis Title(PF)=Main Channel Distance
X Axis Title(XS)=Station
BEGIN DESCRIPTION:
UNT05313 IN WICK
END DESCRIPTION:
DSS Export Rating Curves= 0
DSS Export Rating Curve Sorted= 0
DSS Export Volume Flow Curves= 0
DXF Filename=UNT05313 IN WICK.
DXF OffsetX= 0
DXF OffsetY= 0
DXF ScaleX= 1
DXF ScaleY= 10

--- BRUSHYCREEKTRIB7.p01 (plan) ---

Plan Title=Multiple Run
Short Identifier=Multiple
Geom File=g01
Flow File=f01
Subcritical Flow
K Sum by GR= 0
Std Step Tol= 0.01
Critical Tol= 0.01
Num of Std Step Trials= 20
Max Error Tol= 0.3
Flow Tol Ratio= 0.001
Split Flow NTrial= 30
Split Flow Tol= 0.02
Split Flow Ratio= 0.02
Log Output Level= 0
Friction Slope Method= 1
Unsteady Friction Slope Method= 2
Unsteady Bridges Friction Slope Method= 1
Parabolic Critical Depth
Global Vel Dist=  1 , 1 , 1
Global Log Level= 0
CheckData=True
Encroach Param= -1, 0, 0, 0
BEGIN DESCRIPTION:
Multiple Run
END DESCRIPTION:

--- BRUSHYCREEKTRIB7.f01 (steady flow) ---

Flow Title=Multiple
Program Version=4.10
Number of Profiles= 7
Profile Names=10-year,25-year,50-year,1pct_min,100-year,1pct_plu,500-year
River Rch & RM=UNT05313 IN WICK,Reach-1         ,1951
     205     259     300     256     346     468     460
River Rch & RM=BRUSHYCREEKTR7,Reach-1         ,1951
     205     259     300     256     346     468     460
Boundary for River Rch & Prof#=BRUSHYCREEKTR7,Reach-1         , 1
Up Type= 0
Dn Type= 3
Dn Slope=0.005
Boundary for River Rch & Prof#=BRUSHYCREEKTR7,Reach-1         , 2
Up Type= 0
Dn Type= 3
Dn Slope=0.005
Boundary for River Rch & Prof#=BRUSHYCREEKTR7,Reach-1         , 3
Up Type= 0
Dn Type= 3
Dn Slope=0.005
Boundary for River Rch & Prof#=BRUSHYCREEKTR7,Reach-1         , 4
Up Type= 0
Dn Type= 3
Dn Slope=0.005
Boundary for River Rch & Prof#=BRUSHYCREEKTR7,Reach-1         , 5
Up Type= 0
Dn Type= 3
Dn Slope=0.005
Boundary for River Rch & Prof#=BRUSHYCREEKTR7,Reach-1         , 6
Up Type= 0
Dn Type= 3
Dn Slope=0.005
Boundary for River Rch & Prof#=BRUSHYCREEKTR7,Reach-1         , 7
Up Type= 0
Dn Type= 3
Dn Slope=0.005
DSS Import GetInterval= 0
DSS Import GetPeak= 0
DSS Import FillOption= 0

--- BRUSHYCREEKTRIB7.g01 (geometry) ---

Geom Title=Existing Conditions
Program Version=4.10

River Reach=BRUSHYCREEKTR7  ,Reach-1
Reach XY= 30
       3583903.4     10228468.27      3583908.77     10228435.56
      3583939.36     10228400.62      3583966.62     10228334.85
      3583955.63      10228253.3      3584019.74     10228156.15
      3583994.58     10228081.62      3584018.76     10228007.31
      3583986.95     10227966.06      3584039.53     10227910.51
       3584059.3     10227850.56      3584056.66     10227829.11
      3584015.15     10227770.13      3584011.37     10227721.67
      3584015.83     10227683.28      3584062.41     10227586.67
      3584324.16     10227331.12      3584397.94     10227275.56
      3584526.13     10227294.55      3584562.45     10227314.13
      3584604.82      10227288.5      3584626.75     10227259.85
       3584628.1     10227217.39      3584662.17     10227204.72
      3584671.32     10227170.52      3584704.68     10227150.37
      3584717.78     10227092.37      3584683.93     10226956.75
      3584699.33     10226895.23      3584742.11     10226861.64

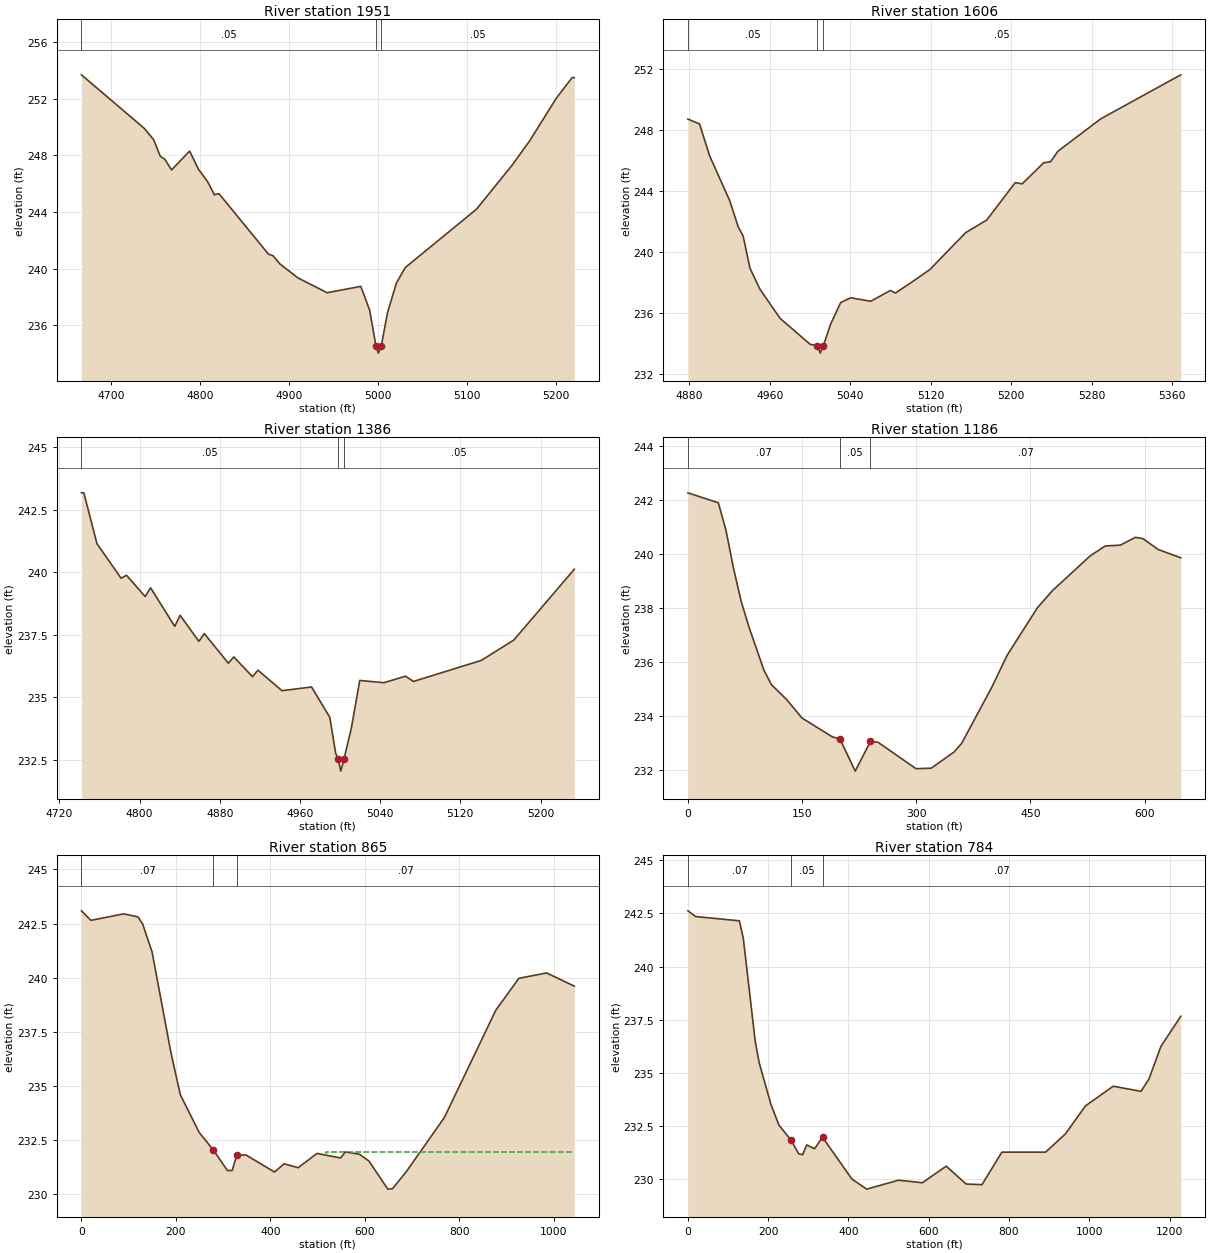
Type RM Length L Ch R = 1 ,1951    ,345,345,345
BEGIN DESCRIPTION:
UNT05313 IN WICK 3.0
END DESCRIPTION:
XS GIS Cut Line= 3
      3584292.06     10228291.63      3583992.11     10228241.64
       3583742.1     10228241.64
#Sta/Elev= 30
  4666.5  253.67  4737.4  249.88  4747.6   249.1  4755.2  247.92  4760.2  247.72
  4767.8  246.96  4788.1  248.29  4798.2     247  4808.4  246.13    4816  245.21
  4821.1  245.29  4876.8  241.02  4881.9  240.91  4889.5  240.34  4909.8  239.35
  4942.7   238.3  4980.6  238.75  4990.6  237.05  4997.6  234.54  5000.3  234.04
  5003.6  234.54  5010.6  236.89  5020.6  238.98  5030.6  240.08  5110.6  244.19
  5150.6  247.29  5170.6  249.03  5200.6  252.04  5218.1  253.47  5220.6  253.47
#Mann= 3 ,-1 , 0
  4666.5     .05       0  4997.6     .03       0  5003.6     .05       0
Bank Sta=4997.6,5003.6
XS Rating Curve= 0 ,0
Exp/Cntr=0.3,0.1

Type RM Length L Ch R = 1 ,1606    ,220,220,220
BEGIN DESCRIPTION:
UNT05313 IN WICK 2.0
END DESCRIPTION:
XS GIS Cut Line= 3
      3584123.63     10227950.13      3583901.27     10227935.53
      3583707.03     10228119.39
#Sta/Elev= 30
  4878.5  248.69  4890.1  248.37  4900.1  246.28  4920.1  243.34  4928.5  241.63
  4933.5  241.01  4940.2  238.92  4950.2  237.53  4970.2  235.62  5000.3  233.91
  5007.3  233.84  5010.1  233.34  5013.3  233.84  5020.3  235.21  5030.4  236.65
  5040.4  236.97  5060.4  236.74  5079.9  237.45  5084.9  237.28  5101.3     238
  5119.2  238.82  5154.8  241.24  5175.8  242.07  5204.1  244.52    5211  244.44
  5232.4  245.82  5239.3  245.89  5246.6  246.58  5289.1   248.7  5368.8  251.59
#Mann= 3 ,-1 , 0
  4878.5     .05       0  5007.3     .03       0  5013.3     .05       0
Bank Sta=5007.3,5013.3
XS Rating Curve= 0 ,0
Exp/Cntr=0.3,0.1

Type RM Length L Ch R = 1 ,1386    ,899,899,899
BEGIN DESCRIPTION:
Mapping XS 1c158731
END DESCRIPTION:
XS GIS Cut Line= 2
      3584251.66     10227660.87      3583796.12     10227846.21
#Sta/Elev= 30
  4741.9  243.17  4744.3  243.17  4757.4  241.14  4781.5  239.76  4786.9  239.88
  4805.5  239.03  4810.9  239.38    4835  237.84  4840.4  238.28  4859.1  237.24
  4864.5  237.55  4888.5  236.37  4893.9  236.62  4912.6  235.83    4918  236.09
  4942.1  235.27  4971.5  235.42  4989.7  234.21  4995.6  232.77    4998  232.56
  5000.7  232.06    5004  232.56  5011.3  233.79  5019.6  235.68  5043.7  235.59
  5065.3  235.85  5073.2  235.64  5140.9  236.48  5173.3  237.29  5233.7  240.12
#Mann= 3 ,-1 , 0
  4741.9     .05       0    4998     .03       0    5004     .05       0
Bank Sta=4998,5004
XS Rating Curve= 0 ,0
Exp/Cntr=0.3,0.1

Type RM Length L Ch R = 1 ,1186    ,321,321,321
XS GIS Cut Line= 3
     3584276.407    10227630.495     3583920.504    10227530.669
     3583731.702    10227733.577
#Sta/Elev= 30
       0  242.28   39.96  241.91   49.95   240.9   59.94  239.48   69.93  238.26
   79.92  237.33    99.9   235.7  109.89  235.16  129.87  234.61  149.85  233.93
  189.81  233.23   199.8  233.15  219.78  231.96  239.77  233.06  249.76  233.03
  299.71  232.05  319.69  232.07  349.66  232.67  359.65  232.99   399.4  235.08
  419.25  236.25  458.94  238.01  478.78  238.65  528.39  239.94  548.23  240.31
  568.08  240.34  587.92  240.63  597.84  240.58  617.69  240.18  647.45  239.87
#Mann= 3 , 0 , 0
       0     .07       0   199.8     .05       0  239.77     .07       0
Bank Sta=199.8,239.77
XS Rating Curve= 0 ,0
Exp/Cntr=0.3,0.1

Type RM Length L Ch R = 1 ,865     ,81,81,81
XS GIS Cut Line= 4
      3584482.57    10227615.304     3584284.003    10227325.591
     3583861.911    10227530.669     3583726.277    10227712.961
#Sta/Elev= 30
       0  243.09   19.94  242.65   89.72  242.95  119.62  242.81  129.59  242.48
  149.53  241.19   189.4  236.54  209.34  234.59  249.22  232.85  279.12  232.04
  309.03  231.09     319  231.09  328.97  231.81   348.9   231.8  408.81  231.02
  428.78   231.4  458.73  231.22  498.67  231.88  548.59  231.67  558.58  231.95
  588.53  231.84   608.5  231.53  648.44  230.23  658.42  230.25  688.38  231.06
  768.26  233.54  876.89  238.49  925.81  239.97  984.52  240.22 1043.23  239.61
#Mann= 3 , 0 , 0
       0     .07       0  279.12     .05       0  328.97     .07       0
#XS Ineff= 2 , 0
                          517.36          231.95
Permanent Ineff=
       F       F
Bank Sta=279.12,328.97
XS Rating Curve= 0 ,0
Exp/Cntr=0.3,0.1

Type RM Length L Ch R = 1 ,784     ,82,82,82
XS GIS Cut Line= 4
     3584524.888    10227568.646     3584351.277    10227281.103
     3584254.706     10227231.19     3583565.687    10227610.964
#Sta/Elev= 30
       0  242.62   19.73  242.35  128.21  242.15  138.08  241.32  167.67  236.49
  177.53  235.48  207.12   233.5  226.84  232.54  256.43  231.85  276.15  231.19
  286.02  231.15  295.88  231.61  315.61  231.43  335.33  231.97  408.77     230
  445.48  229.53  524.72  229.95  584.14  229.83  643.57  230.61  693.09  229.77
   732.7  229.74  782.23  231.27  891.17  231.27  940.69  232.13  990.21  233.44
 1059.54  234.37 1128.87  234.13 1148.68  234.71 1178.39  236.24 1227.91  237.66
#Mann= 3 , 0 , 0
       0     .07       0  256.43     .05       0  335.33     .07       0
#XS Ineff= 2 , 0
       0                  336.38       0  231.38
Permanent Ineff=
       F       T
Bank Sta=256.43,335.33
XS Rating Curve= 0 ,0
Exp/Cntr=0.3,0.1

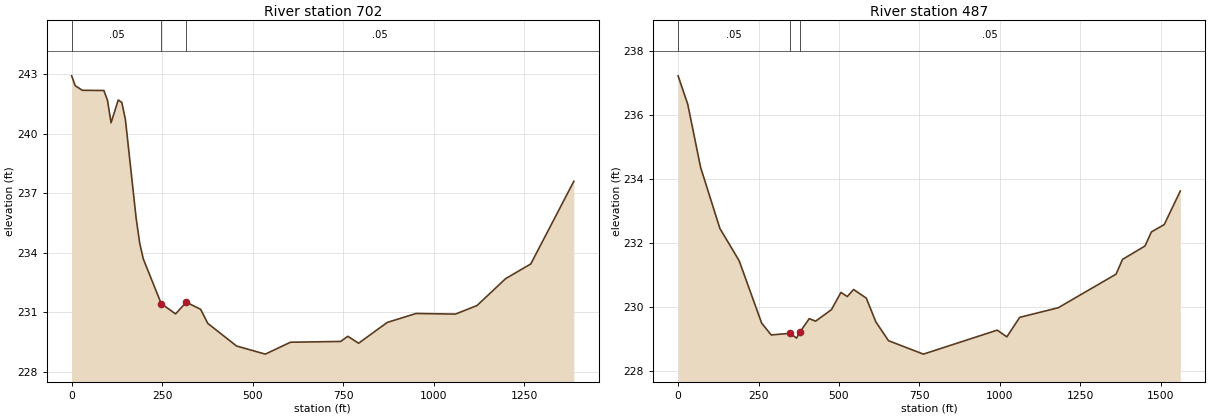
Type RM Length L Ch R = 1 ,702     ,221,221,221
XS GIS Cut Line= 4
     3584538.994    10227564.306     3584404.445    10227197.553
     3584272.067    10227146.554     3583543.985    10227580.582
#Sta/Elev= 30
       0  242.92    9.89  242.42   29.68  242.19   89.04  242.18   98.94  241.69
  108.83  240.55  128.62   241.7  138.51  241.58  148.41  240.72  178.09  235.74
  187.98  234.47  197.88  233.68  247.35  231.43  286.92  230.91   316.6   231.5
  356.18  231.14  375.97  230.43  455.35  229.29  534.82  228.88  604.16  229.48
  742.84  229.52  762.65  229.78  792.37  229.43  871.62  230.48  950.87  230.93
 1059.84   230.9 1119.27  231.33 1198.52  232.69 1267.86  233.43 1386.73   237.6
#Mann= 3 , 0 , 0
       0     .05       0  247.35     .03       0   316.6     .05       0
#XS Ineff= 2 , 0
       0                  320.82       0  230.87
Permanent Ineff=
       F       T
Bank Sta=247.35,316.6
XS Rating Curve= 0 ,0
Exp/Cntr=0.3,0.1

Type RM Length L Ch R = 1 ,487     ,0,0,0
XS GIS Cut Line= 4
     3584730.661    10227582.388     3584711.564    10227321.971
     3584279.727    10227061.555     3583621.286     10227492.11
#Sta/Elev= 30
       0  237.22   29.96  236.33   69.91  234.36  129.83  232.45  189.76  231.44
  259.67  229.49  289.37  229.12   348.5  229.17  368.21  229.02  378.07   229.2
  407.63  229.63  427.34  229.55  476.62  229.91  506.18  230.45   525.9  230.32
  545.61  230.54  585.03  230.27  614.59  229.53  654.01  228.94  762.42  228.52
  991.95  229.27  1021.9  229.06 1061.84  229.67 1181.66  229.97 1361.39  231.02
 1381.36  231.48 1451.26   231.9 1471.23  232.34 1511.17  232.57 1561.09  233.62
#Mann= 3 ,-1 , 0
       0     .05       0   348.5     .03       0  378.07     .05       0
Bank Sta=348.5,378.07
XS Rating Curve= 0 ,0
Exp/Cntr=0.3,0.1

Chan Stop Cuts=-1
Use User Specified Reach Order=0
Composite Channel Slope=5