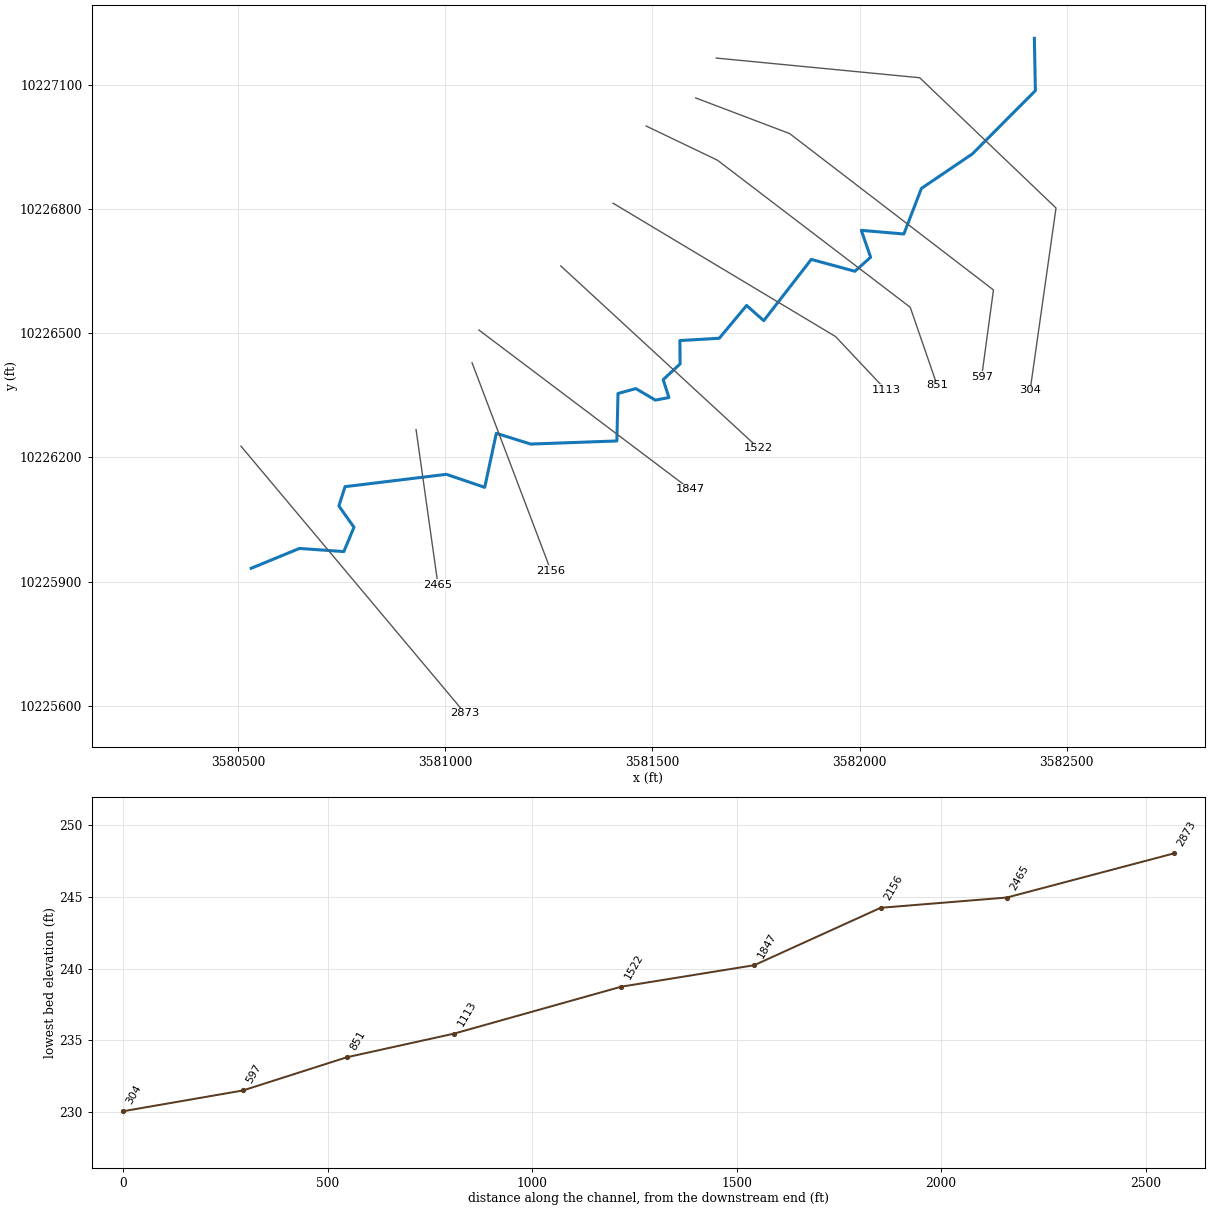
--- BRUSHYCREEKTRIB8.prj (project) ---

Proj Title=BRUSHY CREEK TRIB 8
Current Plan=p01
Default Exp/Contr=0.3,0.1
English Units
Geom File=g01
Flow File=f01
Plan File=p01
Y Axis Title=Elevation
X Axis Title(PF)=Main Channel Distance
X Axis Title(XS)=Station
BEGIN DESCRIPTION:
UNT05310 IN WICK
END DESCRIPTION:
DSS Export Rating Curves= 0
DSS Export Rating Curve Sorted= 0
DSS Export Volume Flow Curves= 0
DXF Filename=UNT05310 IN WICK.
DXF OffsetX= 0
DXF OffsetY= 0
DXF ScaleX= 1
DXF ScaleY= 10

--- BRUSHYCREEKTRIB8.p01 (plan) ---

Plan Title=Multiple Run
Short Identifier=Multiple
Geom File=g01
Flow File=f01
Subcritical Flow
K Sum by GR= 0
Std Step Tol= 0.01
Critical Tol= 0.01
Num of Std Step Trials= 20
Max Error Tol= 0.3
Flow Tol Ratio= 0.001
Split Flow NTrial= 30
Split Flow Tol= 0.02
Split Flow Ratio= 0.02
Log Output Level= 0
Friction Slope Method= 1
Unsteady Friction Slope Method= 2
Unsteady Bridges Friction Slope Method= 1
Parabolic Critical Depth
Global Vel Dist=  1 , 1 , 1
Global Log Level= 0
CheckData=True
Encroach Param= -1, 0, 0, 0
BEGIN DESCRIPTION:
Multiple Run
END DESCRIPTION:

--- BRUSHYCREEKTRIB8.f01 (steady flow) ---

Flow Title=Multiple
Program Version=4.10
Number of Profiles= 7
Profile Names=10-year,25-year,50-year,1pct_min,100-year,1pct_plu,500-year
River Rch & RM=UNT05310 IN WICK,Reach-1         ,2873
     306     398     471     411     555     751     771
River Rch & RM=BRUSHYCRTR8,Reach-1         ,2873
     306     398     471     411     555     751     771
Boundary for River Rch & Prof#=BRUSHYCRTR8,Reach-1         , 1
Up Type= 0
Dn Type= 3
Dn Slope=0.005
Boundary for River Rch & Prof#=BRUSHYCRTR8,Reach-1         , 2
Up Type= 0
Dn Type= 3
Dn Slope=0.005
Boundary for River Rch & Prof#=BRUSHYCRTR8,Reach-1         , 3
Up Type= 0
Dn Type= 3
Dn Slope=0.005
Boundary for River Rch & Prof#=BRUSHYCRTR8,Reach-1         , 4
Up Type= 0
Dn Type= 3
Dn Slope=0.005
Boundary for River Rch & Prof#=BRUSHYCRTR8,Reach-1         , 5
Up Type= 0
Dn Type= 3
Dn Slope=0.005
Boundary for River Rch & Prof#=BRUSHYCRTR8,Reach-1         , 6
Up Type= 0
Dn Type= 3
Dn Slope=0.005
Boundary for River Rch & Prof#=BRUSHYCRTR8,Reach-1         , 7
Up Type= 0
Dn Type= 3
Dn Slope=0.005
DSS Import GetInterval= 0
DSS Import GetPeak= 0
DSS Import FillOption= 0

--- BRUSHYCREEKTRIB8.g01 (geometry) ---

Geom Title=Existing Conditions
Program Version=4.10

River Reach=BRUSHYCRTR8     ,Reach-1
Reach XY= 30
      3580531.16     10225932.13       3580647.8     10225980.11
      3580754.88     10225972.48      3580779.38     10226031.23
      3580742.93     10226082.68      3580757.85     10226129.23
      3581002.31     10226158.98      3581095.02     10226127.61
      3581123.04     10226257.98      3581205.99     10226232.07
      3581414.09     10226239.58      3581416.86     10226354.17
      3581459.92     10226365.97      3581507.14      10226338.2
      3581539.78     10226344.45      3581525.89      10226387.5
      3581566.86      10226425.7      3581566.17     10226481.95
      3581661.31      10226487.5      3581727.28     10226566.67
      3581768.71     10226529.94      3581883.42      10226677.9
      3581988.82     10226649.25      3582026.77     10226683.13
      3582004.32     10226748.02      3582106.99     10226739.25
      3582149.39     10226849.34      3582272.37     10226932.56
      3582424.53     10227085.34      3582422.11     10227211.64

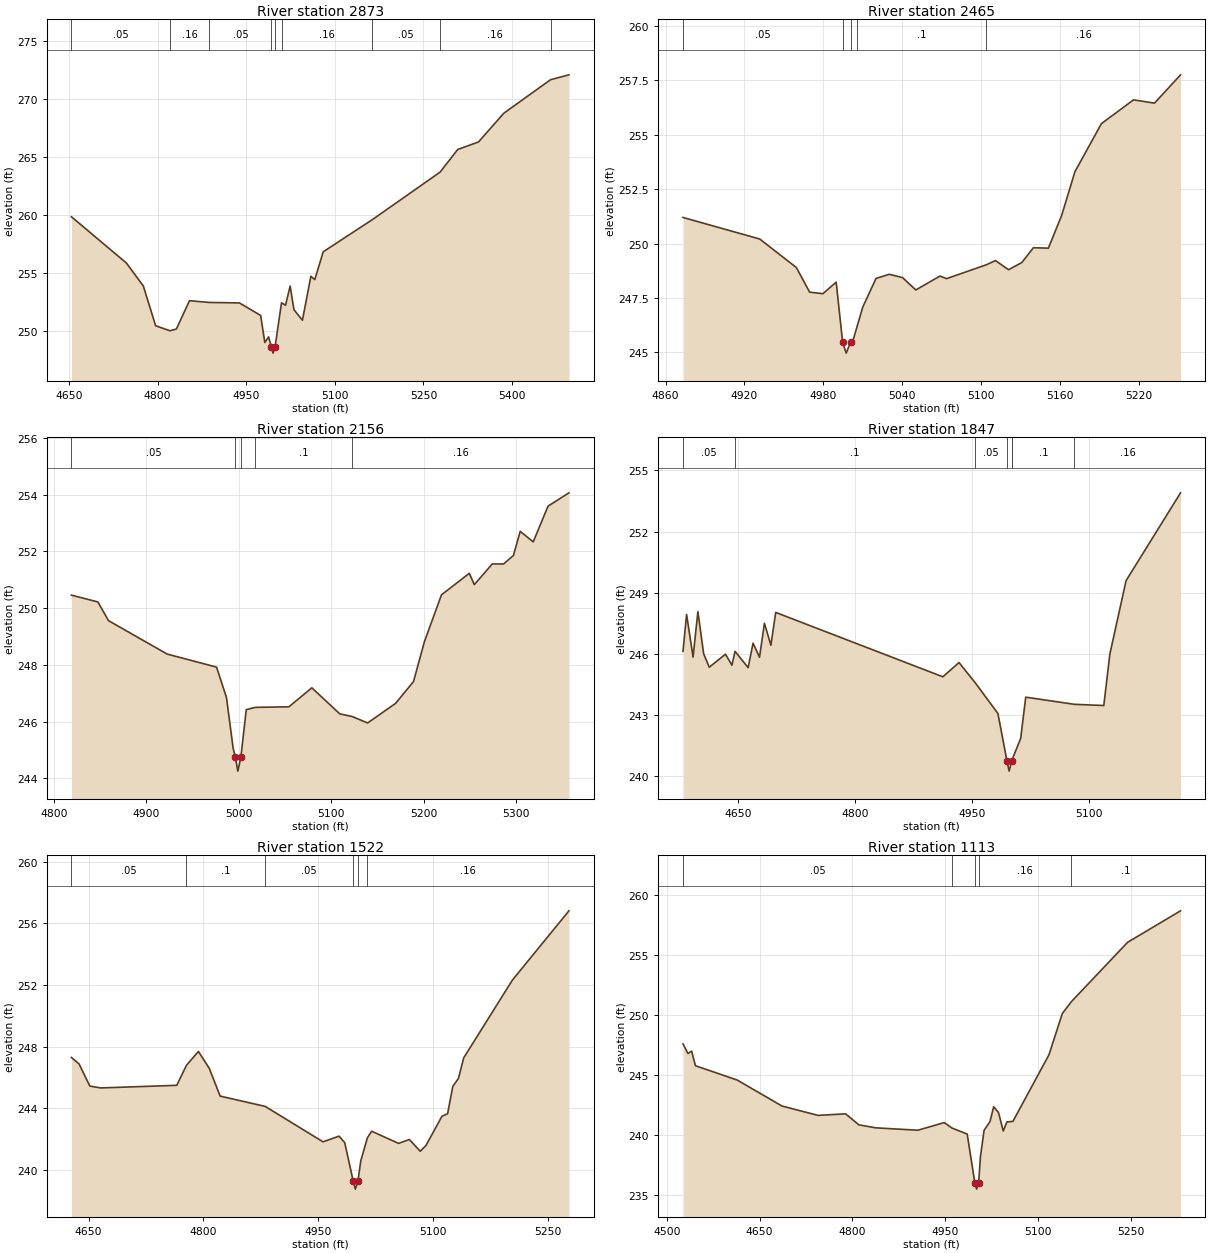
Type RM Length L Ch R = 1 ,2873    ,408,408,408
BEGIN DESCRIPTION:
UNT05310 IN WICK 5.0
END DESCRIPTION:
XS GIS Cut Line= 2
      3580506.49     10226227.06      3581047.63     10225581.85
#Sta/Elev= 30
  4654.1  259.81  4747.2  255.82  4775.8  253.84  4796.7  250.41  4820.7  249.98
  4831.8  250.13  4853.9  252.57  4887.5  252.42  4938.5  252.38  4974.4   251.3
  4981.4  248.97  4987.9  249.45  4992.7  248.55  4995.4  248.05  4998.7  248.55
  5009.7  252.39  5016.5  252.18  5024.3  253.83  5030.8  251.79  5045.1  250.89
  5059.4  254.68    5066  254.39  5080.3  256.79  5163.4  259.56  5278.1  263.66
  5307.9  265.61  5343.1  266.26    5386  268.74  5465.1  271.63  5496.2  272.05
#Mann= 9 ,-1 , 0
  4654.1     .05       0  4820.7     .16       0  4887.5     .05       0
  4992.7     .03       0  4998.7     .05       0  5009.7     .16       0
  5163.4     .05       0  5278.1     .16       0  5465.1      .1       0
Bank Sta=4992.7,4998.7
XS Rating Curve= 0 ,0
Exp/Cntr=0.3,0.1

Type RM Length L Ch R = 1 ,2465    ,309,309,309
BEGIN DESCRIPTION:
Mapping XS e9fddb75
END DESCRIPTION:
XS GIS Cut Line= 2
       3580929.3     10226267.06      3580982.25     10225892.08
#Sta/Elev= 30
  4873.2   251.2  4931.6  250.21  4959.5   248.9  4969.6  247.77  4979.7   247.7
  4989.8  248.23  4994.7  245.47  4997.4  244.97  5000.7  245.47  5002.7  245.57
  5005.5  246.15    5010  247.08  5020.1   248.4  5030.2  248.59  5040.3  248.44
  5050.4  247.87  5068.8  248.51  5073.8  248.39  5104.2  249.03    5111  249.22
    5121   248.8  5131.1  249.13  5139.9  249.81  5151.3  249.79  5161.4  251.29
  5171.5   253.3  5191.7  255.51  5216.1   256.6  5232.1  256.45  5251.9  257.75
#Mann= 5 ,-1 , 0
  4873.2     .05       0  4994.7     .03       0  5000.7     .05       0
  5005.5      .1       0  5104.2     .16       0
Bank Sta=4994.7,5000.7
XS Rating Curve= 0 ,0
Exp/Cntr=0.3,0.1

Type RM Length L Ch R = 1 ,2156    ,309,309,309
BEGIN DESCRIPTION:
UNT05310 IN WICK 4.0
END DESCRIPTION:
XS GIS Cut Line= 2
      3581064.47      10226428.4      3581255.11     10225925.52
#Sta/Elev= 30
  4819.1  250.46  4847.7  250.22  4859.2  249.56  4922.6  248.38    4976  247.92
  4986.7  246.85  4993.9  245.06  4996.3  244.75    4999  244.25  5002.3  244.75
  5008.1  246.42    5018   246.5  5054.2  246.52    5079  247.19  5109.2  246.27
  5122.3  246.18  5139.3  245.95  5169.5  246.64  5188.9  247.41  5200.6  248.81
  5219.1  250.47  5249.2  251.23  5254.6  250.83    5274  251.56  5286.2  251.56
  5296.9  251.86  5304.2  252.71  5318.3  252.34  5334.3   253.6  5356.9  254.07
#Mann= 5 ,-1 , 0
  4819.1     .05       0  4996.3     .03       0  5002.3     .05       0
    5018      .1       0  5122.3     .16       0
Bank Sta=4996.3,5002.3
XS Rating Curve= 0 ,0
Exp/Cntr=0.3,0.1

Type RM Length L Ch R = 1 ,1847    ,325,325,325
BEGIN DESCRIPTION:
Mapping XS e9439293
END DESCRIPTION:
XS GIS Cut Line= 2
      3581080.92     10226507.46      3581590.77     10226122.94
#Sta/Elev= 30
  4578.9  246.12  4583.5  247.93  4591.8  245.84    4598  248.07  4605.4     246
  4612.6  245.34  4633.4  245.98  4641.7  245.44  4645.7  246.12  4662.5  245.32
  4668.8  246.52  4677.1  245.83  4683.4   247.5  4691.7  246.42  4697.9  248.03
  4912.4  244.87  4933.2  245.57  4953.7  244.59  4983.1  243.07  4994.7  240.74
  4997.5  240.24  5000.7  240.74  5001.8  240.85  5012.3  241.84  5018.8  243.87
  5081.1  243.52    5119  243.46  5126.8  245.99  5147.6  249.59  5217.5   253.9
#Mann= 7 ,-1 , 0
  4578.9     .05       0  4645.7      .1       0  4953.7     .05       0
  4994.7     .03       0  5000.7     .05       0  5001.8      .1       0
  5081.1     .16       0
Bank Sta=4994.7,5000.7
XS Rating Curve= 0 ,0
Exp/Cntr=0.3,0.1

Type RM Length L Ch R = 1 ,1522    ,409,409,409
BEGIN DESCRIPTION:
UNT05310 IN WICK 3.0
END DESCRIPTION:
XS GIS Cut Line= 2
      3581278.55     10226662.26      3581756.48     10226221.85
#Sta/Elev= 30
  4627.6  247.29  4637.6  246.87  4651.7  245.43  4665.9  245.31  4765.2  245.48
  4777.9  246.78  4793.5  247.68  4807.7  246.58  4821.9  244.78  4880.8  244.11
  4956.3  241.81  4977.2  242.18  4984.6  241.76  4995.8  239.24  4998.5  238.74
  5001.8  239.24  5005.6  240.58  5014.2  242.07  5019.8   242.5  5054.9  241.71
  5069.1  241.96  5083.3   241.2  5090.7  241.57  5111.6  243.47    5119  243.64
  5125.8  245.41  5133.2  245.93    5140  247.26  5203.6  252.31  5277.5  256.81
#Mann= 6 ,-1 , 0
  4627.6     .05       0  4777.9      .1       0  4880.8     .05       0
  4995.8     .03       0  5001.8     .05       0  5014.2     .16       0
Bank Sta=4995.8,5001.8
XS Rating Curve= 0 ,0
Exp/Cntr=0.3,0.1

Type RM Length L Ch R = 1 ,1113    ,262,262,262
BEGIN DESCRIPTION:
UNT05310 IN WICK 2.0
END DESCRIPTION:
XS GIS Cut Line= 3
       3581404.9     10226813.59      3581942.11     10226491.64
      3582063.82     10226362.43
#Sta/Elev= 30
  4526.2  247.59  4534.2  246.79  4540.1  246.99  4546.3  245.77  4613.9  244.57
  4686.2   242.4  4744.4  241.62  4788.9  241.75  4810.3  240.83  4837.7  240.58
  4905.6  240.38  4948.3  241.02  4960.5  240.57  4985.3  240.06  4997.8  235.96
  5000.6  235.46  5003.8  235.96  5006.7  238.16  5012.6  240.37  5022.2  241.11
  5028.1  242.34  5035.9  241.86  5043.6  240.31  5049.4  241.07  5059.2  241.12
  5117.5  246.69  5138.9  250.12  5153.6  251.12  5244.5  256.08    5330  258.71
#Mann= 5 ,-1 , 0
  4526.2     .05       0  4960.5     .16       0  4997.8     .07       0
  5003.8     .16       0  5153.6      .1       0
Bank Sta=4997.8,5003.8
XS Rating Curve= 0 ,0
Exp/Cntr=0.3,0.1

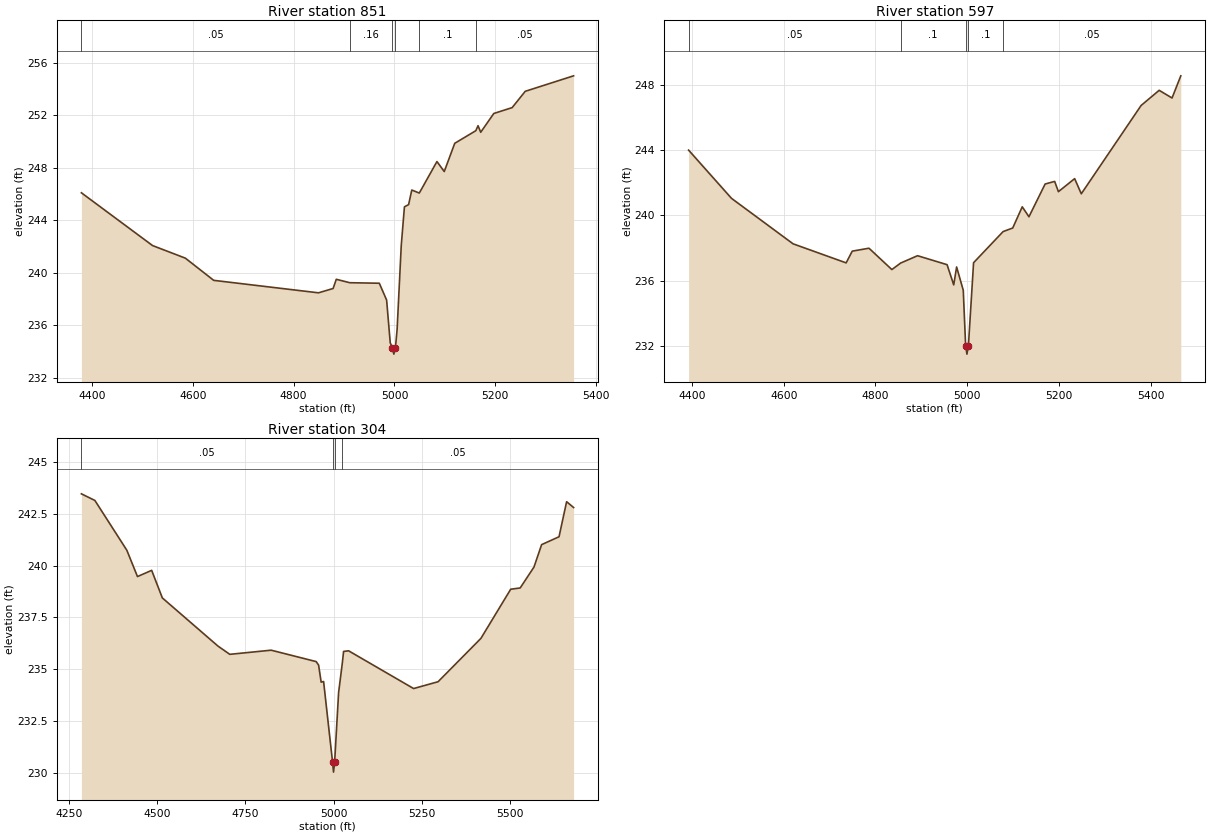
Type RM Length L Ch R = 1 ,851     ,254,254,254
BEGIN DESCRIPTION:
Mapping XS b8094614
END DESCRIPTION:
XS GIS Cut Line= 4
      3581484.79     10226999.96      3581657.01     10226917.38
      3582122.43     10226562.29      3582187.51      10226373.5
#Sta/Elev= 30
  4379.1   246.1  4520.2  242.08  4585.3  241.12  4641.5  239.43  4849.3  238.48
  4878.3  238.81  4884.6  239.51  4911.3  239.25  4969.9  239.21  4984.4  237.93
  4991.6  234.67  4995.9  234.31  4998.7  233.81  5001.9  234.31  5005.2  235.68
  5013.4  242.07  5019.7  245.03    5028   245.2  5034.3  246.31  5049.2  246.08
  5084.2  248.48  5098.7  247.72  5119.5  249.87  5161.3  250.83  5165.7  251.21
    5171  250.71  5196.9  252.14  5233.4  252.59  5259.3  253.83  5355.2  255.01
#Mann= 6 ,-1 , 0
  4379.1     .05       0  4911.3     .16       0  4995.9     .07       0
  5001.9     .16       0  5049.2      .1       0  5161.3     .05       0
Bank Sta=4995.9,5001.9
XS Rating Curve= 0 ,0
Exp/Cntr=0.3,0.1

Type RM Length L Ch R = 1 ,597     ,293,293,293
BEGIN DESCRIPTION:
Mapping XS b3f67877
END DESCRIPTION:
XS GIS Cut Line= 4
      3581604.57     10227067.68      3581831.13     10226981.74
      3582323.32     10226604.14      3582294.91     10226394.91
#Sta/Elev= 30
  4392.3  244.01  4485.9  241.05  4620.2  238.26    4736  237.09  4749.3  237.81
  4785.8  237.99  4835.7  236.68    4855  237.08  4891.8  237.53  4956.2  236.98
  4970.7  235.74    4977  236.84  4991.5  235.41  4996.7  231.99  4999.5  231.49
  5002.7  231.99    5014   237.1  5078.4  239.01  5099.4  239.23  5120.2  240.53
  5134.8  239.92  5170.1  241.93  5190.9  242.09  5199.1  241.46  5234.5  242.26
    5249  241.33  5379.5  246.75  5418.9  247.68    5447  247.21  5466.1  248.57
#Mann= 5 ,-1 , 0
  4392.3     .05       0    4855      .1       0  4996.7     .07       0
  5002.7      .1       0  5078.4     .05       0
Bank Sta=4996.7,5002.7
XS Rating Curve= 0 ,0
Exp/Cntr=0.3,0.1

Type RM Length L Ch R = 1 ,304     ,0,0,0
BEGIN DESCRIPTION:
UNT05310 IN WICK 1.0
END DESCRIPTION:
XS GIS Cut Line= 4
       3581654.1     10227164.03      3582145.26     10227116.49
      3582474.36     10226802.05      3582411.87     10226361.99
#Sta/Elev= 30
  4285.9  243.46  4324.1  243.14  4414.5  240.74  4444.6  239.47  4484.8  239.77
    4515  238.44  4672.3  236.12  4705.9  235.72    4823  235.92  4950.4  235.37
  4957.3   235.2  4964.5  234.38  4971.4  234.41  4996.7  230.54  4999.5  230.04
  5002.7  230.54  5013.9  233.88  5024.5  235.31    5028  235.86  5042.2  235.89
  5226.2  234.07  5295.5   234.4  5416.7  236.49    5501  238.86  5527.8  238.92
  5566.9  239.93  5588.5  241.01  5637.8  241.39  5659.2  243.08    5679   242.8
#Mann= 4 ,-1 , 0
  4285.9     .05       0  4996.7     .07       0  5002.7     .05       0
  5024.5     .05       0
Bank Sta=4996.7,5002.7
XS Rating Curve= 0 ,0
Exp/Cntr=0.3,0.1

Chan Stop Cuts=-1
Use User Specified Reach Order=0
Composite Channel Slope=5