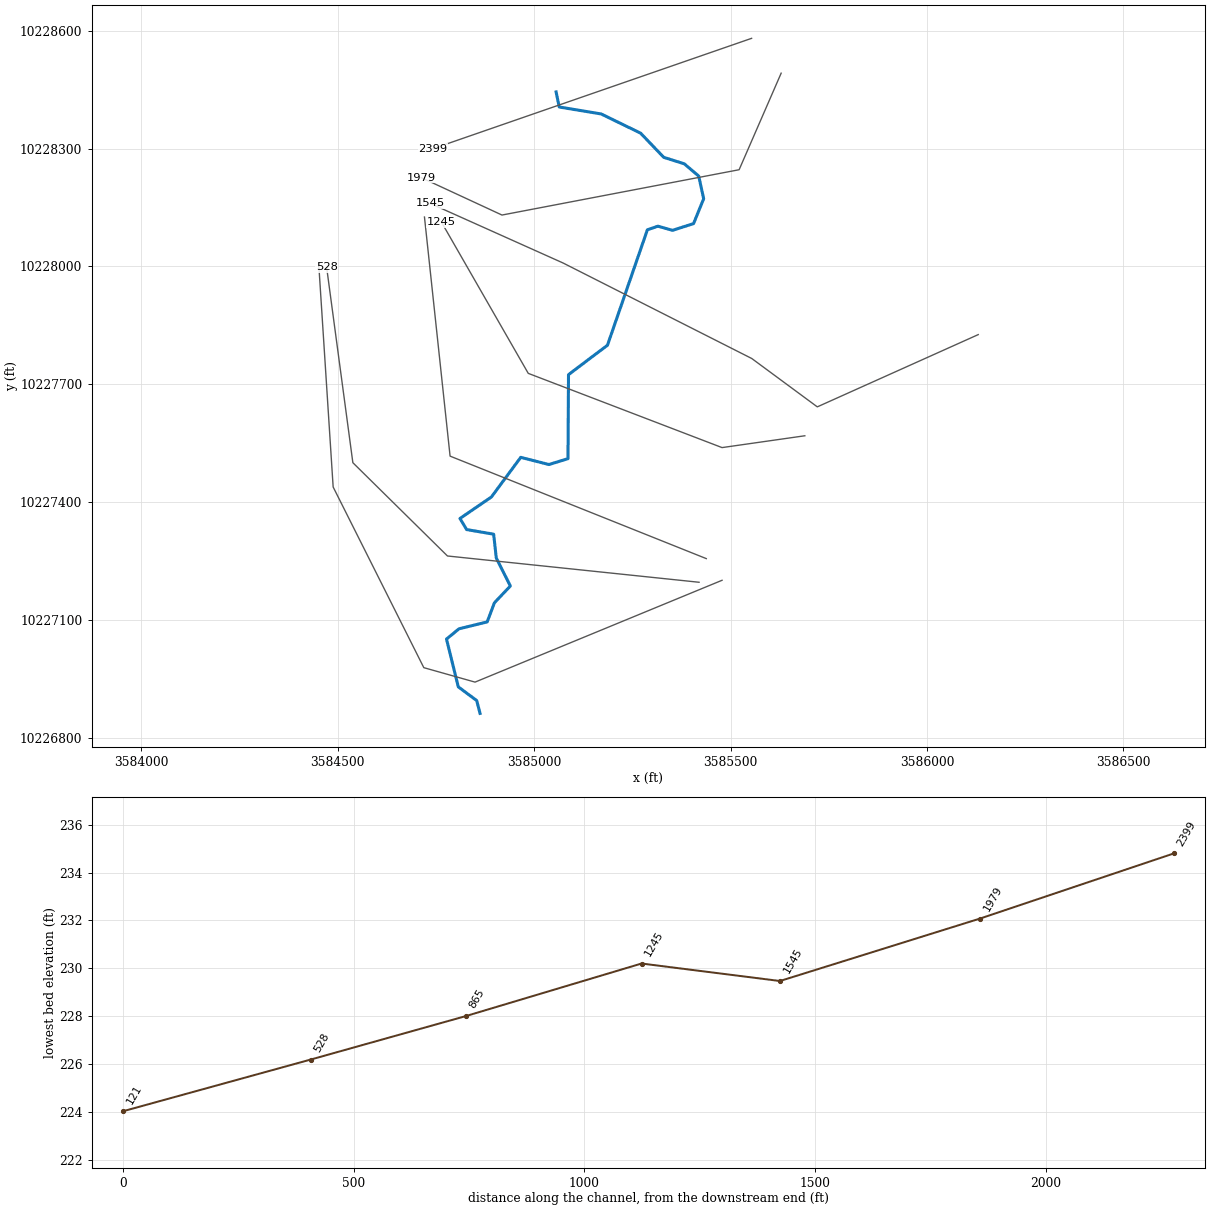
--- BRUSHY CREEK TRIBUTARY 6.prj (project) ---

Proj Title=BRUSHY CREEK TRIBUTARY 6 Base Level Engineering
Current Plan=p01
Default Exp/Contr=0.3,0.1
English Units
Geom File=g01
Flow File=f01
Plan File=p01
BEGIN DESCRIPTION:
BRUSHY CREEK TRIBUTARY 6
END DESCRIPTION:

--- BRUSHY CREEK TRIBUTARY 6.p01 (plan) ---

Plan Title=Multiple Run
Short Identifier=Multiple
Geom File=g01
Flow File=f01
Subcritical Flow
K Sum by GR= 0
Std Step Tol= 0.01
Critical Tol= 0.01
Num of Std Step Trials= 20
Max Error Tol= 0.3
Flow Tol Ratio= 0.001
Split Flow NTrial= 30
Split Flow Tol= 0.02
Split Flow Ratio= 0.02
Log Output Level= 0
Friction Slope Method= 1
Unsteady Friction Slope Method= 2
Unsteady Bridges Friction Slope Method= 1
Parabolic Critical Depth
Global Vel Dist=  1 , 1 , 1
Global Log Level= 0
CheckData=True
Encroach Param= -1, 0, 0, 0
BEGIN DESCRIPTION:
Multiple Run
END DESCRIPTION:

--- BRUSHY CREEK TRIBUTARY 6.f01 (steady flow) ---

Flow Title=Multiple
Number of Profiles=7
Profile Names=10-year,25-year,50-year,1pct_min,100-year,1pct_plu,500-year
River Rch & RM= BRUSHY CREEK TRI,Reach-1,2399
     615     830    1006     893    1208    1633    1744
Boundary for River Rch & Prof#=BRUSHY CREEK TRI,Reach-1,1
Up Type=0
Dn Type=3
Dn Slope=0.005
Boundary for River Rch & Prof#=BRUSHY CREEK TRI,Reach-1,2
Up Type=0
Dn Type=3
Dn Slope=0.005
Boundary for River Rch & Prof#=BRUSHY CREEK TRI,Reach-1,3
Up Type=0
Dn Type=3
Dn Slope=0.005
Boundary for River Rch & Prof#=BRUSHY CREEK TRI,Reach-1,4
Up Type=0
Dn Type=3
Dn Slope=0.005
Boundary for River Rch & Prof#=BRUSHY CREEK TRI,Reach-1,5
Up Type=0
Dn Type=3
Dn Slope=0.005
Boundary for River Rch & Prof#=BRUSHY CREEK TRI,Reach-1,6
Up Type=0
Dn Type=3
Dn Slope=0.005
Boundary for River Rch & Prof#=BRUSHY CREEK TRI,Reach-1,7
Up Type=0
Dn Type=3
Dn Slope=0.005

--- BRUSHY CREEK TRIBUTARY 6.g01 (geometry) ---

Geom Title=Existing Conditions

River Reach=BRUSHY CREEK TRI,Reach-1
Reach XY= 30
      3585055.77     10228443.99      3585063.77     10228405.66
      3585170.56     10228387.96      3585270.95     10228339.07
      3585329.80     10228277.58      3585382.11     10228261.00
      3585418.93     10228229.79      3585431.52     10228172.04
      3585405.76     10228108.75      3585352.11     10228091.64
      3585314.97     10228102.22      3585288.21     10228093.00
      3585186.52     10227799.07      3585087.34     10227724.19
      3585086.04     10227510.25      3585037.49     10227495.28
      3584965.71     10227513.57      3584890.92     10227412.56
      3584810.96     10227357.91      3584828.04     10227329.63
      3584896.76     10227317.96      3584903.45     10227257.32
      3584939.28     10227185.95      3584898.77     10227143.32
      3584880.21     10227094.49      3584808.69     10227077.07
      3584776.67     10227050.89      3584806.71     10226929.09
      3584853.47     10226894.38      3584862.11     10226861.64

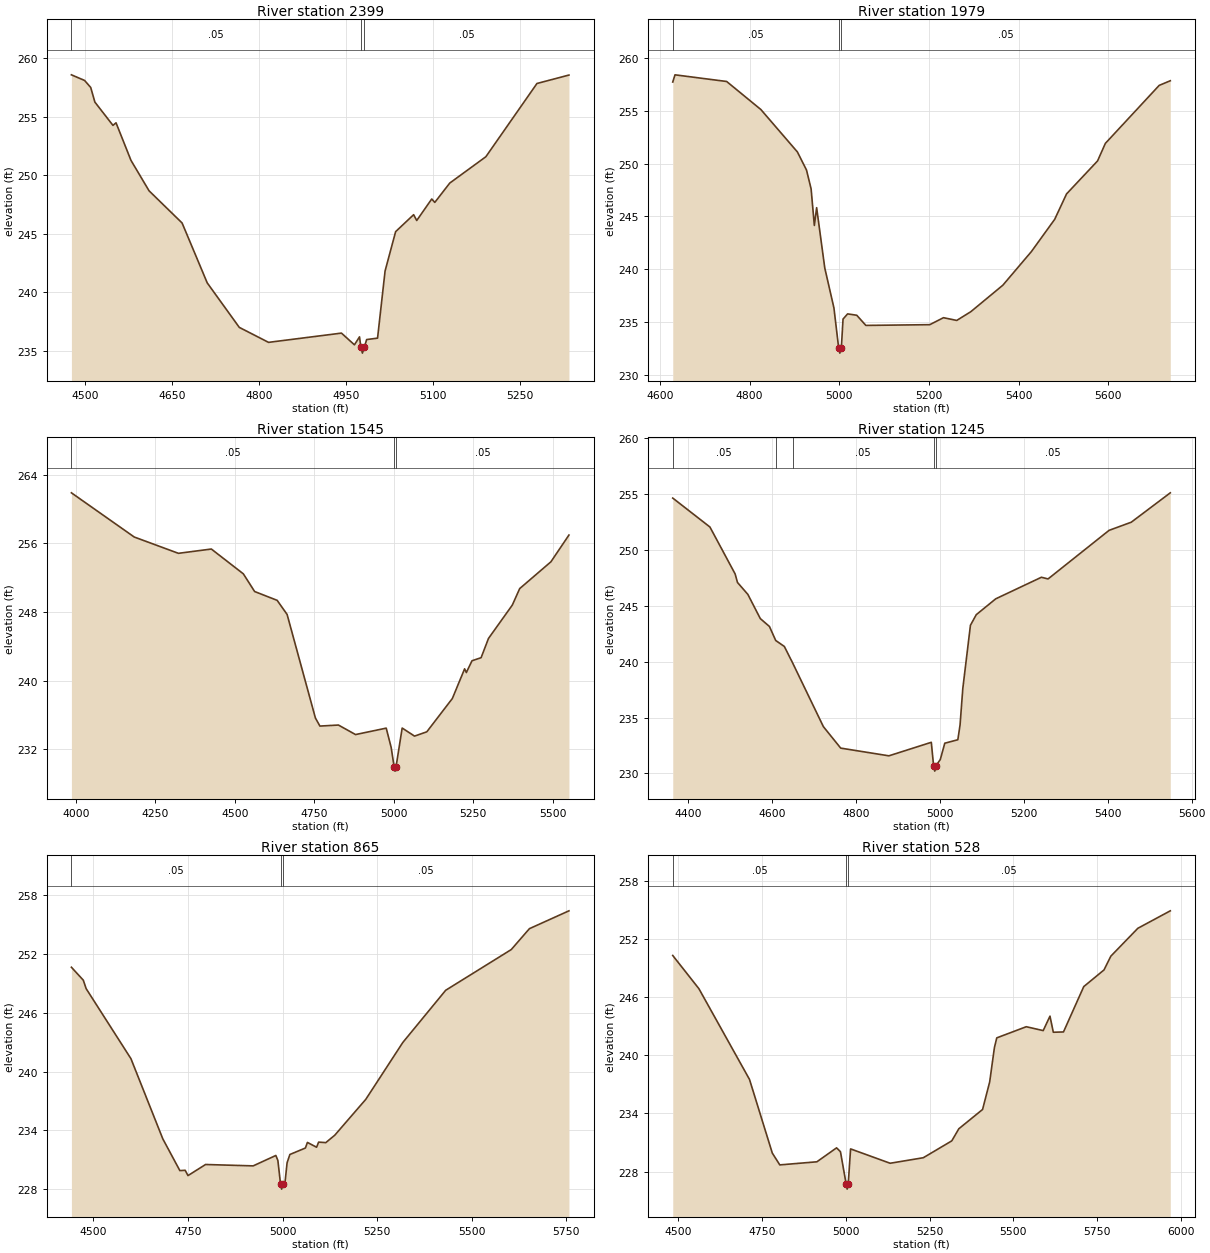
Type RM Length L Ch R = 1,2399,420,420,420
BEGIN DESCRIPTION:
UNT05313 IN WICK 3.5
END DESCRIPTION:
XS GIS Cut Line= 2
      3585553.57     10228580.54      3584742.26     10228299.51
#Sta/Elev= 30
  4476.7  258.58  4499.4  258.10  4510.0  257.50  4517.2  256.25  4548.4  254.26
  4553.7  254.48  4579.5  251.27  4610.7  248.67  4667.7  245.92  4711.1  240.80
  4766.4  237.00  4816.9  235.72  4942.7  236.51  4965.1  235.51  4973.9  236.19
  4976.2  235.30  4978.9  234.80  4982.2  235.30  4986.2  235.96  5005.0  236.08
  5018.0  241.82  5036.2  245.18  5067.3  246.63  5072.6  246.13  5098.5  247.97
  5103.8  247.68  5129.6  249.33  5191.9  251.58  5280.1  257.84  5335.3  258.56
#Mann=3,-1,0
  4476.7    0.05       0  4976.2    0.03       0  4982.2    0.05       0
Bank Sta=4976.2,4982.2
Exp/Cntr=0.3,0.1

Type RM Length L Ch R = 1,1979,434,434,434
BEGIN DESCRIPTION:
Mapping XS bf2eaa6c
END DESCRIPTION:
XS GIS Cut Line= 4
      3585628.85     10228491.85      3585521.81     10228245.99
      3584917.95     10228130.57      3584712.20     10228225.92
#Sta/Elev= 30
  4628.7  257.71  4633.7  258.39  4748.9  257.76  4825.2  255.11  4906.7  251.10
  4927.1  249.38  4937.3  247.60  4944.5  244.15  4949.6  245.83  4967.8  240.12
  4988.2  236.35  4998.7  232.58  5001.4  232.08  5004.7  232.58  5008.5  235.30
  5018.7  235.79  5039.1  235.66  5059.4  234.70  5202.0  234.77  5232.5  235.43
  5262.1  235.17  5293.6  236.00  5364.9  238.50  5428.6  241.68  5480.6  244.73
  5507.0  247.13  5576.2  250.25  5593.6  251.91  5713.6  257.39  5738.4  257.83
#Mann=3,-1,0
  4628.7    0.05       0  4998.7   0.035       0  5004.7    0.05       0
Bank Sta=4998.7,5004.7
Exp/Cntr=0.3,0.1

Type RM Length L Ch R = 1,1545,300,300,300
BEGIN DESCRIPTION:
Mapping XS 20a924b4
END DESCRIPTION:
XS GIS Cut Line= 5
      3586130.71     10227826.14      3585720.87     10227642.13
      3585554.08     10227765.20      3585073.51     10228008.46
      3584735.48     10228160.00
#Sta/Elev= 30
  3985.8  261.90  4183.5  256.75  4322.5  254.85  4426.1  255.35  4526.8  252.46
  4562.3  250.40  4633.2  249.37  4664.5  247.73  4753.6  235.66  4767.8  234.72
  4826.1  234.84  4879.9  233.73  4976.4  234.48  4992.0  232.23  5001.3  229.97
  5004.1  229.47  5007.3  229.97  5026.6  234.49  5065.5  233.55  5104.1  234.05
  5184.5  237.93  5223.1  241.39  5228.6  240.96  5246.3  242.33  5275.0  242.69
  5298.2  244.93  5373.2  248.82  5396.4  250.74  5494.6  253.86  5551.4  256.98
#Mann=3,-1,0
  3985.8    0.05       0  5001.3    0.03       0  5007.3    0.05       0
Bank Sta=5001.3,5007.3
Exp/Cntr=0.3,0.1

Type RM Length L Ch R = 1,1245,380,380,380
BEGIN DESCRIPTION:
Mapping XS 85d85fff
END DESCRIPTION:
XS GIS Cut Line= 4
      3585689.12     10227568.54      3585478.32     10227538.42
      3584984.86     10227727.44      3584764.03     10228112.21
#Sta/Elev= 30
  4364.1  254.65  4452.6  252.06  4512.6  247.86  4518.3  247.09  4542.9  246.03
  4572.6  243.86  4594.4  243.15  4609.3  241.90  4629.9  241.36  4649.6  239.89
  4722.9  234.18  4764.1  232.26  4878.9  231.57  4979.9  232.78  4985.3  230.70
  4988.1  230.20  4991.3  230.70  5001.3  231.24  5012.0  232.70  5043.1  233.01
  5048.4  234.34  5054.9  237.59  5073.1  243.26  5087.0  244.21  5133.4  245.63
  5242.2  247.56  5258.0  247.41  5403.3  251.76  5456.2  252.49  5549.1  255.12
#Mann=5,-1,0
  4364.1    0.05       0  4609.3     0.1       0  4649.6    0.05       0
  4985.3    0.03       0  4991.3    0.05       0
Bank Sta=4985.3,4991.3
Exp/Cntr=0.3,0.1

Type RM Length L Ch R = 1,865,337,337,337
BEGIN DESCRIPTION:
Mapping XS ae3a1905
END DESCRIPTION:
XS GIS Cut Line= 3
      3585438.19     10227255.72      3584785.80     10227516.68
      3584720.56     10228125.54
#Sta/Elev= 30
  4441.7  250.63  4473.1  249.31  4480.6  248.45  4599.0  241.31  4683.2  233.14
  4728.3  229.90  4742.4  229.93  4749.8  229.39  4796.3  230.52  4922.1  230.38
  4982.0  231.44  4987.4  230.93  4994.5  228.51  4997.3  228.01  5000.5  228.51
  5006.3  228.70  5011.7  230.69  5019.1  231.54  5060.1  232.20  5065.5  232.77
  5089.7  232.28  5095.1  232.80  5114.0  232.75  5137.6  233.50  5219.7  237.16
  5317.6  242.96  5430.9  248.28  5604.2  252.43  5652.2  254.56  5756.7  256.38
#Mann=3,-1,0
  4441.7    0.05       0  4994.5    0.03       0  5000.5    0.05       0
Bank Sta=4994.5,5000.5
Exp/Cntr=0.3,0.1

Type RM Length L Ch R = 1,528,407,407,407
BEGIN DESCRIPTION:
Mapping XS 0ff012ba
END DESCRIPTION:
XS GIS Cut Line= 4
      3585419.82     10227195.50      3584779.11     10227262.42
      3584538.23     10227499.95      3584471.45     10227997.50
#Sta/Elev= 30
  4483.9  250.30  4562.0  246.87  4712.9  237.51  4780.9  229.91  4803.3  228.69
  4913.9  229.01  4972.7  230.45  4984.3  230.05  5001.4  226.69  5004.2  226.19
  5007.4  226.69  5014.5  230.34  5132.5  228.86  5231.5  229.43  5316.4  231.17
  5337.5  232.42  5408.3  234.41  5429.5  237.25  5443.7  240.81  5450.7  241.80
  5538.7  242.95  5589.2  242.55  5609.4  244.04  5619.4  242.38  5649.7  242.41
  5710.2  247.09  5770.6  248.81  5791.0  250.23  5871.7  253.11  5968.4  254.91
#Mann=3,-1,0
  4483.9    0.05       0  5001.4    0.03       0  5007.4    0.05       0
Bank Sta=5001.4,5007.4
Exp/Cntr=0.3,0.1

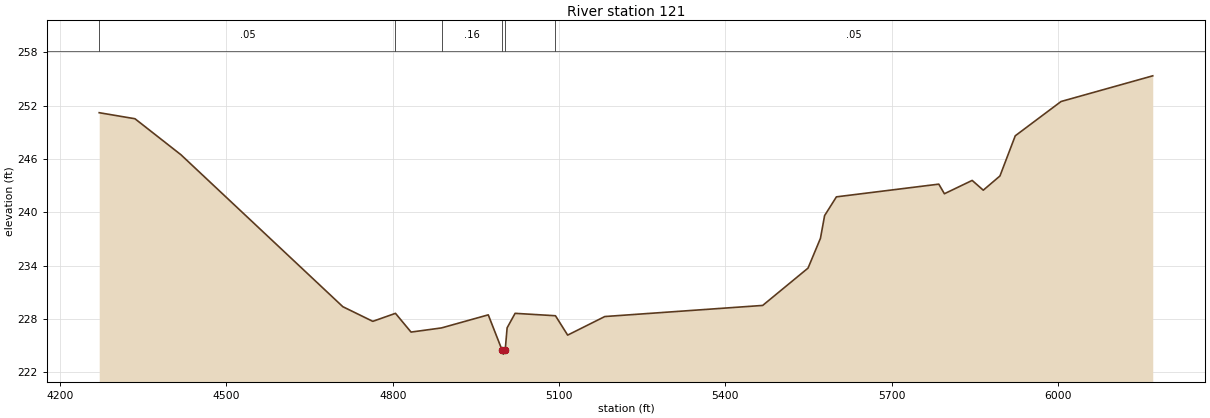
Type RM Length L Ch R = 1,121,0,0,0
BEGIN DESCRIPTION:
UNT05313 IN WICK 1.1
END DESCRIPTION:
XS GIS Cut Line= 5
      3585478.35     10227200.54      3584849.36     10226941.25
      3584718.89     10226978.05      3584488.05     10227438.06
      3584451.26     10228006.69
#Sta/Elev= 30
  4270.6  251.20  4335.1  250.52  4418.0  246.47  4710.0  229.37  4764.1  227.72
  4805.0  228.62  4833.1  226.51  4888.1  226.98  4972.4  228.45  4997.0  224.53
  4999.8  224.03  5003.0  224.53  5006.4  226.99  5020.8  228.62  5093.6  228.35
  5115.6  226.17  5182.6  228.26  5467.4  229.51  5549.2  233.71  5571.6  237.06
  5579.1  239.62  5600.4  241.73  5785.1  243.16  5795.2  242.08  5845.3  243.58
  5865.3  242.48  5895.4  244.08  5923.0  248.60  6005.6  252.46  6171.0  255.35
#Mann=6,-1,0
  4270.6    0.05       0  4805.0     0.1       0  4888.1    0.16       0
  4997.0    0.07       0  5003.0    0.16       0  5093.6    0.05       0
Bank Sta=4997,5003
Exp/Cntr=0.3,0.1

Chan Stop Cuts=-1