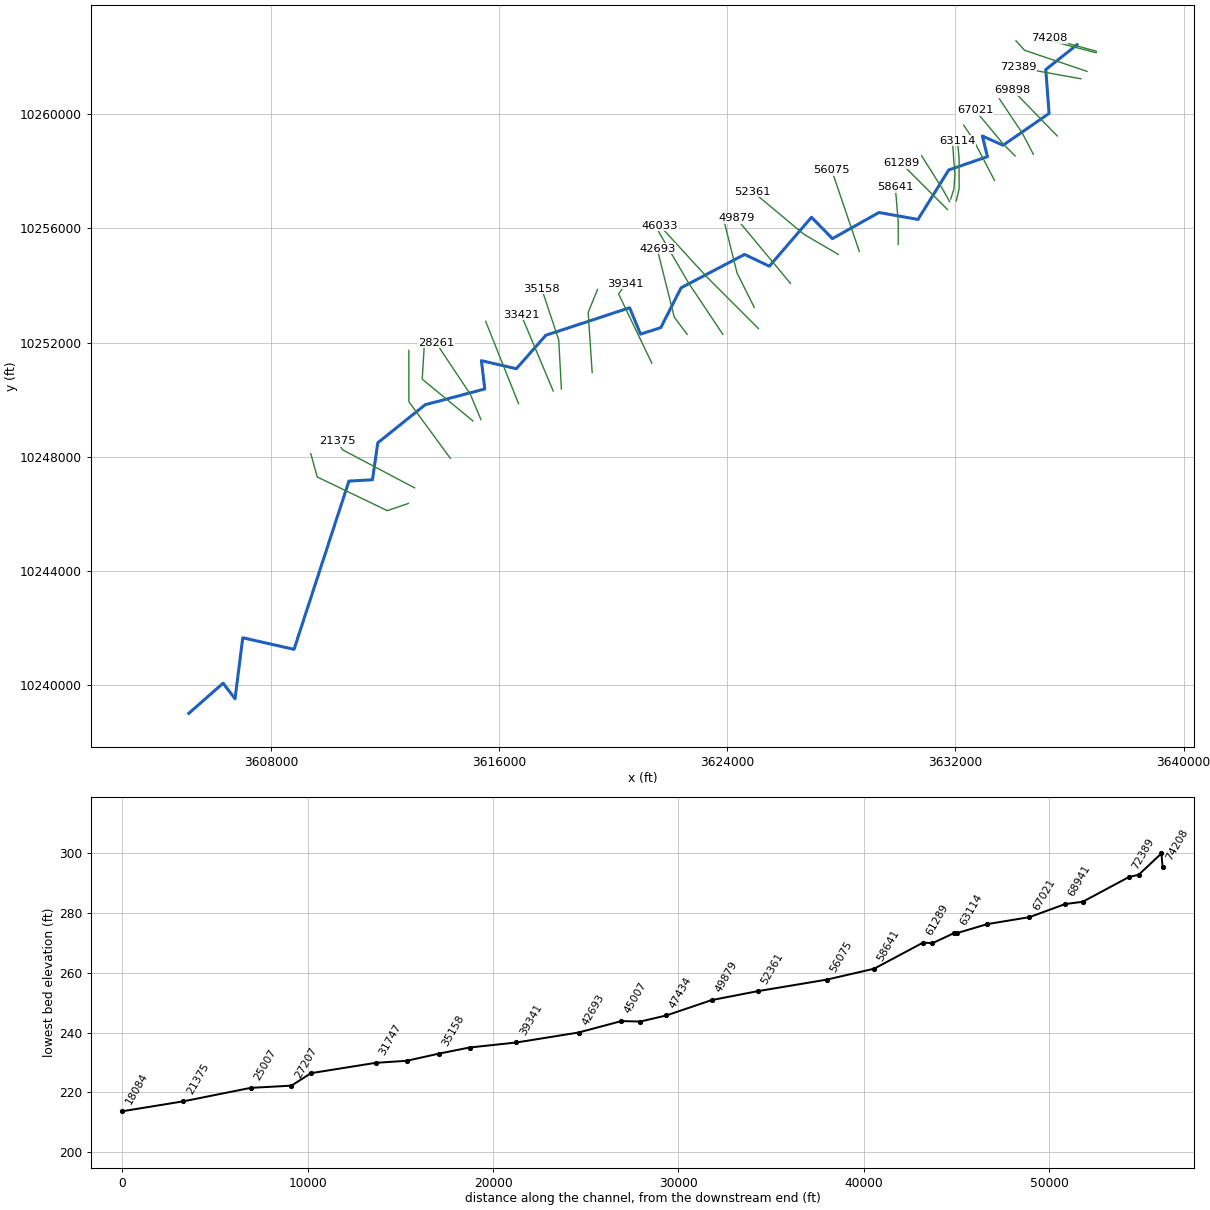
--- BULL CREEK.prj (project) ---

Proj Title=BULL CREEK Base Level Engineering
Current Plan=p01
Default Exp/Contr=0.3,0.1
English Units
Geom File=g01
Flow File=f01
Plan File=p01
Y Axis Title=Elevation
X Axis Title(PF)=Main Channel Distance
X Axis Title(XS)=Station
BEGIN DESCRIPTION:
BULL CREEK
END DESCRIPTION:
DSS Export Rating Curves= 0
DSS Export Rating Curve Sorted= 0
DSS Export Volume Flow Curves= 0
DXF OffsetX= 0
DXF OffsetY= 0
DXF ScaleX= 1
DXF ScaleY= 10

--- BULL CREEK.p01 (plan) ---

Plan Title=Multiple Run
Short Identifier=Multiple
Geom File=g01
Flow File=f01
Subcritical Flow
K Sum by GR= 0
Std Step Tol= 0.01
Critical Tol= 0.01
Num of Std Step Trials= 20
Max Error Tol= 0.3
Flow Tol Ratio= 0.001
Split Flow NTrial= 30
Split Flow Tol= 0.02
Split Flow Ratio= 0.02
Log Output Level= 0
Friction Slope Method= 1
Unsteady Friction Slope Method= 2
Unsteady Bridges Friction Slope Method= 1
Parabolic Critical Depth
Global Vel Dist=  1 , 1 , 1
Global Log Level= 0
CheckData=True
Encroach Param= -1, 0, 0, 0
BEGIN DESCRIPTION:
Multiple Run
END DESCRIPTION:

--- BULL CREEK.f01 (steady flow) ---

Flow Title=Multiple
Program Version=4.10
Number of Profiles= 7
Profile Names=10-year,25-year,50-year,1pct_min,100-year,1pct_plu,500-year
River Rch & RM=BULL CREEK,Reach-1         ,74208
     692     938    1140    1016    1374    1858    1998
River Rch & RM=BULL CREEK,Reach-1         ,72921
     990    1362    1672    1502    2032    2748    3004
River Rch & RM=BULL CREEK,Reach-1         ,68941
    1144    1576    1935    1736    2348    3175    3465
River Rch & RM=BULL CREEK,Reach-1         ,58641
    1706    2386    2960    2680    3624    4901    5444
River Rch & RM=BULL CREEK,Reach-1         ,49879
    1793    2507    3107    2810    3800    5139    5697
River Rch & RM=BULL CREEK,Reach-1         ,47434
    2045    2871    3569    3236    4376    5919    6595
River Rch & RM=BULL CREEK,Reach-1         ,39341
    2091    2931    3639    3295    4456    6027    6698
River Rch & RM=BULL CREEK,Reach-1         ,35158
    2177    3050    3786    3425    4633    6265    6952
River Rch & RM=BULL CREEK,Reach-1         ,28261
    2200    3075    3811    3442    4655    6295    6960
River Rch & RM=BULL CREEK,Reach-1         ,16057
    2341    3270    4051    3655    4942    6684    7376
Boundary for River Rch & Prof#=BULL CREEK,Reach-1         , 1
Up Type= 0
Dn Type= 3
Dn Slope=0.001
Boundary for River Rch & Prof#=BULL CREEK,Reach-1         , 2
Up Type= 0
Dn Type= 3
Dn Slope=0.001
Boundary for River Rch & Prof#=BULL CREEK,Reach-1         , 3
Up Type= 0
Dn Type= 3
Dn Slope=0.001
Boundary for River Rch & Prof#=BULL CREEK,Reach-1         , 4
Up Type= 0
Dn Type= 3
Dn Slope=0.001
Boundary for River Rch & Prof#=BULL CREEK,Reach-1         , 5
Up Type= 0
Dn Type= 3
Dn Slope=0.001
Boundary for River Rch & Prof#=BULL CREEK,Reach-1         , 6
Up Type= 0
Dn Type= 3
Dn Slope=0.001
Boundary for River Rch & Prof#=BULL CREEK,Reach-1         , 7
Up Type= 0
Dn Type= 3
Dn Slope=0.001
DSS Import GetInterval= 0
DSS Import GetPeak= 0
DSS Import FillOption= 0

--- BULL CREEK.g01 (geometry) ---

Geom Title=Existing Conditions
Program Version=4.10

River Reach=BULL CREEK      ,Reach-1
Reach XY= 30
      3636260.93     10262441.77      3635165.47     10261570.09
      3635281.67     10260033.73      3633666.33     10258916.18
      3632942.06     10259241.32      3633119.72     10258517.22
      3631763.01      10258050.6      3630684.41     10256316.43
      3629318.13     10256559.63      3627687.16     10255645.13
      3626951.99     10256392.07      3625474.83     10254677.03
      3624607.05     10255090.13      3622382.07     10253921.55
      3621671.12     10252524.99      3620959.72     10252296.78
      3620577.48     10253220.28      3617639.09     10252255.86
      3616606.56     10251083.14       3615381.2     10251365.93
      3615500.78     10250374.08      3613412.11     10249821.64
      3611749.72     10248488.28      3611562.96     10247191.06
      3610737.41     10247144.33       3608812.7     10241246.45
      3607015.66     10241651.97      3606744.22     10239514.45
      3606327.49     10240059.37      3605122.11     10239001.64

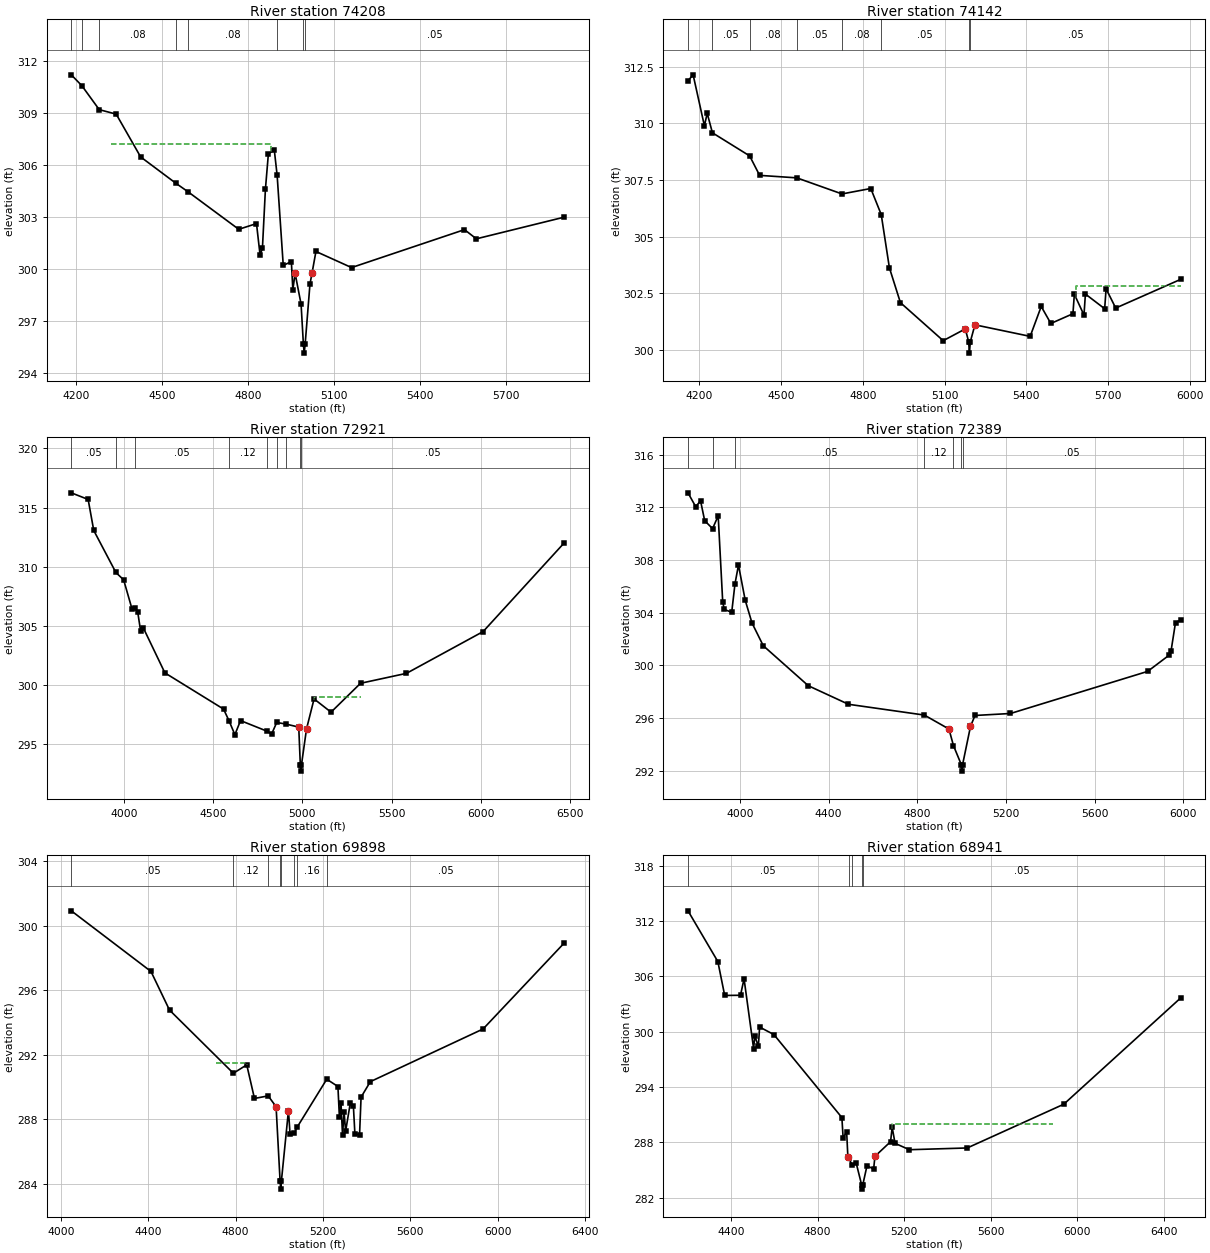
Type RM Length L Ch R = 1 ,74208   ,66,66,66
BEGIN DESCRIPTION:
BULL CREEK 85.0
END DESCRIPTION:
XS GIS Cut Line= 2
      3636935.45     10262214.86      3635276.83     10262665.32
#Sta/Elev= 30
  4183.5  311.22  4220.4  310.59  4280.9  309.21  4340.1  308.95  4425.3  306.48
  4548.1  304.96  4591.2  304.46  4767.5   302.3  4829.4  302.63  4841.9  300.81
  4850.1  301.21  4860.5  304.61  4870.9  306.67  4891.6  306.86  4901.4  305.42
  4922.7  300.22    4951  300.43  4956.2  298.82  4964.1  299.75  4984.9  297.98
    4993  295.65  4995.7  295.15    4999  295.65  5015.9  299.14 5023.31  299.79
  5036.7  301.02    5161  300.09  5554.8  302.28  5596.2  301.75  5902.2     303
#Mann= 8 ,-1 , 0
  4183.5     .08       0  4220.4     .05       0  4280.9     .08       0
  4548.1     .05       0  4591.2     .08       0  4901.4     .05       0
    4993     .04       0    4999     .05       0
#XS Ineff= 1 ,-1
 4320.64 4880.05  307.25
Permanent Ineff=
       F
Bank Sta=4964.1,5023.31
XS Rating Curve= 0 ,0
Exp/Cntr=0.3,0.1

Type RM Length L Ch R = 1 ,74142   ,1221,1221,1221
BEGIN DESCRIPTION:
Mapping XS b0daa026
END DESCRIPTION:
XS GIS Cut Line= 2
      3636930.26     10262160.17      3635182.91     10262615.89
#Sta/Elev= 30
  4159.8  311.88  4178.6  312.14  4219.9  309.89  4230.2  310.44  4249.3  309.58
  4385.7  308.56  4422.3   307.7  4558.6  307.59  4724.2  306.88  4829.6  307.12
  4867.9  305.97  4897.8  303.62  4938.2  302.08    5095   300.4    5176  300.92
  5188.3  300.35  5191.1  299.85  5194.3  300.35  5211.3   301.1  5413.7  300.59
  5454.2  301.91  5489.5  301.16  5570.4  301.59  5575.6  302.45  5610.9  301.53
  5616.1  302.46  5686.7  301.81  5691.9  302.69  5727.2  301.84  5965.6  303.11
#Mann= 8 ,-1 , 0
  4159.8     .08       0  4249.3     .05       0  4385.7     .08       0
  4558.6     .05       0  4724.2     .08       0  4867.9     .05       0
  5188.3     .04       0  5194.3     .05       0
#XS Ineff= 1 ,-1
 5582.72 5976.12  302.81
Permanent Ineff=
       F
Bank Sta=5176,5211.3
XS Rating Curve= 0 ,0
Exp/Cntr=0.3,0.1

Type RM Length L Ch R = 1 ,72921   ,532,532,532
BEGIN DESCRIPTION:
BULL CREEK 83.0
END DESCRIPTION:
XS GIS Cut Line= 3
      3636609.71     10261507.55      3634422.17     10262247.15
      3634120.11     10262580.46
#Sta/Elev= 30
    3706  316.24  3800.3  315.68  3831.7  313.06  3955.6  309.51    3999  308.89
  4046.6  306.39  4061.3  306.52    4078  306.16    4094  304.57  4109.5  304.82
    4230  301.03  4558.5  297.97  4589.4  296.97  4621.8  295.81  4653.5     297
  4800.7  296.11  4827.4  295.86  4856.1  296.84  4906.3  296.71  4979.4  296.45
  4988.3  293.23  4991.1  292.73  4994.3  293.23    5023   296.3  5065.2  298.83
  5160.2  297.71  5325.3  300.15  5582.5  300.99  6011.8  304.52    6465     312
#Mann= 9 ,-1 , 0
    3706     .05       0  3955.6     .08       0  4061.3     .05       0
  4589.4     .12       0  4800.7     .16       0  4856.1     .12       0
  4906.3     .05       0  4988.3     .03       0  4994.3     .05       0
#XS Ineff= 1 ,-1
 5063.96 5326.61  299.01
Permanent Ineff=
       F
Bank Sta=4979.4,5023
XS Rating Curve= 0 ,0
Exp/Cntr=0.3,0.1

Type RM Length L Ch R = 1 ,72389   ,2491,2491,2491
BEGIN DESCRIPTION:
BULL CREEK 81.0
END DESCRIPTION:
XS GIS Cut Line= 2
      3636396.16     10261247.15      3634208.68     10261642.97
#Sta/Elev= 30
  3765.7  313.11  3800.3  312.06  3822.4   312.5    3841  310.99  3876.6  310.39
  3901.9  311.36  3922.3  304.82  3929.3  304.25  3962.9  304.03  3977.7   306.2
  3993.4  307.62  4023.9  304.94  4054.4  303.22  4105.2  301.49  4308.4  298.45
  4489.6  297.04  4831.9  296.22  4942.9  295.16  4963.2   293.9  4998.5  292.46
  5001.2  291.96  5004.5  292.46  5040.1  295.36  5060.4  296.19  5220.5  296.34
  5839.3  299.54  5934.4  300.75  5944.6  301.07  5964.9  303.25  5988.7  303.44
#Mann= 7 ,-1 , 0
  3765.7     .05       0  3876.6     .08       0  3977.7     .05       0
  4831.9     .12       0  4963.2     .05       0  4998.5     .03       0
  5004.5     .05       0
Bank Sta=4942.9,5040.1
XS Rating Curve= 0 ,0
Exp/Cntr=0.3,0.1

Type RM Length L Ch R = 1 ,69898   ,957,957,957
BEGIN DESCRIPTION:
BULL CREEK 78.0
END DESCRIPTION:
XS GIS Cut Line= 3
      3635568.03     10259241.92       3634000.3     10260856.52
       3634000.3     10260851.31
#Sta/Elev= 30
  4047.8  300.91  4412.4  297.16  4497.3  294.77  4789.6  290.86  4850.9  291.38
  4886.2   289.3    4949  289.46  4985.2  288.79  5003.5  284.19  5006.3  283.69
  5009.5  284.19  5041.8  288.55    5049  287.12  5069.4  287.18    5081  287.51
  5217.1  290.49  5268.2  290.04  5275.1  288.13  5282.3  289.01  5289.3  287.04
  5296.5  288.47  5303.4  287.27  5324.7     289  5338.9  288.86  5345.9  287.12
  5367.2  287.03  5374.2  289.38  5416.6  290.34  5932.8   293.6  6303.5  298.91
#Mann= 8 ,-1 , 0
  4047.8     .05       0  4789.6     .12       0    4949     .16       0
  5003.5     .07       0  5009.5     .16       0  5069.4     .05       0
    5081     .16       0  5217.1     .05       0
#XS Ineff= 1 ,-1
 4710.63 4851.34  291.49
Permanent Ineff=
       F
Bank Sta=4985.2,5041.8
XS Rating Curve= 0 ,0
Exp/Cntr=0.3,0.1

Type RM Length L Ch R = 1 ,68941   ,1920,1920,1920
BEGIN DESCRIPTION:
BULL CREEK 76.0
END DESCRIPTION:
XS GIS Cut Line= 3
      3634729.45     10258601.34      3634342.11     10259341.64
      3633542.13     10260541.61
#Sta/Elev= 30
    4201  313.13    4339  307.62  4370.6  303.94  4443.7  303.96  4460.1  305.75
  4504.2  298.18  4509.9  299.51  4526.3  298.43    4532  300.51  4598.2  299.69
  4912.3  290.68  4917.9  288.51  4934.4  289.09    4940  286.38  4943.1  286.32
  4959.8  285.53  4978.5  285.73  5003.2  283.41    5006  282.91  5009.2  283.41
  5028.3  285.44  5059.1   285.1  5065.1  286.47  5137.2  288.06  5144.7  289.61
  5158.2  287.88  5224.3  287.19  5491.7  287.38  5937.9  292.13  6478.7  303.68
#Mann= 5 ,-1 , 0
    4201     .05       0  4943.1     .12       0  4959.8     .05       0
  5003.2     .03       0  5009.2     .05       0
#XS Ineff= 1 ,-1
 5144.12 5888.86  290.03
Permanent Ineff=
       F
Bank Sta=4940,5065.1
XS Rating Curve= 0 ,0
Exp/Cntr=0.3,0.1

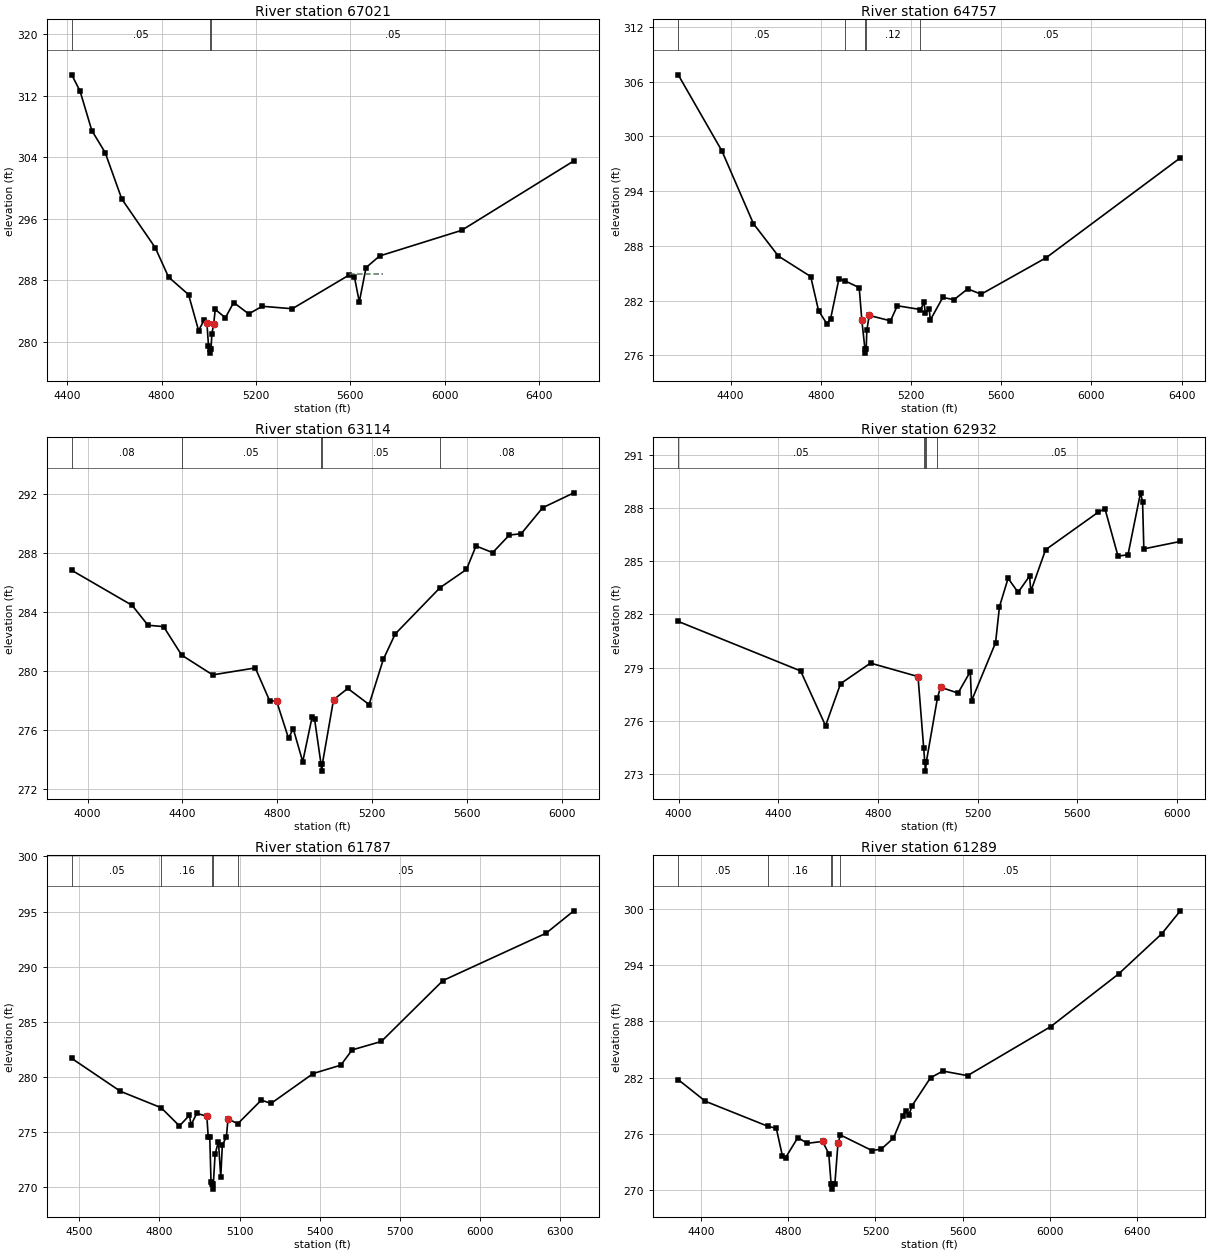
Type RM Length L Ch R = 1 ,67021   ,2264,2264,2264
BEGIN DESCRIPTION:
BULL CREEK 74.0
END DESCRIPTION:
XS GIS Cut Line= 3
       3634092.1     10258541.64      3633692.11     10258941.64
      3632692.13     10260141.62
#Sta/Elev= 30
  4419.1  314.73  4454.5  312.59    4504  307.49  4560.5  304.63  4631.2  298.58
  4772.7  292.27  4829.2  288.44  4914.1  286.15  4956.5  281.49  4981.2   282.9
  4991.9  282.43  4998.5  279.53  5003.3  279.05    5006  278.55  5009.3  279.05
  5012.8  281.06  5020.6  282.37  5027.1  284.23    5070  283.15  5105.2  285.13
    5169  283.65  5226.3  284.64  5353.8  284.32  5595.9  288.73  5616.8  288.47
  5637.6  285.21  5666.2  289.67  5723.5  291.18  6071.1  294.51  6546.8  303.54
#Mann= 3 ,-1 , 0
  4419.1     .05       0  5003.3     .03       0  5009.3     .05       0
#XS Ineff= 1 ,-1
 5596.36 5739.62  288.87
Permanent Ineff=
       F
Bank Sta=4991.9,5020.6
XS Rating Curve= 0 ,0
Exp/Cntr=0.3,0.1

Type RM Length L Ch R = 1 ,64757   ,1643,1643,1643
BEGIN DESCRIPTION:
BULL CREEK 71.0
END DESCRIPTION:
XS GIS Cut Line= 3
      3633370.11     10257679.41      3632609.67     10259142.98
      3632286.95     10259621.86
#Sta/Elev= 30
  4167.5  306.74  4361.6  298.38  4500.9  290.43  4611.5  286.88    4755  284.63
  4789.8   280.9    4827  279.44  4843.5  280.03    4880  284.35  4906.2  284.17
  4970.1  283.42  4981.8  279.85  4995.3  276.74    4998  276.24  5001.3  276.74
  5003.9  278.76  5014.7  280.37  5108.8  279.78  5139.2  281.43  5241.6  281.02
    5258  281.79  5263.6  280.59  5280.1   281.1  5285.7  279.88  5340.8  282.34
  5390.7   282.1  5451.4  283.28  5511.1   282.7  5799.6   286.7  6394.3  297.64
#Mann= 5 ,-1 , 0
  4167.5     .05       0  4906.2     .12       0  4995.3     .07       0
  5001.3     .12       0  5241.6     .05       0
#XS Ineff= 1 ,-1
 4601.19 4881.18  284.33
Permanent Ineff=
       F
Bank Sta=4981.8,5014.7
XS Rating Curve= 0 ,0
Exp/Cntr=0.3,0.1

Type RM Length L Ch R = 1 ,63114   ,182,182,182
BEGIN DESCRIPTION:
BULL CREEK 68.0
END DESCRIPTION:
XS GIS Cut Line= 4
      3632029.32      10256968.6      3632126.54     10257385.23
      3632126.54     10258454.67      3632070.98     10259072.71
#Sta/Elev= 30
  3933.3  286.82  4187.8  284.45  4254.8   283.1  4320.6  283.01  4396.7  281.08
  4527.5  279.74  4707.5  280.21  4767.5     278  4797.5  277.95  4847.5  275.45
  4867.5  276.09  4907.5  273.86  4947.5  276.92  4957.5  276.74  4984.5  273.72
  4987.3  273.22  4990.5  273.72  5037.5  278.06  5097.5  278.82  5187.5  277.73
  5247.5  280.79  5297.5  282.51    5487  285.65  5598.2  286.88  5638.4  288.47
  5708.7  288.02  5778.9  289.21  5829.1   289.3  5919.5  291.06  6051.1  292.07
#Mann= 5 ,-1 , 0
  3933.3     .08       0  4396.7     .05       0  4984.5     .03       0
  4990.5     .05       0    5487     .08       0
Bank Sta=4797.5,5037.5
XS Rating Curve= 0 ,0
Exp/Cntr=0.3,0.1

Type RM Length L Ch R = 1 ,62932   ,1145,1145,1145
BEGIN DESCRIPTION:
Mapping XS 40c14a7c
END DESCRIPTION:
XS GIS Cut Line= 5
      3631834.87       10257038.      3631945.98     10257392.17
       3631980.7     10257926.89      3631939.04     10258399.11
      3631897.37     10259031.04
#Sta/Elev= 30
  3998.6   281.6  4489.5  278.81  4589.7  275.72  4649.9  278.09  4770.1  279.25
  4960.6  278.49  4983.3  274.49  4987.7  273.66  4990.5  273.16  4993.7  273.66
  5038.8   277.3    5051  277.89  5121.2  277.56  5170.3  278.77  5175.3  277.12
  5271.8   280.4  5287.4  282.43    5322  284.03  5362.2  283.24  5408.2  284.16
  5413.2   283.3  5472.4  285.64  5682.9  287.75  5710.5  287.96  5763.1  285.28
  5803.1  285.36  5853.3  288.85  5861.6  288.34  5866.7  285.69    6013  286.11
#Mann= 5 ,-1 , 0
  3998.6     .05       0  4983.3     .08       0  4987.7     .07       0
  4993.7     .08       0  5038.8     .05       0
Bank Sta=4960.6,5051
XS Rating Curve= 0 ,0
Exp/Cntr=0.3,0.1

Type RM Length L Ch R = 1 ,61787   ,498,498,498
BEGIN DESCRIPTION:
BULL CREEK 65.0
END DESCRIPTION:
XS GIS Cut Line= 3
      3631794.09     10256943.78      3631542.11     10257391.64
      3630813.63     10258547.91
#Sta/Elev= 30
  4471.7  281.69  4653.8  278.71  4806.4  277.22    4875  275.57  4912.6  276.54
  4918.3  275.66    4940  276.71  4977.6  276.45  4982.7  274.61  4988.5  274.61
  4993.2  270.51  4996.1  270.34  4998.9  269.84  5002.1  270.34  5008.5  273.01
    5021  274.15  5029.7  270.92  5035.6  273.82  5050.9  274.58  5056.8   276.2
  5093.5  275.77  5181.6  277.91  5218.1  277.61  5375.8  280.32  5479.4  281.08
  5521.8  282.46  5631.3  283.23    5862  288.75  6248.1  293.04  6352.2  295.07
#Mann= 5 ,-1 , 0
  4471.7     .05       0  4806.4     .16       0  4996.1     .07       0
  5002.1     .16       0  5093.5     .05       0
Bank Sta=4977.6,5056.8
XS Rating Curve= 0 ,0
Exp/Cntr=0.3,0.1

Type RM Length L Ch R = 1 ,61289   ,2648,2648,2648
BEGIN DESCRIPTION:
BULL CREEK 64.0
END DESCRIPTION:
XS GIS Cut Line= 3
      3631720.06     10256663.68      3631292.11     10257091.64
      3630092.09     10258291.66
#Sta/Elev= 30
  4295.7  281.77  4420.1  279.46  4707.1  276.78  4745.4  276.57  4773.6  273.59
  4787.8  273.42  4844.4  275.58  4886.8  274.96  4957.5  275.16  4985.8  273.86
  4996.9  270.56  4999.7  270.06  5002.9  270.56  5014.1  270.65  5028.2  274.97
  5039.7  275.85  5183.8  274.19  5226.2  274.33  5282.8  275.52  5325.2  277.91
  5339.3  278.43  5353.5  277.98  5367.6  278.97  5452.5  281.97    5509  282.69
  5622.2   282.2    6004  287.45  6315.1  293.08  6513.1  297.38    6598  299.83
#Mann= 5 ,-1 , 0
  4295.7     .05       0  4707.1     .16       0  4996.9     .07       0
  5002.9     .16       0  5039.7     .05       0
Bank Sta=4957.5,5028.2
XS Rating Curve= 0 ,0
Exp/Cntr=0.3,0.1

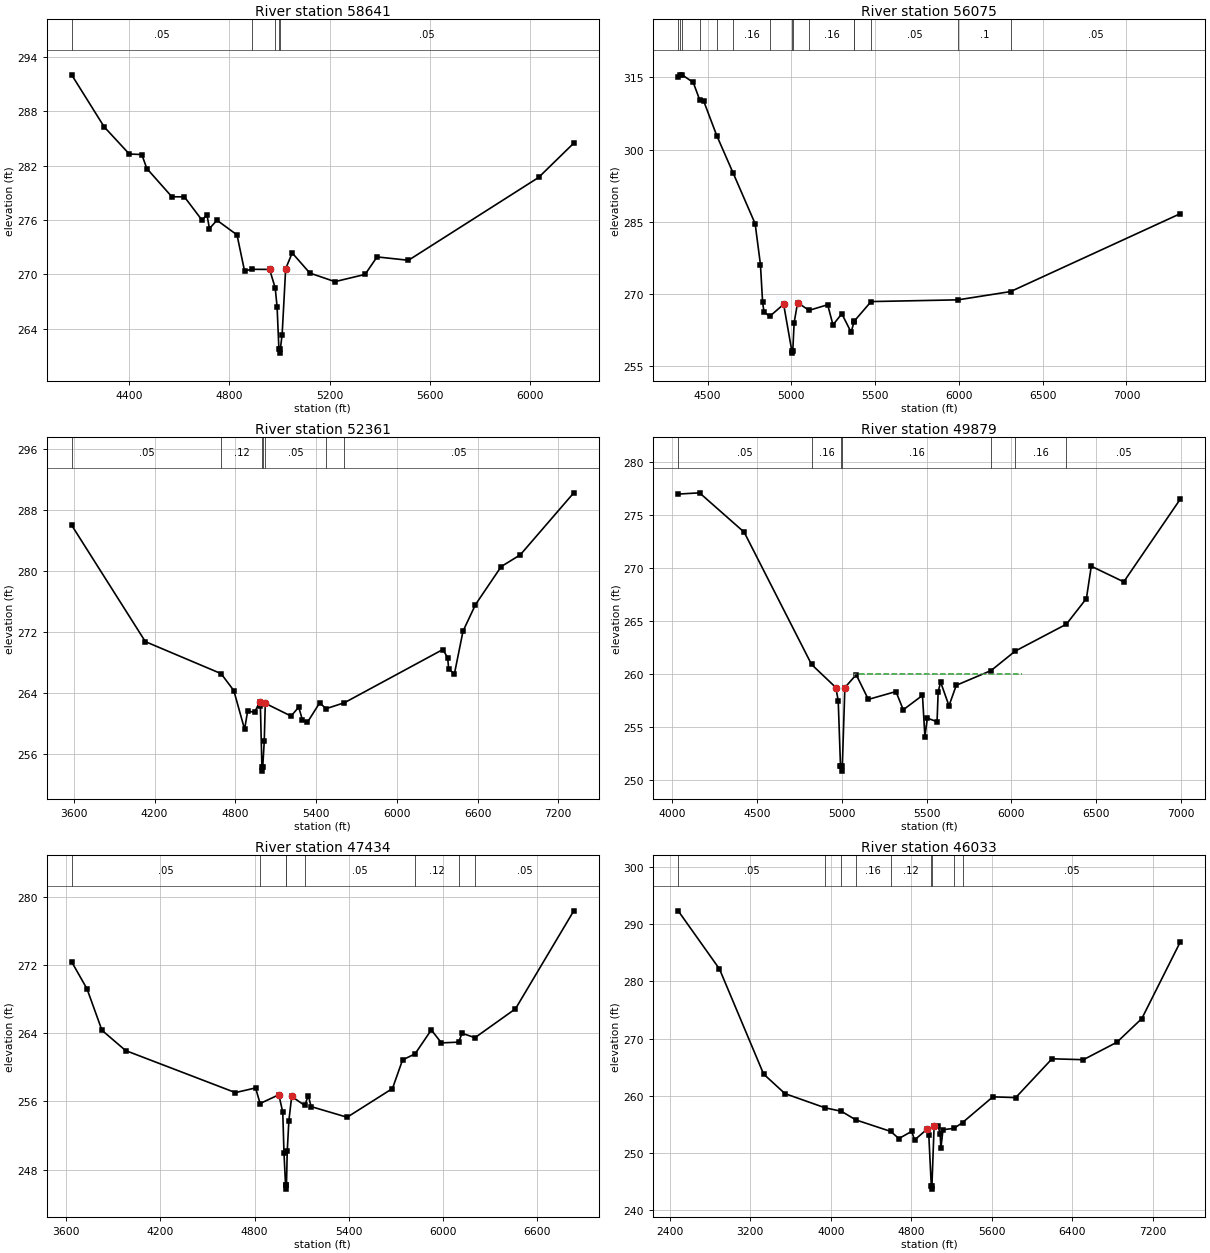
Type RM Length L Ch R = 1 ,58641   ,2566,2566,2566
BEGIN DESCRIPTION:
BULL CREEK 60.0
END DESCRIPTION:
XS GIS Cut Line= 3
      3629992.11     10255441.68      3629992.11     10256241.64
      3629892.11     10257441.62
#Sta/Elev= 30
  4170.5  292.04  4300.5  286.29  4400.5   283.3  4450.5  283.24  4470.5   281.7
  4570.5  278.58  4620.5  278.57  4690.5  276.01  4710.5  276.58  4720.5  275.07
  4750.5  275.99  4830.5  274.37  4860.5   270.4  4890.7  270.57  4960.5  270.56
  4982.9  268.52  4990.5  266.42  4997.6  261.82  5000.3  261.32  5003.6  261.82
  5010.6  263.37 5024.73  270.64  5050.7  272.38    5121  270.16  5221.3  269.21
  5341.7  270.01  5389.4  271.94  5514.8  271.57  6034.1  280.71  6174.6   284.5
#Mann= 5 ,-1 , 0
  4170.5     .05       0  4890.7     .12       0  4982.9     .05       0
  4997.6     .03       0  5003.6     .05       0
Bank Sta=4960.5,5024.73
XS Rating Curve= 0 ,0
Exp/Cntr=0.3,0.1

Type RM Length L Ch R = 1 ,56075   ,3714,3714,3714
BEGIN DESCRIPTION:
BULL CREEK 56.0
END DESCRIPTION:
XS GIS Cut Line= 2
      3628628.15     10255196.62      3627664.62     10258035.14
#Sta/Elev= 30
    4324  315.08  4334.9  315.53  4349.4  315.48  4413.8  313.95  4451.8  310.39
  4477.1     310  4554.2   302.9  4651.8  295.13  4783.4  284.58  4815.1  276.08
    4828  268.25  4836.2  266.26  4870.2   265.3  4953.6  267.81  5002.2  258.16
  5004.9  257.66  5008.2  258.16  5016.3  263.98  5036.9  268.16  5105.4  266.55
  5216.4  267.72  5248.1  263.53  5300.9  265.85  5356.4     262  5373.3   264.1
  5376.5  264.37  5475.7  268.38  5994.7  268.74  6308.3  270.46  7321.6  286.66
#Mann= 15 ,-1 , 0
    4324     .05       0  4334.9     .16       0  4349.4      .1       0
  4451.8     .05       0  4554.2      .1       0  4651.8     .16       0
  4870.2     .12       0  5002.2     .07       0  5008.2     .12       0
  5105.4     .16       0  5373.3     .12       0  5376.5     .16       0
  5475.7     .05       0  5994.7      .1       0  6308.3     .05       0
Bank Sta=4953.6,5036.9
XS Rating Curve= 0 ,0
Exp/Cntr=0.3,0.1

Type RM Length L Ch R = 1 ,52361   ,2482,2482,2482
BEGIN DESCRIPTION:
BULL CREEK 53.0
END DESCRIPTION:
XS GIS Cut Line= 3
      3627892.13     10255091.63      3626692.11     10255791.64
      3624892.14     10257291.61
#Sta/Elev= 30
  3583.3  286.03  4131.2  270.78    4694  266.59  4788.6  264.37  4868.8   259.3
  4891.5  261.69  4943.2  261.52  4979.7  262.84  4986.2  262.35  4997.6  254.32
  5000.3  253.82  5003.6  254.32  5014.9  257.74  5022.7   262.7    5214  261.03
  5271.3   262.2  5298.7  260.52  5335.1   260.2  5427.5  262.78    5473  261.99
    5611  262.78  6342.6  269.75  6378.4  268.66  6385.6  267.16  6428.5  266.57
  6492.3  272.15  6584.7  275.62  6776.1  280.61    6918  282.15  7315.6  290.27
#Mann= 7 ,-1 , 0
  3583.3     .05       0    4694     .12       0  4997.6     .07       0
  5003.6     .12       0  5022.7     .05       0    5473      .1       0
    5611     .05       0
Bank Sta=4979.7,5022.7
XS Rating Curve= 0 ,0
Exp/Cntr=0.3,0.1

Type RM Length L Ch R = 1 ,49879   ,2445,2445,2445
BEGIN DESCRIPTION:
BULL CREEK 49.0
END DESCRIPTION:
XS GIS Cut Line= 2
      3626214.99     10254076.78      3624322.58     10256351.13
#Sta/Elev= 30
    4036  276.95  4161.8  277.07  4424.8  273.36  4822.1  260.89  4965.1  258.72
    4979  257.46  4992.4  251.36  4997.3  251.34    5000  250.84  5003.3  251.34
 5018.19  258.71  5084.9  259.93  5156.5   257.6  5319.2  258.34  5362.2  256.62
  5475.4  257.98  5489.8  254.09  5504.1  255.84  5561.4  255.49  5567.9  258.31
  5582.2  259.24  5631.7     257  5674.6  258.93  5879.8  260.32  6021.6  262.15
  6323.5  264.69  6441.4  267.11  6470.1  270.15  6661.5  268.68  6994.7  276.48
#Mann= 7 ,-1 , 0
    4036     .05       0  4822.1     .16       0  4997.3     .07       0
  5003.3     .16       0  5879.8     .05       0  6021.6     .16       0
  6323.5     .05       0
#XS Ineff= 1 ,-1
 5072.77 6060.26  259.99
Permanent Ineff=
       F
Bank Sta=4965.1,5018.19
XS Rating Curve= 0 ,0
Exp/Cntr=0.3,0.1

Type RM Length L Ch R = 1 ,47434   ,1401,1401,1401
BEGIN DESCRIPTION:
BULL CREEK 46.0
END DESCRIPTION:
XS GIS Cut Line= 3
       3624942.1     10253241.65      3624342.11     10254441.64
      3623892.11     10256241.62
#Sta/Elev= 30
  3635.7  272.37  3733.5   269.2  3828.6  264.34  3979.5  261.96  4678.3  257.03
  4806.8  257.58  4835.4  255.75    4955  256.78  4979.9  254.71  4987.6  249.96
  4997.5  246.21  5000.3  245.71  5003.5  246.21  5008.3  250.14  5018.6   253.7
  5036.6  256.58    5120  255.52  5142.3  256.69  5160.3  255.39  5389.6  254.14
  5678.3  257.51  5742.7  260.87    5822  261.57  5925.6  264.38  5990.1  262.86
  6099.5  262.95  6121.5  263.99  6203.4  263.47  6461.6  266.86  6832.7  278.35
#Mann= 8 ,-1 , 0
  3635.7     .05       0  4835.4     .16       0  4997.5     .07       0
  5003.5     .16       0    5120     .05       0    5822     .12       0
  6099.5     .16       0  6203.4     .05       0
Bank Sta=4955,5036.6
XS Rating Curve= 0 ,0
Exp/Cntr=0.3,0.1

Type RM Length L Ch R = 1 ,46033   ,1026,1026,1026
BEGIN DESCRIPTION:
BULL CREEK 43.0
END DESCRIPTION:
XS GIS Cut Line= 3
      3625092.08     10252491.67      3623292.11     10254291.64
      3621642.09     10256091.66
#Sta/Elev= 30
  2483.9  292.33    2894  282.16  3332.4  263.79  3544.5  260.37  3944.5  257.88
  4103.9  257.29  4249.2  255.77  4594.9  253.76  4675.9  252.51  4803.2  253.77
  4831.5  252.26  4958.7  254.19  4972.9   253.2  4998.2  244.17  5000.9  243.67
  5004.2  244.17  5025.9  254.71  5064.9  254.75  5085.9  253.33  5093.3   250.8
  5114.2  254.06  5224.1   254.3  5308.4  255.31    5610  259.81  5836.3  259.67
    6197  266.46  6508.4   266.3  6841.4  269.35  7089.3   273.5  7471.3   286.9
#Mann= 9 ,-1 , 0
  2483.9     .05       0  3944.5     .16       0  4103.9     .05       0
  4249.2     .16       0  4594.9     .12       0  4998.2     .07       0
  5004.2     .12       0  5224.1     .16       0  5308.4     .05       0
Bank Sta=4958.7,5025.9
XS Rating Curve= 0 ,0
Exp/Cntr=0.3,0.1

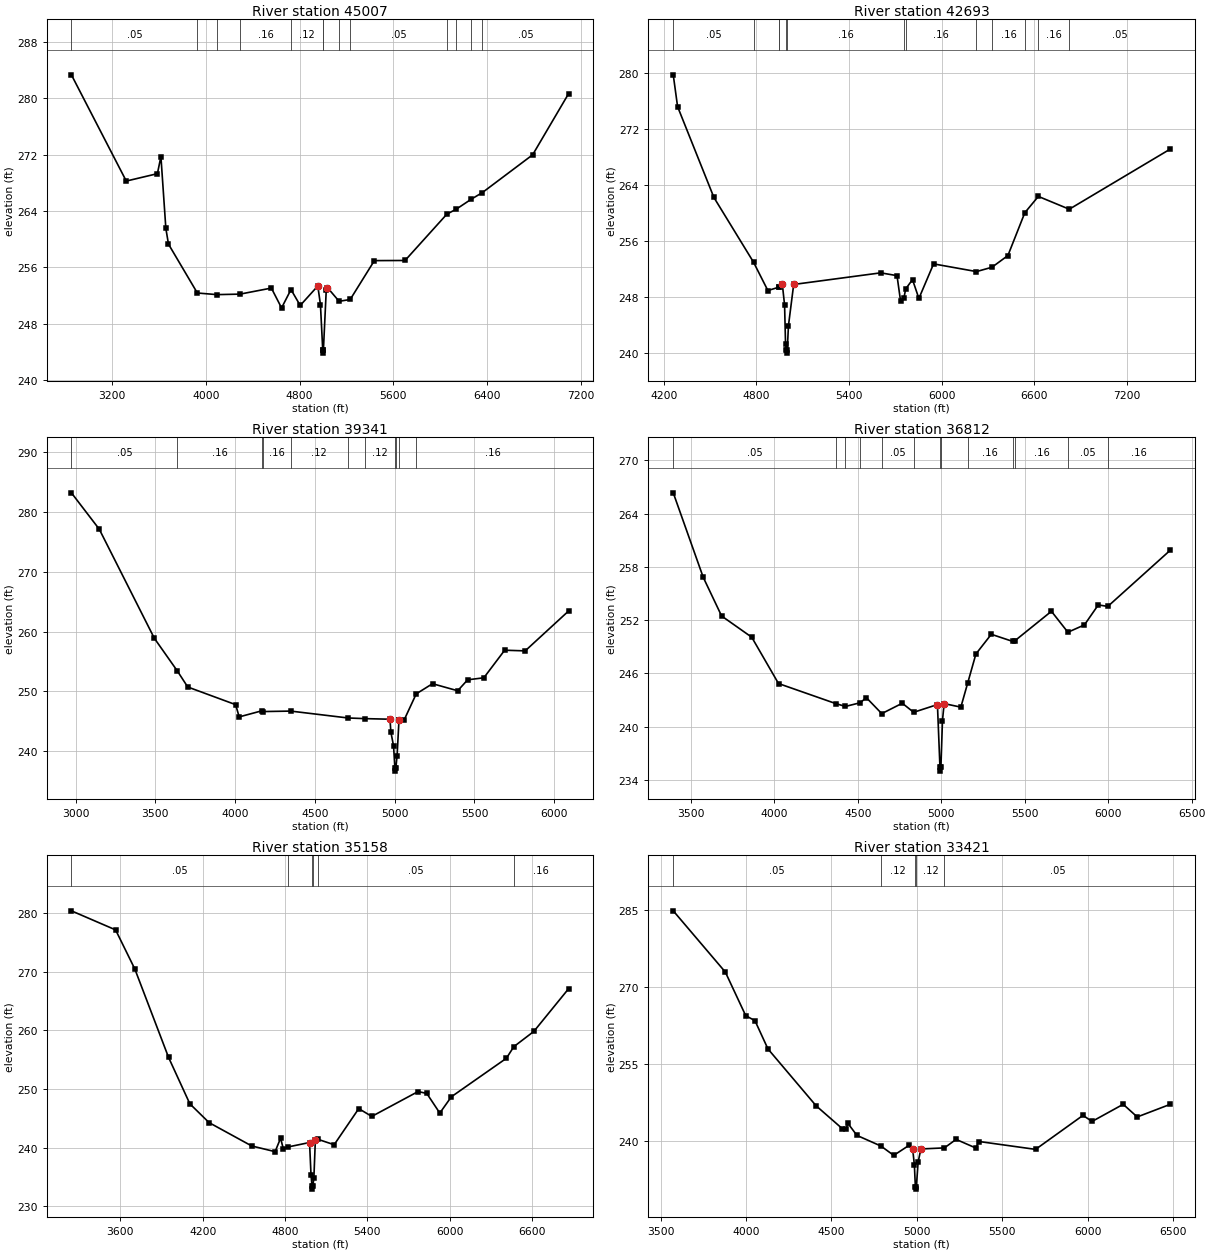
Type RM Length L Ch R = 1 ,45007   ,2314,2314,2314
BEGIN DESCRIPTION:
BULL CREEK 41.0
END DESCRIPTION:
XS GIS Cut Line= 3
      3623842.11     10252291.63      3622642.11     10254091.64
      3621592.11     10255891.63
#Sta/Elev= 30
  2850.4  283.35  3319.1  268.26    3585  269.31  3615.1  271.74  3657.2  261.53
  3679.7   259.3  3926.2  252.36  4093.1  252.13  4290.1   252.2  4558.5  253.06
  4645.7  250.24  4726.1  252.85  4804.9  250.59  4955.2  253.36  4977.7  250.72
  4997.2  244.32    5000  243.82  5003.2  244.32  5027.4  252.78  5036.9  253.14
  5137.4  251.18    5232  251.44  5438.4  256.96  5700.5  256.98  6057.6  263.56
  6138.1  264.27  6267.6   265.7  6360.5  266.62  6790.4  271.99  7097.6  280.68
#Mann= 13 ,-1 , 0
  2850.4     .05       0  3926.2     .16       0  4093.1     .05       0
  4290.1     .16       0  4726.1     .12       0  4997.2     .07       0
  5003.2     .12       0  5137.4     .16       0    5232     .05       0
  6057.6     .08       0  6138.1     .05       0  6267.6     .08       0
  6360.5     .05       0
Bank Sta=4955.2,5036.9
XS Rating Curve= 0 ,0
Exp/Cntr=0.3,0.1

Type RM Length L Ch R = 1 ,42693   ,3352,3352,3352
BEGIN DESCRIPTION:
BULL CREEK 39.0
END DESCRIPTION:
XS GIS Cut Line= 3
      3622592.11     10252291.63      3622142.11     10252891.64
       3621542.1     10255291.67
#Sta/Elev= 30
  4260.6  279.76  4288.7  275.22  4524.2  262.24  4781.2  252.99  4874.2  248.94
  4946.8  249.43  4948.3   249.5  4967.9  249.84  4982.5  246.87  4988.7  241.32
  4994.1   240.5  4996.8     240  5000.1   240.5  5007.5  243.91  5041.5  249.81
  5605.9  251.47  5711.5  251.07  5734.7  247.42  5756.8  247.94  5767.8  249.18
    5812   250.5  5853.3  247.81  5948.6  252.75  6226.8  251.65  6327.1  252.27
  6430.5  253.94  6540.2  260.06  6627.9  262.39  6828.5  260.56  7484.5  269.17
#Mann= 13 ,-1 , 0
  4260.6     .05       0  4781.2     .16       0  4946.8      .1       0
  4948.3     .16       0  4994.1     .07       0  5000.1     .16       0
  5756.8     .12       0  5767.8     .16       0  6226.8     .05       0
  6327.1     .16       0  6540.2     .05       0  6627.9     .16       0
  6828.5     .05       0
Bank Sta=4967.9,5041.5
XS Rating Curve= 0 ,0
Exp/Cntr=0.3,0.1

Type RM Length L Ch R = 1 ,39341   ,2529,2529,2529
BEGIN DESCRIPTION:
BULL CREEK 36.0
END DESCRIPTION:
XS GIS Cut Line= 3
      3621353.84      10251281.7      3620190.66     10253703.53
      3620432.79     10254058.07
#Sta/Elev= 30
  2973.8  283.21  3148.4  277.13  3493.5  258.89  3637.2  253.44  3702.9  250.74
  4002.8  247.79  4025.4  245.74  4167.6  246.76    4173  246.63  4348.3  246.71
  4706.9  245.56  4813.9  245.45  4970.4  245.35  4975.9  243.21  4992.8  240.87
  5001.1  237.17  5003.9  236.67  5007.1  237.17    5015  239.28  5026.8  245.24
  5027.8   245.3  5059.3  245.24  5134.8  249.59  5236.8  251.29  5394.6  250.11
    5457  251.94  5558.6  252.28    5689  256.89  5817.7  256.78  6089.8  263.45
#Mann= 11 ,-1 , 0
  2973.8     .05       0  3637.2     .16       0  4167.6     .12       0
    4173     .16       0  4348.3     .12       0  4706.9     .16       0
  4813.9     .12       0  5001.1     .07       0  5007.1     .12       0
  5027.8     .05       0  5134.8     .16       0
Bank Sta=4970.4,5026.8
XS Rating Curve= 0 ,0
Exp/Cntr=0.3,0.1

Type RM Length L Ch R = 1 ,36812   ,1654,1654,1654
BEGIN DESCRIPTION:
BULL CREEK 33.0
END DESCRIPTION:
XS GIS Cut Line= 3
      3619264.51     10250952.48      3619123.43     10253054.29
        3619452.     10253862.19
#Sta/Elev= 30
  3394.3  266.35  3573.9  256.83  3684.1  252.47  3864.5  250.08  4024.9  244.86
  4368.1   242.6  4425.7  242.28  4515.4   242.7  4550.6  243.28  4643.4  241.47
  4766.5  242.64  4834.5  241.62    4977  242.49    4992  235.49  4994.8  234.99
    4998  235.49  5007.1  240.67  5017.1   242.6  5117.3   242.2  5157.9  244.89
  5207.5  248.19  5299.7  250.41  5429.1   249.6  5440.9  249.68  5659.9     253
  5758.6  250.64  5857.7  251.47  5940.6  253.72  5997.7  253.55    6373   259.9
#Mann= 13 ,-1 , 0
  3394.3     .05       0  4368.1      .1       0  4425.7     .05       0
  4515.4      .1       0  4643.4     .05       0  4834.5     .12       0
    4992     .07       0    4998     .12       0  5157.9     .16       0
  5429.1     .05       0  5440.9     .16       0  5758.6     .05       0
  5997.7     .16       0
Bank Sta=4977,5017.1
XS Rating Curve= 0 ,0
Exp/Cntr=0.3,0.1

Type RM Length L Ch R = 1 ,35158   ,1737,1737,1737
BEGIN DESCRIPTION:
BULL CREEK 30.0
END DESCRIPTION:
XS GIS Cut Line= 3
      3618185.46     10250370.17      3618092.11     10252091.64
      3617492.09     10253891.68
#Sta/Elev= 30
  3244.2   280.4  3566.1  277.15  3706.3  270.47  3952.1  255.39  4106.9  247.49
  4247.1  244.28  4557.6   240.3  4727.8  239.33  4767.9  241.63  4787.9  239.78
  4823.8  240.14  4978.7  240.89  4989.3  235.42  4996.8  233.44  4999.6  232.94
  5002.8  233.44  5010.4  234.91  5020.9  241.26  5043.3  241.41  5157.9  240.51
  5337.1  246.67    5432  245.34  5769.3  249.58  5832.6  249.26  5927.4  245.91
  6011.7  248.69  6412.3  255.25  6466.4  257.23  6612.6  259.84  6865.6  267.12
#Mann= 6 ,-1 , 0
  3244.2     .05       0  4823.8     .12       0  4996.8     .07       0
  5002.8     .12       0  5043.3     .05       0  6466.4     .16       0
Bank Sta=4978.7,5020.9
XS Rating Curve= 0 ,0
Exp/Cntr=0.3,0.1

Type RM Length L Ch R = 1 ,33421   ,1674,1674,1674
BEGIN DESCRIPTION:
BULL CREEK 29.0
END DESCRIPTION:
XS GIS Cut Line= 2
      3617899.01     10250300.71      3616770.51     10252983.09
#Sta/Elev= 30
  3574.2  284.88    3879  272.93  3998.3  264.42  4052.6  263.43  4128.5  257.92
  4410.6  246.81  4563.5  242.36  4587.2  242.22    4595  243.45  4649.3  241.04
  4789.9  238.96  4864.6  237.14    4953  239.07  4975.9  238.29  4985.6  235.22
  4991.2  231.05    4994  230.55  4997.2  231.05  5007.3  235.77  5023.4  238.39
  5161.2   238.6  5229.6  240.26  5343.6   238.6  5365.3  239.84  5694.9  238.31
  5972.4  244.95  6025.3  243.76  6207.7  247.11  6289.8  244.64  6484.3  247.12
#Mann= 5 ,-1 , 0
  3574.2     .05       0  4789.9     .12       0  4991.2     .07       0
  4997.2     .12       0  5161.2     .05       0
Bank Sta=4975.9,5023.4
XS Rating Curve= 0 ,0
Exp/Cntr=0.3,0.1

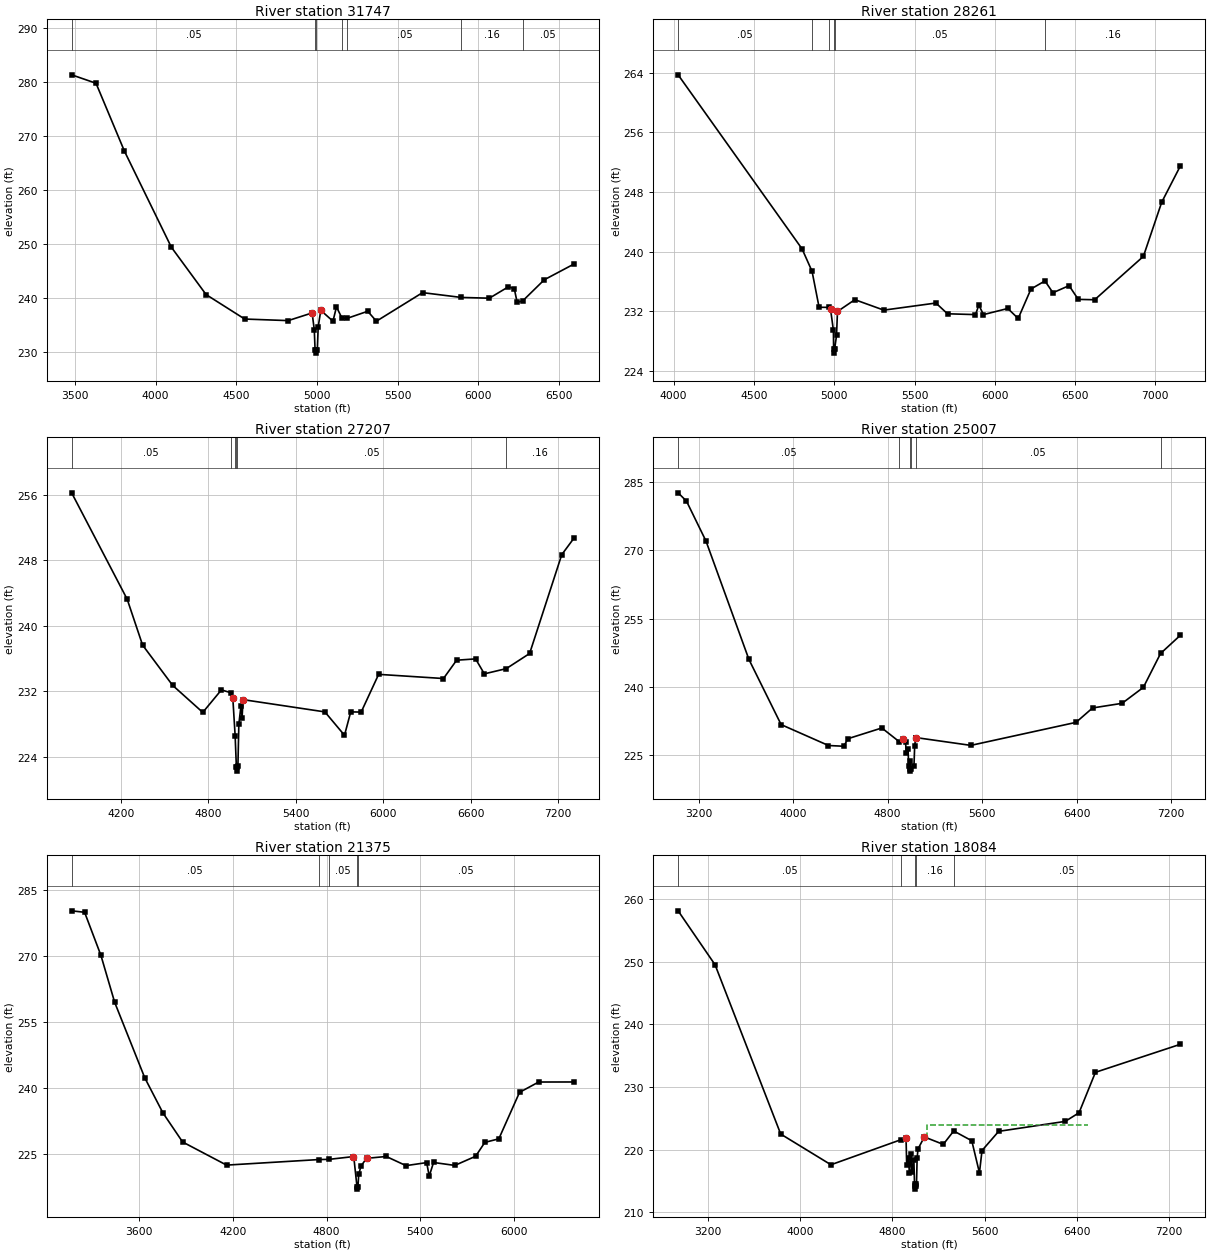
Type RM Length L Ch R = 1 ,31747   ,3486,3486,3486
BEGIN DESCRIPTION:
BULL CREEK 26.0
END DESCRIPTION:
XS GIS Cut Line= 2
      3616683.73     10249858.02      3615529.61     10252747.67
#Sta/Elev= 30
  3479.4  281.39  3630.4  279.83  3806.3  267.27  4097.1  249.48  4312.4  240.71
  4551.7  236.18  4821.1  235.89  4969.3  237.31  4982.8  234.19  4987.8  230.37
  4990.6  229.87  4993.8  230.37  5001.6  230.45    5007  234.74  5023.1  237.79
  5098.5  235.78  5120.2  238.42  5153.8  236.39  5188.4  236.33  5313.9  237.62
  5367.7  235.78  5653.6  241.07  5893.2  240.18  6067.6  240.04  6186.1  242.16
    6222  241.79  6239.9  239.26  6274.1  239.54  6407.9  243.45    6591  246.35
#Mann= 7 ,-1 , 0
  3479.4     .05       0  4987.8     .03       0  4993.8     .05       0
  5153.8     .07       0  5188.4     .05       0  5893.2     .16       0
  6274.1     .05       0
Bank Sta=4969.3,5023.1
XS Rating Curve= 0 ,0
Exp/Cntr=0.3,0.1

Type RM Length L Ch R = 1 ,28261   ,1054,1054,1054
BEGIN DESCRIPTION:
BULL CREEK 24.0
END DESCRIPTION:
XS GIS Cut Line= 3
      3615364.26     10249302.52      3614992.11     10250191.64
      3613792.11     10251991.64
#Sta/Elev= 30
    4028   263.7  4799.9  240.38    4862  237.38  4905.9  232.56  4968.3  232.55
  4977.3  232.28  4994.9   229.5  4996.4  226.92  4999.1  226.42  5002.4  226.92
  5014.4  228.79  5020.4     232  5128.6  233.58  5308.9  232.18  5633.4  233.13
  5705.5  231.69  5879.7  231.58  5900.8  232.85  5929.3  231.58    6081   232.4
  6145.6  231.06  6225.3  235.01  6312.4  236.09    6362  234.51  6462.6  235.46
  6519.7  233.62  6621.9  233.57  6925.3  239.38  7039.5  246.64  7155.2  251.48
#Mann= 6 ,-1 , 0
    4028     .05       0    4862     .16       0  4968.3     .05       0
  4996.4     .03       0  5002.4     .05       0  6312.4     .16       0
Bank Sta=4977.3,5020.4
XS Rating Curve= 0 ,0
Exp/Cntr=0.3,0.1

Type RM Length L Ch R = 1 ,27207   ,2200,2200,2200
BEGIN DESCRIPTION:
BULL CREEK 22.0
END DESCRIPTION:
XS GIS Cut Line= 3
      3615086.52     10249250.39      3613306.98     10250717.42
      3613376.43     10251854.52
#Sta/Elev= 30
  3862.1  256.27  4243.2  243.26  4348.7  237.66  4554.7  232.74  4761.8  229.43
  4889.5  232.18    4955  231.83  4967.7  231.25  4983.7   226.6  4992.3  222.75
  4995.1  222.25  4998.3  222.75  5002.8  222.86  5009.3  228.01  5023.6  230.19
  5031.5  228.79    5038  230.99  5599.6  229.49  5734.1  226.63  5776.8  229.49
  5848.5  229.47  5968.3  234.08  6413.1  233.57  6503.4  235.81  6633.5  235.97
  6693.6  234.14  6844.2  234.78  7004.2  236.63  7224.6  248.71  7307.6  250.71
#Mann= 6 ,-1 , 0
  3862.1     .05       0    4955     .16       0  4983.7     .05       0
  4992.3     .03       0  4998.3     .05       0  6844.2     .16       0
Bank Sta=4967.7,5038
XS Rating Curve= 0 ,0
Exp/Cntr=0.3,0.1

Type RM Length L Ch R = 1 ,25007   ,3632,3632,3632
BEGIN DESCRIPTION:
BULL CREEK 19.0
END DESCRIPTION:
XS GIS Cut Line= 3
      3614287.86     10247948.36      3612838.23     10249927.49
      3612838.23     10251724.35
#Sta/Elev= 30
  3026.6  282.58  3097.2  280.77  3262.4     272    3626  246.01  3898.4  231.72
  4299.2  227.13  4428.8  226.97  4464.4  228.63  4750.7  230.98    4896  228.01
  4928.3  228.58  4951.5   227.8  4957.6  225.45  4972.3  226.27  4978.5  222.55
    4987  223.77  4990.2  222.01  4992.9  221.51  4996.2  222.01  5022.5  222.55
  5028.7   227.1  5037.1  228.68  5039.9  228.87    5504  227.16    6394  232.21
    6534  235.37    6784  236.39    6964  239.89  7109.7  247.33  7276.7  251.31
#Mann= 6 ,-1 , 0
  3026.6     .05       0    4896     .16       0  4990.2     .07       0
  4996.2     .16       0  5039.9     .05       0  7109.7     .16       0
Bank Sta=4928.3,5037.1
XS Rating Curve= 0 ,0
Exp/Cntr=0.3,0.1

Type RM Length L Ch R = 1 ,21375   ,3291,3291,3291
BEGIN DESCRIPTION:
BULL CREEK 15.0
END DESCRIPTION:
XS GIS Cut Line= 3
      3613037.91     10246906.64      3610511.85     10248243.46
      3610329.76     10248546.93
#Sta/Elev= 30
  3169.6  280.28  3252.4  279.95  3356.8  270.15  3444.8  259.47  3637.2  242.32
  3753.2  234.35  3879.2  227.73  4160.5  222.47  4749.5  223.73  4815.9  223.78
  4967.4  224.39  4975.1  223.99  4994.7  217.51  4997.5  217.01  5000.7  217.51
  5005.8   220.4  5020.4  222.27  5055.5  224.01  5181.8  224.43  5308.2  222.35
  5440.2  223.04  5456.6  219.97  5484.2  223.07    5620   222.4  5753.3  224.48
  5812.3  227.64  5901.7  228.44  6034.1  239.01  6156.5  241.36  6381.5  241.37
#Mann= 5 ,-1 , 0
  3169.6     .05       0  4749.5     .12       0  4815.9     .05       0
  4994.7     .03       0  5000.7     .05       0
Bank Sta=4967.4,5055.5
XS Rating Curve= 0 ,0
Exp/Cntr=0.3,0.1

Type RM Length L Ch R = 1 ,18084   ,2027,2027,2027
BEGIN DESCRIPTION:
BULL CREEK 13.0
END DESCRIPTION:
XS GIS Cut Line= 4
      3612820.85     10246359.77      3612083.03     10246108.04
      3609626.43      10247288.6      3609400.74     10248104.53
#Sta/Elev= 30
  2943.9  258.11  3264.1   249.5  3832.8  222.49  4268.2  217.59  4874.9  221.59
    4919  221.79  4924.5  217.63  4941.6   218.7  4947.2  216.23  4964.3  219.34
  4969.8  216.37  4986.9  218.33  4992.4  214.51  4997.4   214.2  5000.2   213.7
  5003.4   214.2  5009.5  214.45  5015.1  218.65  5022.6  220.11  5077.5  222.03
  5241.5  220.84  5331.9  222.98  5488.6  221.42  5555.1   216.3  5577.3  219.86
  5721.6  222.92  6298.5  224.51  6418.2  225.89  6560.1  232.34  7295.6  236.81
#Mann= 5 ,-1 , 0
  2943.9     .05       0  4874.9     .16       0  4997.4     .07       0
  5003.4     .16       0  5331.9     .05       0
#XS Ineff= 1 ,-1
 5100.63 6492.33  223.95
Permanent Ineff=
       F
Bank Sta=4919,5077.5
XS Rating Curve= 0 ,0
Exp/Cntr=0.3,0.1