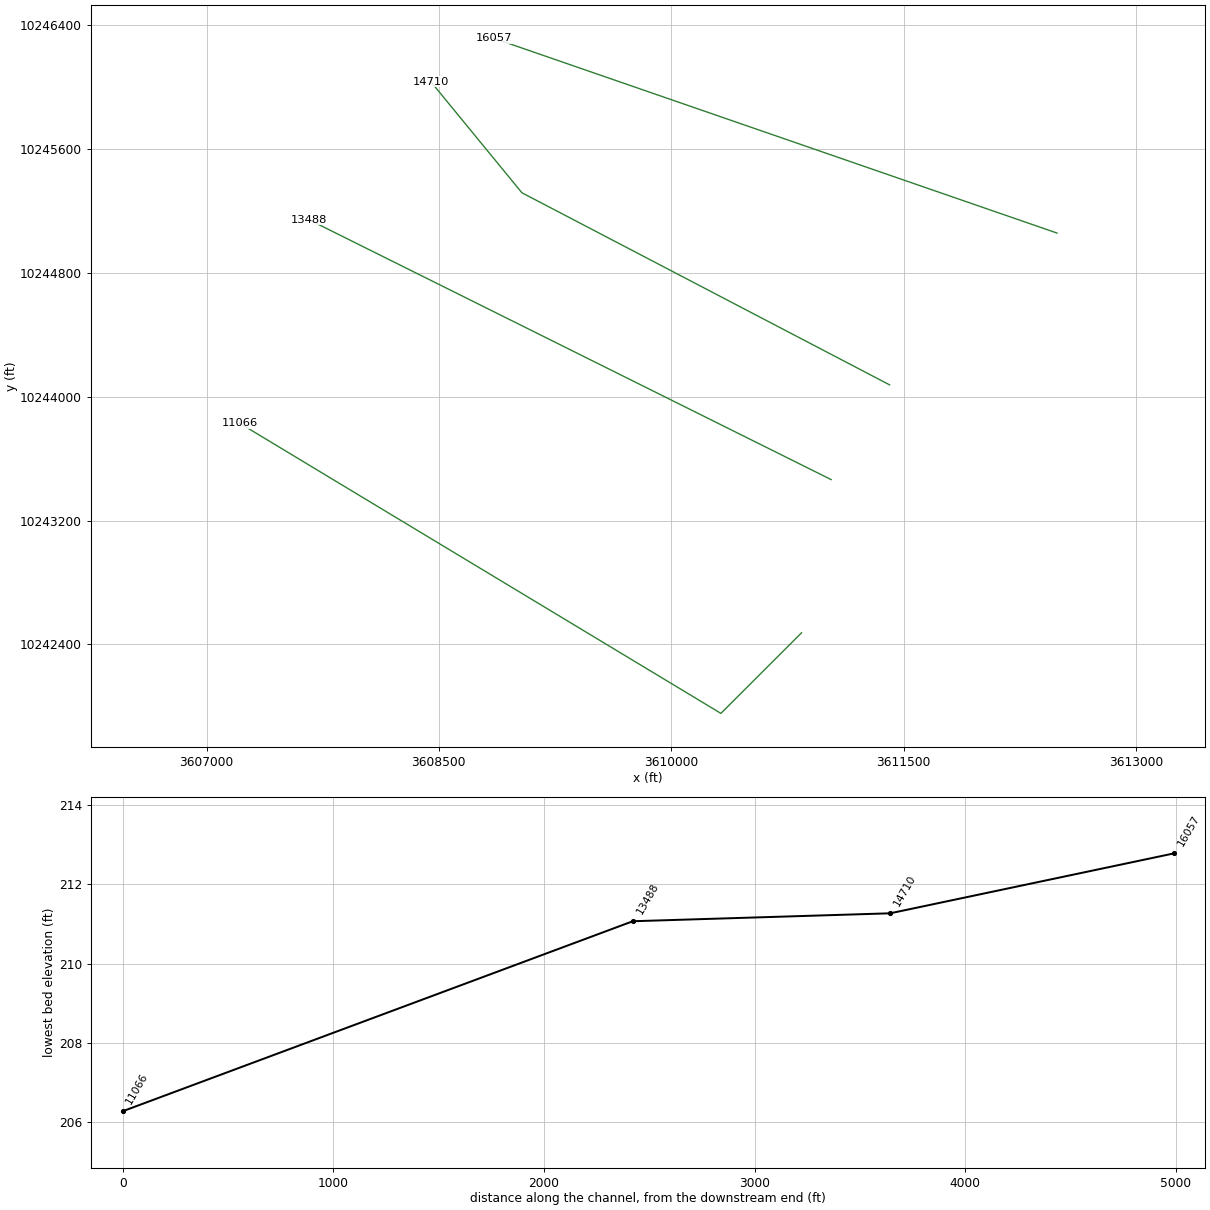
HEC-RAS study BULL CREEK.prj: BULL CREEK Base Level Engineering

--- BULL CREEK.g01 (geometry) --- (continued)

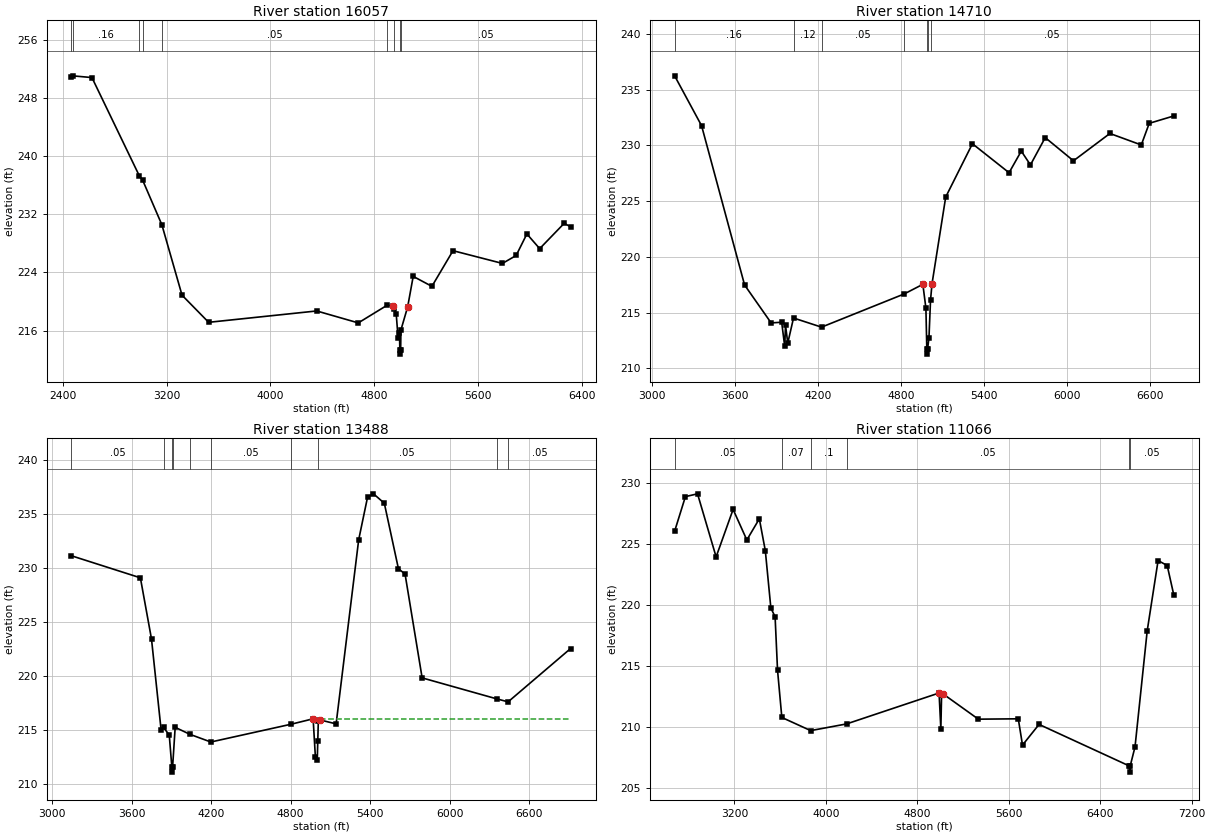
Type RM Length L Ch R = 1 ,16057   ,1347,1347,1347
BEGIN DESCRIPTION:
BULL CREEK 11.0
END DESCRIPTION:
XS GIS Cut Line= 2
      3612491.06     10245057.68       3608855.5     10246315.81
#Sta/Elev= 30
  2466.5  250.88  2475.1  251.01  2624.1  250.77  2989.1  237.28  3015.3  236.66
  3163.1  230.55  3318.4  220.88  3523.6  217.15  4356.7  218.71    4677  217.07
  4900.7  219.51  4943.5  219.36  4953.3  218.94  4969.4  218.29  4983.9  215.02
  4994.5  215.75  4997.5  213.28  5000.3  212.78  5003.5  213.28  5005.8   216.1
  5057.6  219.27  5100.3  223.46  5244.5  222.09  5407.2  226.99  5788.1  225.24
  5893.9  226.33  5976.5  229.29  6075.3  227.27  6264.3  230.75  6313.6  230.27
#Mann= 9 ,-1 , 0
  2466.5      .1       0  2475.1     .16       0  2989.1      .1       0
  3015.3     .16       0  3163.1     .05       0  4900.7     .12       0
  4953.3     .05       0  4997.5     .03       0  5003.5     .05       0
Bank Sta=4943.5,5057.6
XS Rating Curve= 0 ,0
Exp/Cntr=0.3,0.1

Type RM Length L Ch R = 1 ,14710   ,1222,1222,1222
BEGIN DESCRIPTION:
BULL CREEK 9.0
END DESCRIPTION:
XS GIS Cut Line= 3
      3611410.29     10244076.79      3609036.15     10245318.11
      3608447.32     10246036.84
#Sta/Elev= 30
  3162.7  236.23  3357.4  231.76  3668.4  217.47  3860.3  214.07  3936.5  214.13
  3958.6  211.96  3964.2  213.87  3980.6  212.26  4022.1  214.51  4224.7  213.69
  4822.8  216.67  4957.1  217.53  4979.2   215.4  4985.7  211.77  4988.5  211.27
  4991.7  211.77  5001.3  212.73  5012.7  216.12  5023.3  217.57  5122.4  225.36
  5315.5  230.14  5580.4  227.54  5668.7  229.48  5734.9  228.24  5841.8  230.69
    6046  228.61  6309.4  231.06  6536.3  230.03  6593.7  231.97  6770.9  232.63
#Mann= 7 ,-1 , 0
  3162.7     .16       0  4022.1     .12       0  4224.7     .05       0
  4822.8     .12       0  4985.7     .07       0  4991.7     .12       0
  5012.7     .05       0
Bank Sta=4957.1,5023.3
XS Rating Curve= 0 ,0
Exp/Cntr=0.3,0.1

Type RM Length L Ch R = 1 ,13488   ,2422,2422,2422
BEGIN DESCRIPTION:
BULL CREEK 6.0
END DESCRIPTION:
XS GIS Cut Line= 2
      3611032.64     10243464.83      3607660.29      10245144.5
#Sta/Elev= 30
  3146.5  231.11  3666.5  229.07  3750.4   223.4  3823.2  214.95    3841  215.21
  3884.4  214.51  3903.8  211.57  3906.5  211.07  3909.8  211.57  3929.1  215.22
  4040.8  214.57  4198.3  213.86    4805  215.51  4970.5  216.01  4987.3  212.51
  5001.6  212.16  5005.5  213.93  5009.7  215.83  5023.9   215.9    5144  215.54
  5314.4   232.6  5381.4  236.55  5426.1  236.85  5507.8  235.98  5614.2  229.92
  5664.5  229.41  5793.3   219.8  6355.3  217.86  6442.3  217.58    6914  222.52
#Mann= 10 ,-1 , 0
  3146.5     .05       0    3841     .12       0  3903.8     .07       0
  3909.8     .12       0  4040.8     .16       0  4198.3     .05       0
    4805     .12       0  5005.5     .05       0  6355.3     .16       0
  6442.3     .05       0
#XS Ineff= 2 , 0
                          5039.8          215.97
Permanent Ineff=
       F       F
Bank Sta=4970.5,5023.9
XS Rating Curve= 0 ,0
Exp/Cntr=0.3,0.1

Type RM Length L Ch R = 1 ,11066   ,0,0,0
BEGIN DESCRIPTION:
BULL CREEK 1.0
END DESCRIPTION:
XS GIS Cut Line= 3
      3610841.72     10242475.25      3610320.87      10241954.4
       3607213.2     10243829.42
#Sta/Elev= 30
  2676.8  226.07    2771  228.91  2877.1  229.14  3039.7  223.96  3188.2  227.86
  3308.4  225.35  3417.8  227.09  3470.2  224.46  3518.7  219.75  3555.6  219.05
  3576.9  214.66  3614.6  210.77  3867.1  209.69  4181.1  210.24  4990.1  212.78
  5005.6  209.83    5012  212.59  5021.1  212.73  5333.6  210.63    5683  210.66
  5719.9   208.5  5864.6   210.2  6655.8  206.78  6658.5  206.28  6661.8  206.78
  6704.1  208.35  6810.8  217.89    6906  223.66  6985.8  223.25  7042.9  220.85
#Mann= 6 ,-1 , 0
  2676.8     .05       0  3614.6     .07       0  3867.1      .1       0
  4181.1     .05       0  6655.8     .03       0  6661.8     .05       0
Bank Sta=4990.1,5021.1
XS Rating Curve= 0 ,0
Exp/Cntr=0.3,0.1

Chan Stop Cuts=-1
Use User Specified Reach Order=0
Composite Channel Slope=5