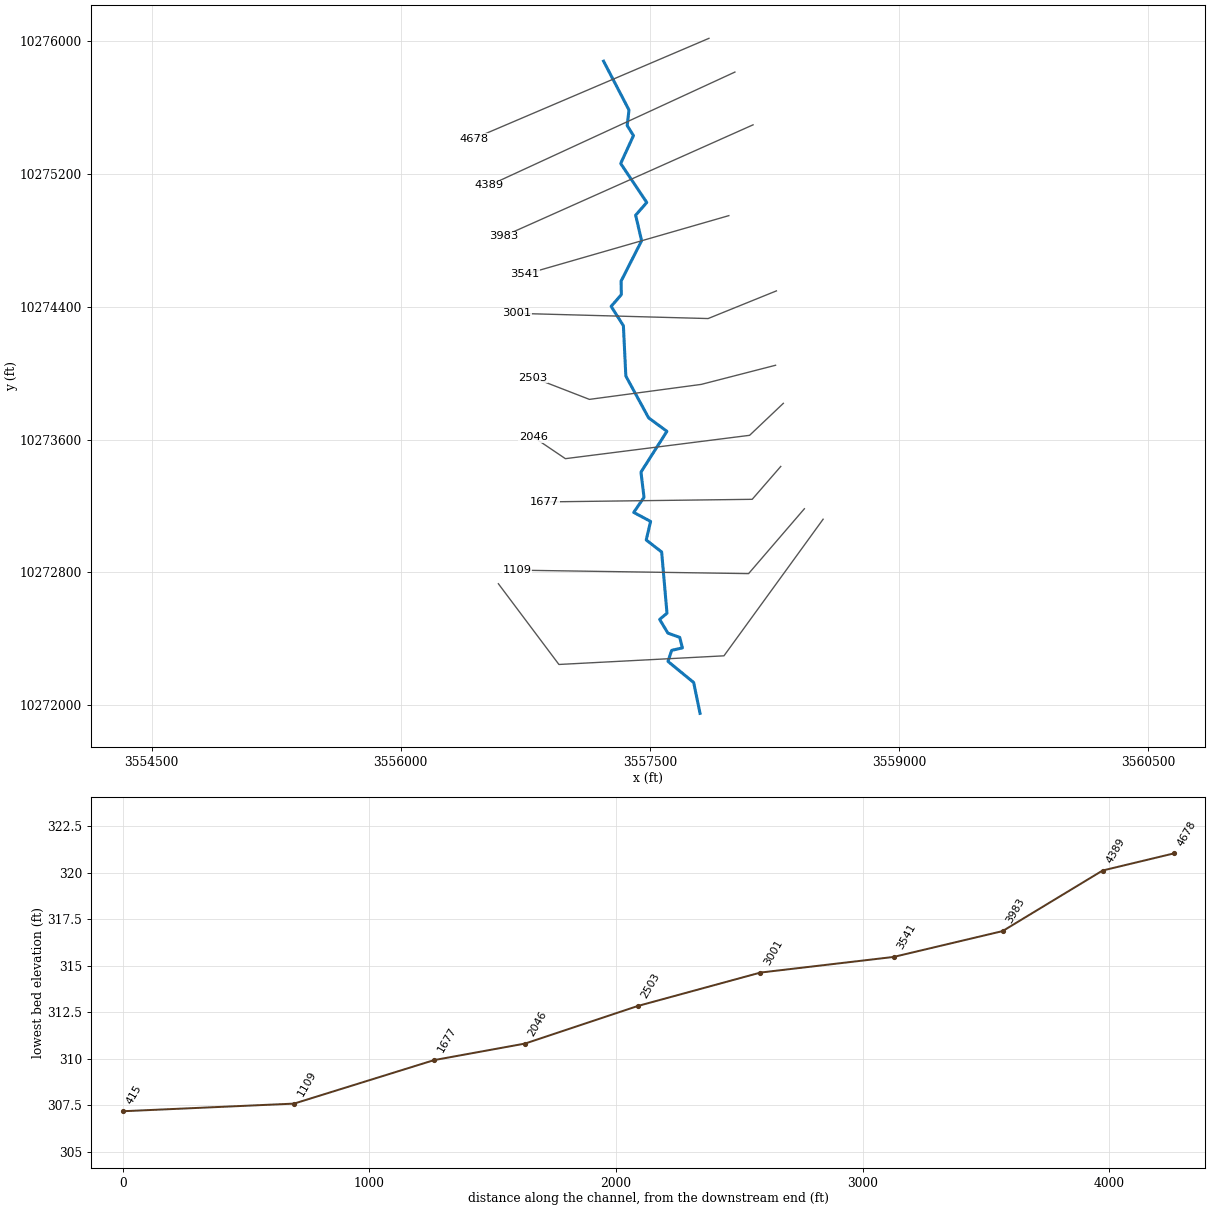
--- MATHISCREEKTRIB1.prj (project) ---

Proj Title=MATHIS CREEK TRIB 10
Current Plan=p01
Default Exp/Contr=0.3,0.1
English Units
Geom File=g01
Flow File=f01
Plan File=p01
Y Axis Title=Elevation
X Axis Title(PF)=Main Channel Distance
X Axis Title(XS)=Station
BEGIN DESCRIPTION:
UNT05204 IN WICK
END DESCRIPTION:
DSS Export Rating Curves= 0
DSS Export Rating Curve Sorted= 0
DSS Export Volume Flow Curves= 0
DXF OffsetX= 0
DXF OffsetY= 0
DXF ScaleX= 1
DXF ScaleY= 10

--- MATHISCREEKTRIB1.p01 (plan) ---

Plan Title=Multiple Run
Short Identifier=Multiple
Geom File=g01
Flow File=f01
Subcritical Flow
K Sum by GR= 0
Std Step Tol= 0.01
Critical Tol= 0.01
Num of Std Step Trials= 20
Max Error Tol= 0.3
Flow Tol Ratio= 0.001
Split Flow NTrial= 30
Split Flow Tol= 0.02
Split Flow Ratio= 0.02
Log Output Level= 0
Friction Slope Method= 1
Unsteady Friction Slope Method= 2
Unsteady Bridges Friction Slope Method= 1
Parabolic Critical Depth
Global Vel Dist=  1 , 1 , 1
Global Log Level= 0
CheckData=True
Encroach Param= -1, 0, 0, 0
BEGIN DESCRIPTION:
Multiple Run
END DESCRIPTION:

--- MATHISCREEKTRIB1.f01 (steady flow) ---

Flow Title=Multiple
Program Version=4.10
Number of Profiles= 7
Profile Names=10-year,25-year,50-year,1pct_min,100-year,1pct_plu,500-year
River Rch & RM=UNT05204 IN WICK,Reach-1         ,4678
     431     568     677     591     800    1082    1119
River Rch & RM=MATHISCRTRIB10,Reach-1         ,4678
     431     568     677     591     800    1082    1119
Boundary for River Rch & Prof#=MATHISCRTRIB10,Reach-1         , 1
Up Type= 0
Dn Type= 3
Dn Slope=0.005
Boundary for River Rch & Prof#=MATHISCRTRIB10,Reach-1         , 2
Up Type= 0
Dn Type= 3
Dn Slope=0.005
Boundary for River Rch & Prof#=MATHISCRTRIB10,Reach-1         , 3
Up Type= 0
Dn Type= 3
Dn Slope=0.005
Boundary for River Rch & Prof#=MATHISCRTRIB10,Reach-1         , 4
Up Type= 0
Dn Type= 3
Dn Slope=0.005
Boundary for River Rch & Prof#=MATHISCRTRIB10,Reach-1         , 5
Up Type= 0
Dn Type= 3
Dn Slope=0.005
Boundary for River Rch & Prof#=MATHISCRTRIB10,Reach-1         , 6
Up Type= 0
Dn Type= 3
Dn Slope=0.005
Boundary for River Rch & Prof#=MATHISCRTRIB10,Reach-1         , 7
Up Type= 0
Dn Type= 3
Dn Slope=0.005
DSS Import GetInterval= 0
DSS Import GetPeak= 0
DSS Import FillOption= 0

--- MATHISCREEKTRIB1.g01 (geometry) ---

Geom Title=Existing Conditions
Program Version=4.10

River Reach=MATHISCRTRIB10  ,Reach-1
Reach XY= 30
      3557221.13     10275879.18      3557374.28     10275584.91
      3557363.46     10275491.68      3557401.12     10275430.95
       3557324.3      10275262.9      3557481.19     10275028.35
       3557414.4     10274951.56      3557450.16     10274797.67
      3557326.53     10274554.41      3557328.21     10274473.25
       3557266.8     10274402.68      3557340.52     10274285.91
      3557355.25       10273983.      3557492.17     10273731.63
      3557602.57     10273650.05      3557446.35     10273404.49
      3557464.71      10273252.8      3557402.73     10273161.89
      3557504.37     10273107.49        3557478.     10272995.97
      3557570.88     10272923.48        3557603.     10272554.56
      3557558.73     10272517.67      3557608.61     10272434.92
      3557679.72      10272409.4      3557695.81     10272346.03
      3557631.21     10272331.04      3557609.21     10272264.48
      3557763.66     10272137.56      3557802.11     10271951.64

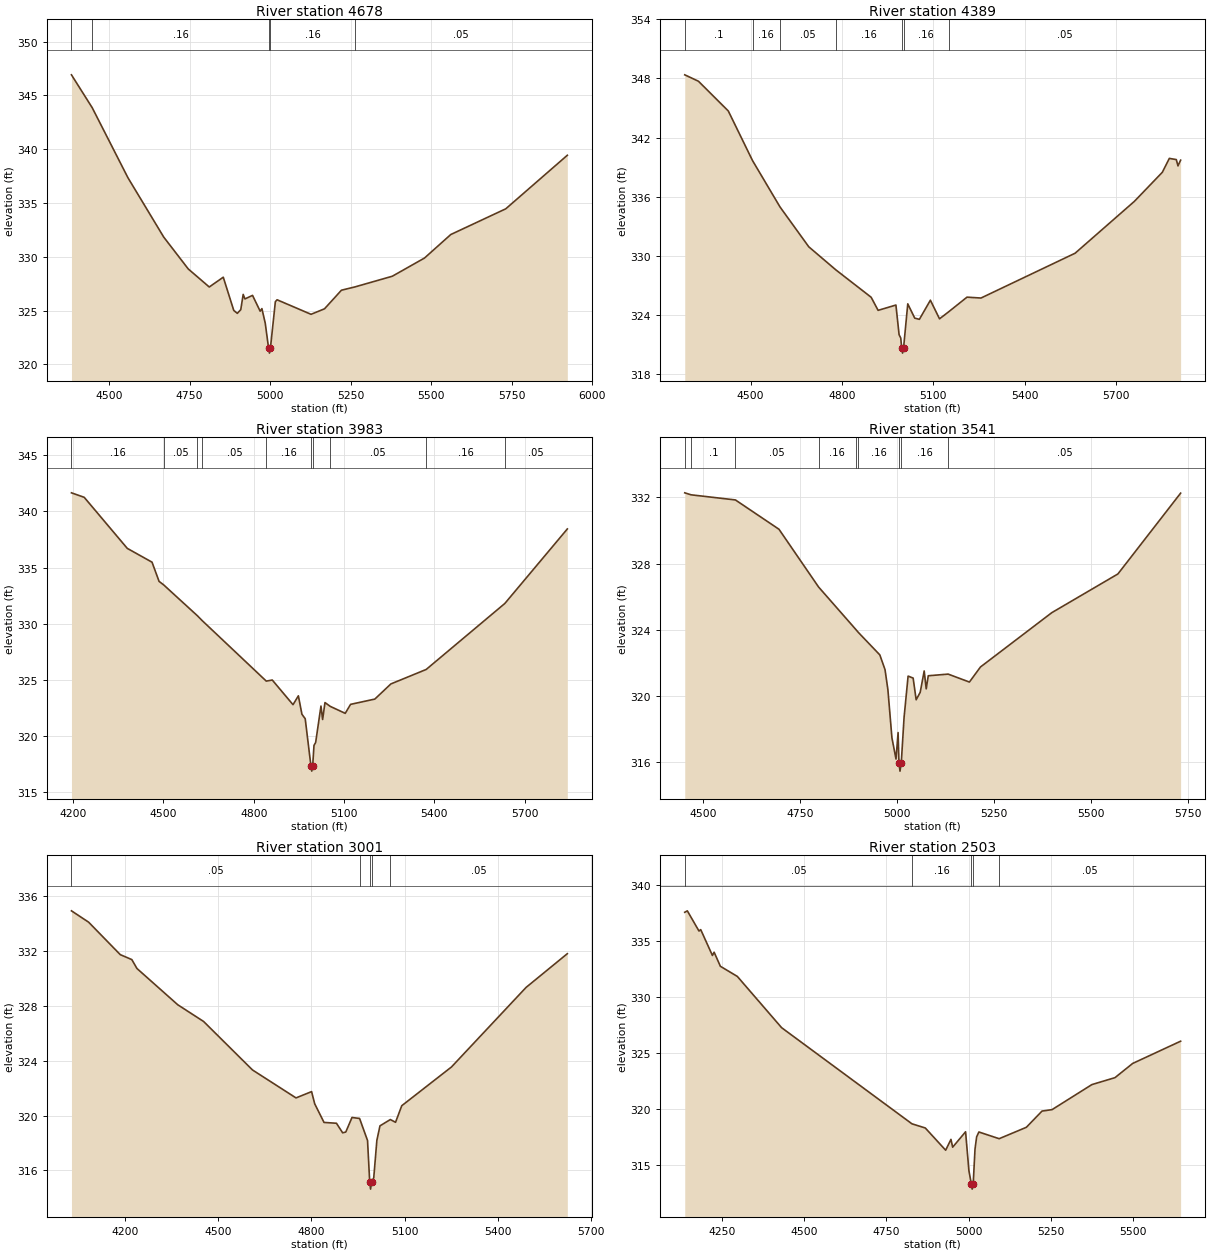
Type RM Length L Ch R = 1 ,4678    ,289,289,289
BEGIN DESCRIPTION:
UNT05204 IN WICK 9.0
END DESCRIPTION:
XS GIS Cut Line= 2
      3557855.77     10276016.72      3556439.12     10275412.56
#Sta/Elev= 30
  4383.2  346.92  4447.7  343.86  4558.8  337.34  4669.8  331.83  4745.9  328.87
  4811.2  327.19  4854.7   328.1  4887.3  325.01  4898.4  324.74    4909  325.08
  4916.6   326.5    4922  326.08  4945.6  326.41  4969.3  324.94  4974.7  325.18
  4985.1  323.82  4995.3  321.54  4998.1  321.04  5001.3  321.54  5016.5  325.83
  5021.9     326  5127.3  324.65  5169.1  325.16  5221.7  326.89    5264   327.2
  5379.7  328.19  5479.6  329.88  5561.4  332.07  5732.1  334.46  5923.3  339.44
#Mann= 5 ,-1 , 0
  4383.2      .1       0  4447.7     .16       0  4995.3     .07       0
  5001.3     .16       0    5264     .05       0
Bank Sta=4995.3,5001.3
XS Rating Curve= 0 ,0
Exp/Cntr=0.3,0.1

Type RM Length L Ch R = 1 ,4389    ,406,406,406
BEGIN DESCRIPTION:
UNT05204 IN WICK 8.0
END DESCRIPTION:
XS GIS Cut Line= 2
      3558012.03      10275813.6       3556532.9     10275131.33
#Sta/Elev= 30
  4283.9  348.36  4328.9  347.71    4427  344.69  4506.5  339.66  4596.9  334.95
  4691.3  330.91  4779.8  328.58  4896.2  325.79  4919.1  324.46  4977.6     325
    4988  321.99  4993.5  321.65  4996.6  320.62  4999.4  320.12  5002.6  320.62
  5016.5  325.12  5039.4  323.67  5054.7  323.55  5090.8  325.49  5120.8   323.6
  5150.3   324.3  5211.1   325.8    5257  325.71  5566.3  330.26  5760.9  335.52
  5852.7  338.47  5875.7  339.88  5898.6  339.76  5904.1  339.12  5912.8   339.7
#Mann= 7 ,-1 , 0
  4283.9      .1       0  4506.5     .16       0  4596.9     .05       0
  4779.8     .16       0  4996.6     .07       0  5002.6     .16       0
  5150.3     .05       0
Bank Sta=4996.6,5002.6
XS Rating Curve= 0 ,0
Exp/Cntr=0.3,0.1

Type RM Length L Ch R = 1 ,3983    ,442,442,442
BEGIN DESCRIPTION:
UNT05204 IN WICK 7.0
END DESCRIPTION:
XS GIS Cut Line= 2
      3558121.45     10275495.91      3556616.66     10274824.22
#Sta/Elev= 30
  4194.4  341.66  4236.8  341.26  4379.9  336.71  4462.2  335.48  4485.5  333.77
  4500.7  333.46  4612.8  330.71  4629.4  330.26  4841.9  324.88  4861.7  324.98
  4930.7  322.78  4948.5  323.57  4960.3  321.93  4971.2  321.53  4990.1  317.36
  4992.9  316.86  4996.1  317.36  5000.4  319.15  5005.9  319.41  5023.6  322.66
  5029.1  321.46  5036.9  322.97  5054.5  322.63  5104.2  322.01    5122  322.81
  5202.6  323.28  5255.9  324.63  5373.3  325.92  5634.6   331.8  5842.3  338.44
#Mann= 10 ,-1 , 0
  4194.4     .16       0  4500.7     .05       0  4612.8     .16       0
  4629.4     .05       0  4841.9     .16       0  4990.1     .07       0
  4996.1     .16       0  5054.5     .05       0  5373.3     .16       0
  5634.6     .05       0
Bank Sta=4990.1,4996.1
XS Rating Curve= 0 ,0
Exp/Cntr=0.3,0.1

Type RM Length L Ch R = 1 ,3541    ,540,540,540
BEGIN DESCRIPTION:
Mapping XS 11afbd6d
END DESCRIPTION:
XS GIS Cut Line= 2
      3557975.57     10274949.02      3556746.76     10274594.96
#Sta/Elev= 30
  4453.2  332.28  4469.5  332.16  4583.9  331.85  4696.2  330.08  4798.4  326.59
  4894.6  324.02  4900.8  323.85  4956.3  322.49  4969.7   321.6  4977.1  320.39
  4987.5  317.48    4998   316.2  5003.4   317.8  5005.6  315.97  5008.3  315.47
  5011.6  315.97  5018.8  318.71  5029.2  321.21  5042.2  321.09    5050  319.78
  5060.4  320.23  5070.7  321.52  5075.9  320.44  5081.2  321.23  5132.5  321.33
  5187.3  320.85  5215.8  321.76  5399.7  325.04  5570.3  327.38    5732  332.26
#Mann= 9 ,-1 , 0
  4453.2     .05       0  4469.5      .1       0  4583.9     .05       0
  4798.4     .16       0  4894.6     .05       0  4900.8     .16       0
  5005.6     .07       0  5011.6     .16       0  5132.5     .05       0
Bank Sta=5005.6,5011.6
XS Rating Curve= 0 ,0
Exp/Cntr=0.3,0.1

Type RM Length L Ch R = 1 ,3001    ,498,498,498
BEGIN DESCRIPTION:
UNT05204 IN WICK 6.0
END DESCRIPTION:
XS GIS Cut Line= 3
      3558262.07     10274495.91       3557850.6     10274329.24
      3556699.57     10274360.49
#Sta/Elev= 30
  4028.2  334.95  4083.5  334.12  4185.3  331.75  4222.4  331.39  4238.9  330.74
  4370.3  328.09  4453.4  326.87  4610.7  323.33  4750.7  321.29  4800.8  321.75
  4810.8  320.86  4840.8   319.5  4880.8  319.44  4900.8  318.74  4910.8   318.8
  4930.8  319.86  4955.2  319.79  4980.8  318.18  4987.8  315.13  4990.6  314.63
  4993.8  315.13  5000.8  315.46  5010.8  318.19  5020.8  319.25  5054.1  319.71
  5070.9  319.51  5090.9  320.72  5250.9  323.55    5491  329.36  5623.6  331.82
#Mann= 5 ,-1 , 0
  4028.2     .05       0  4955.2     .16       0  4987.8     .07       0
  4993.8     .16       0  5054.1     .05       0
Bank Sta=4987.8,4993.8
XS Rating Curve= 0 ,0
Exp/Cntr=0.3,0.1

Type RM Length L Ch R = 1 ,2503    ,457,457,457
BEGIN DESCRIPTION:
UNT05204 IN WICK 5.0
END DESCRIPTION:
XS GIS Cut Line= 4
      3558256.87     10274047.99      3557809.49     10273932.79
      3557135.88     10273842.52      3556796.32     10273974.18
#Sta/Elev= 30
  4137.7  337.59  4145.5  337.72    4181  335.91  4186.2  336.04  4221.7  333.73
  4226.9  334.02  4245.9  332.76  4297.5  331.85  4431.8  327.27  4827.7  318.67
  4868.1   318.3    4930  316.31  4946.1  317.28  4951.2  316.58  4990.5  317.96
  5000.6  314.48  5007.7  313.33  5010.5  312.83  5013.7  313.33  5019.1   316.4
  5024.1  317.51  5030.9  317.94  5092.4  317.34  5175.1  318.36  5222.6  319.81
  5253.1  319.94  5374.1  322.18  5444.2   322.8  5497.9  324.07  5643.5  326.06
#Mann= 5 ,-1 , 0
  4137.7     .05       0  4827.7     .16       0  5007.7     .07       0
  5013.7     .16       0  5092.4     .05       0
Bank Sta=5007.7,5013.7
XS Rating Curve= 0 ,0
Exp/Cntr=0.3,0.1

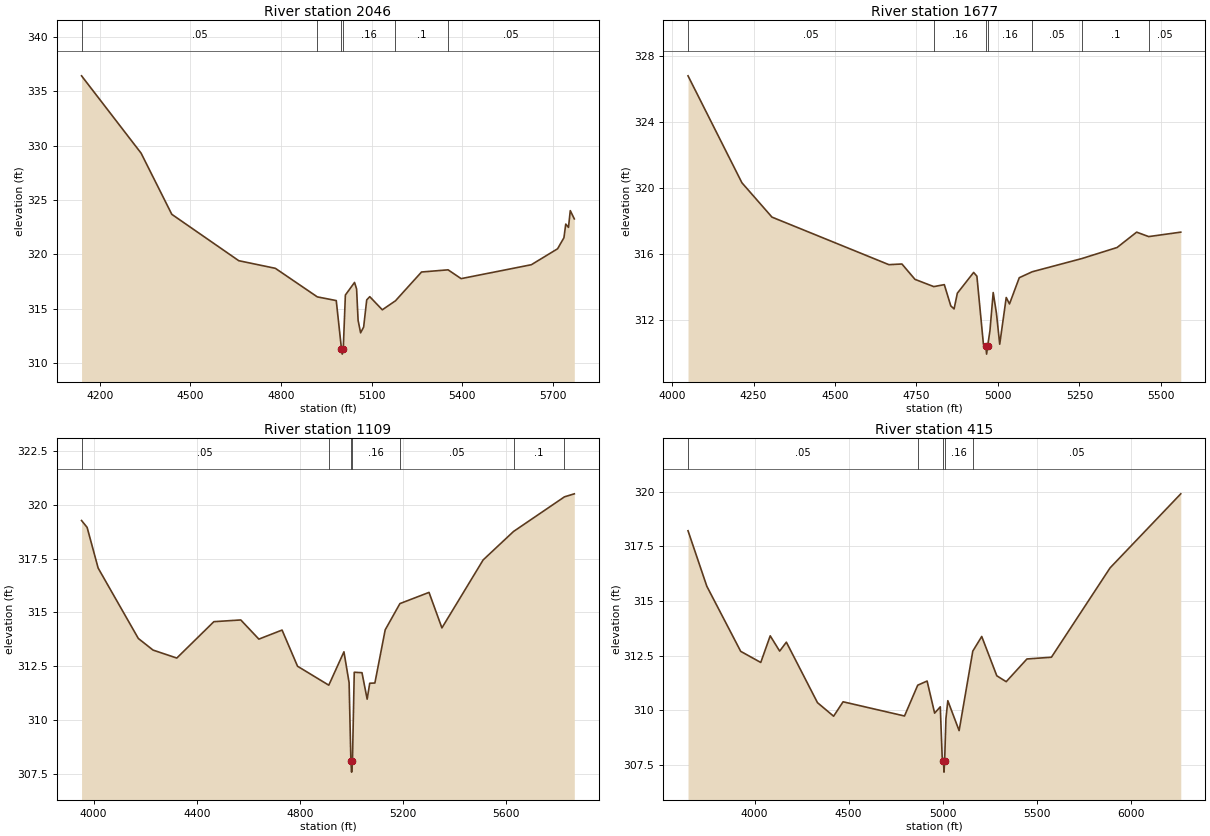
Type RM Length L Ch R = 1 ,2046    ,369,369,369
BEGIN DESCRIPTION:
UNT05204 IN WICK 4.0
END DESCRIPTION:
XS GIS Cut Line= 4
      3558303.75     10273818.85       3558100.6     10273626.11
      3556991.23     10273485.49      3556798.48     10273615.72
#Sta/Elev= 30
  4139.6  336.43  4336.7  329.31  4438.3  323.68    4660  319.41    4781  318.71
  4919.9  316.08  4982.6  315.74  4999.8  311.31  5002.5  310.81  5005.8  311.31
  5012.8  316.25  5043.1  317.41  5049.9  316.81  5054.9  313.92  5063.2  312.77
  5073.3  313.31  5083.4   315.8  5093.5   316.1    5135  314.89  5178.6  315.72
  5264.8  318.37  5352.7  318.57  5395.9  317.76  5628.3  319.04  5715.2  320.51
  5736.2  321.53  5742.2  322.78  5751.2  322.48  5757.2  324.02  5770.5  323.26
#Mann= 6 ,-1 , 0
  4139.6     .05       0  4919.9     .16       0  4999.8     .07       0
  5005.8     .16       0  5178.6      .1       0  5352.7     .05       0
Bank Sta=4999.8,5005.8
XS Rating Curve= 0 ,0
Exp/Cntr=0.3,0.1

Type RM Length L Ch R = 1 ,1677    ,568,568,568
BEGIN DESCRIPTION:
UNT05204 IN WICK 2.0
END DESCRIPTION:
XS GIS Cut Line= 3
      3558288.12     10273438.64      3558116.23      10273240.7
      3556866.68     10273225.08
#Sta/Elev= 30
  4049.1  326.78  4214.5   320.3  4306.7  318.22  4665.4  315.34  4705.4  315.38
  4745.4  314.45  4803.2  314.01  4835.4  314.13  4855.4  312.84  4865.4  312.66
  4875.4  313.61  4925.4  314.87  4935.4  314.64  4955.4  310.52  4962.4  310.42
  4965.2  309.92  4968.4  310.42  4975.4  311.33  4985.4  313.65  4995.4  312.39
  5005.4  310.52  5025.4  313.35  5035.4  312.96  5065.4  314.55  5105.2  314.91
  5257.4  315.71  5365.5  316.38  5425.5  317.31  5462.5  317.04  5560.9  317.31
#Mann= 7 ,-1 , 0
  4049.1     .05       0  4803.2     .16       0  4962.4     .07       0
  4968.4     .16       0  5105.2     .05       0  5257.4      .1       0
  5462.5     .05       0
Bank Sta=4962.4,4968.4
XS Rating Curve= 0 ,0
Exp/Cntr=0.3,0.1

Type RM Length L Ch R = 1 ,1109    ,694,694,694
BEGIN DESCRIPTION:
Mapping XS 7b131da9
END DESCRIPTION:
XS GIS Cut Line= 3
      3558430.46     10273183.89      3558094.51     10272793.26
      3556698.69     10272814.09
#Sta/Elev= 30
  3953.2  319.27  3974.8  318.95  4017.6  317.06  4173.4  313.79  4230.5  313.25
  4322.6  312.88  4466.4  314.57  4570.8  314.65  4640.9  313.76  4730.9  314.18
  4790.9   312.5  4912.1  311.62  4970.9  313.17  4990.9  311.74  4997.9  308.08
  5000.6  307.58  5003.9  308.08  5010.9  312.22  5040.9   312.2  5060.9  310.97
  5070.9  311.71  5090.9  311.72  5130.9  314.19    5188  315.41  5300.9  315.93
  5350.9  314.28  5510.9  317.44  5628.6  318.76  5826.2  320.37  5864.4  320.51
#Mann= 7 ,-1 , 0
  3953.2     .05       0  4912.1     .16       0  4997.9     .07       0
  5003.9     .16       0    5188     .05       0  5628.6      .1       0
  5826.2     .05       0
Bank Sta=4997.9,5003.9
XS Rating Curve= 0 ,0
Exp/Cntr=0.3,0.1

Type RM Length L Ch R = 1 ,415     ,0,0,0
BEGIN DESCRIPTION:
UNT05204 IN WICK 1.0
END DESCRIPTION:
XS GIS Cut Line= 4
      3558543.31     10273120.91      3557946.18     10272298.23
      3556952.25     10272246.14      3556587.66     10272732.27
#Sta/Elev= 30
  3646.5  318.22  3746.4  315.68  3926.5   312.7  4033.2  312.19  4083.5  313.41
  4133.7  312.71  4169.3  313.12  4334.7  310.35  4420.5  309.73  4470.8  310.39
  4797.3  309.74  4867.7  311.15  4917.5  311.34  4957.5  309.87  4987.6  310.16
  4997.6  307.86  5004.6  307.67  5007.3  307.17  5010.6  307.67  5017.6  309.62
  5027.6  310.44  5087.7  309.07  5160.4  312.71  5207.9  313.38    5288  311.58
    5338  311.31  5448.2  312.35  5578.4  312.43  5890.2  316.52    6266  319.91
#Mann= 5 ,-1 , 0
  3646.5     .05       0  4867.7     .16       0  5004.6     .07       0
  5010.6     .16       0  5160.4     .05       0
Bank Sta=5004.6,5010.6
XS Rating Curve= 0 ,0
Exp/Cntr=0.3,0.1

Chan Stop Cuts=-1
Use User Specified Reach Order=0
Composite Channel Slope=5