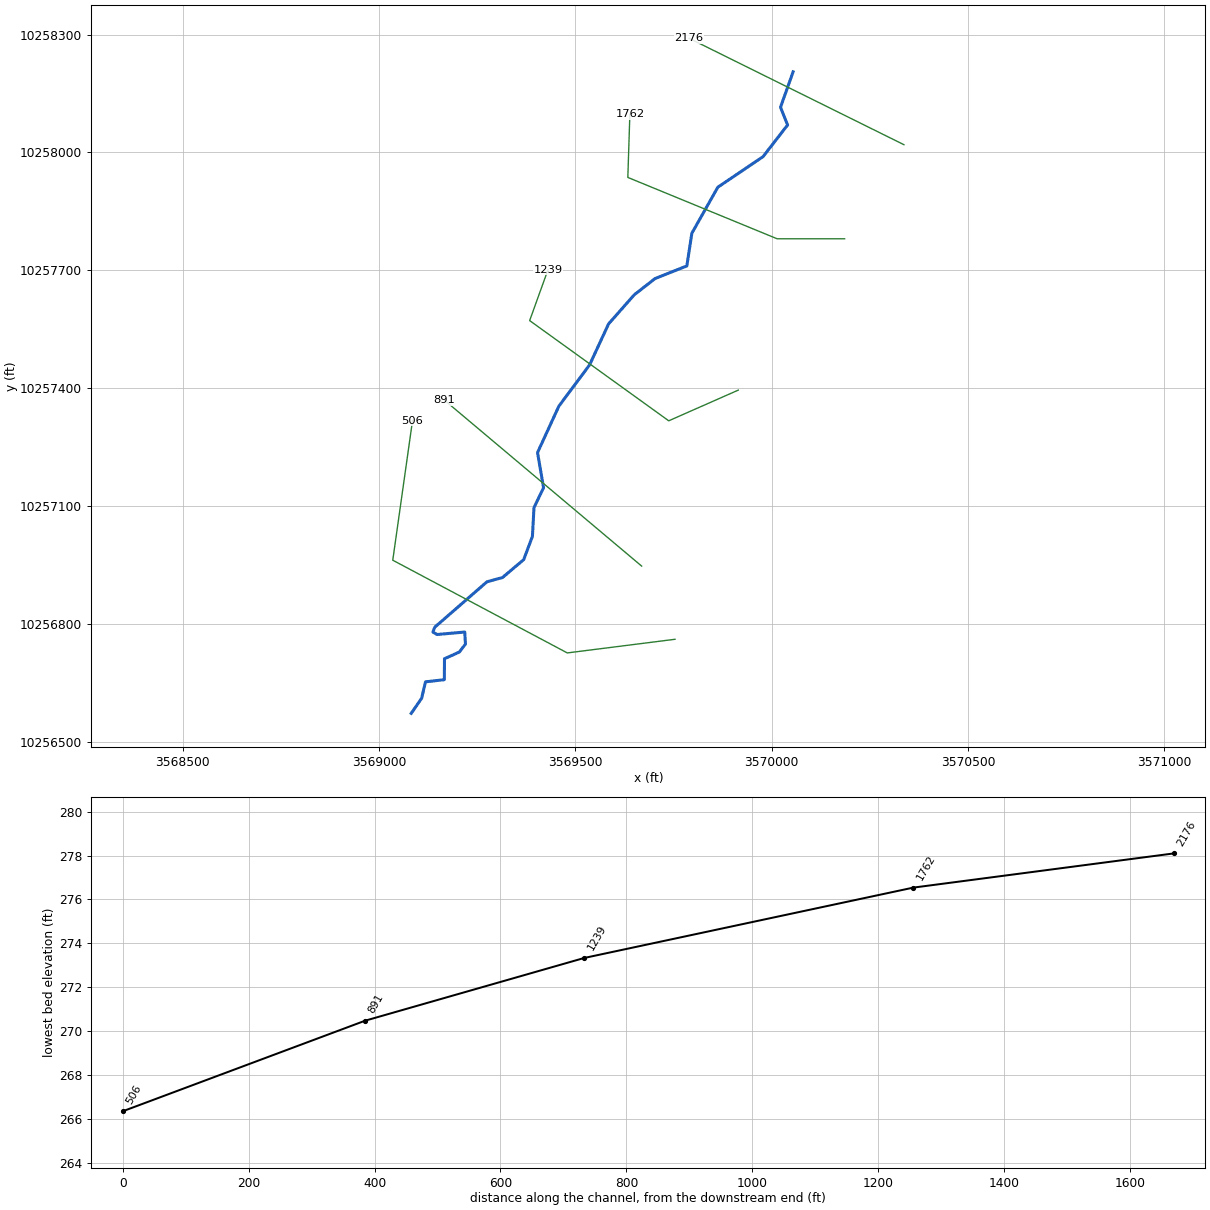
--- MATHISCREEKTRIB2.prj (project) ---

Proj Title=MATHIS CREEK TRIB 2
Current Plan=p01
Default Exp/Contr=0.3,0.1
English Units
Geom File=g01
Flow File=f01
Plan File=p01
Y Axis Title=Elevation
X Axis Title(PF)=Main Channel Distance
X Axis Title(XS)=Station
BEGIN DESCRIPTION:
UNT05225 IN WICK
END DESCRIPTION:
DSS Export Rating Curves= 0
DSS Export Rating Curve Sorted= 0
DSS Export Volume Flow Curves= 0
DXF OffsetX= 0
DXF OffsetY= 0
DXF ScaleX= 1
DXF ScaleY= 10

--- MATHISCREEKTRIB2.p01 (plan) ---

Plan Title=Multiple Run
Short Identifier=Multiple
Geom File=g01
Flow File=f01
Subcritical Flow
K Sum by GR= 0
Std Step Tol= 0.01
Critical Tol= 0.01
Num of Std Step Trials= 20
Max Error Tol= 0.3
Flow Tol Ratio= 0.001
Split Flow NTrial= 30
Split Flow Tol= 0.02
Split Flow Ratio= 0.02
Log Output Level= 0
Friction Slope Method= 1
Unsteady Friction Slope Method= 2
Unsteady Bridges Friction Slope Method= 1
Parabolic Critical Depth
Global Vel Dist=  1 , 1 , 1
Global Log Level= 0
CheckData=True
Encroach Param= -1, 0, 0, 0
BEGIN DESCRIPTION:
Multiple Run
END DESCRIPTION:

--- MATHISCREEKTRIB2.f01 (steady flow) ---

Flow Title=Multiple
Program Version=4.10
Number of Profiles= 7
Profile Names=10-year,25-year,50-year,1pct_min,100-year,1pct_plu,500-year
River Rch & RM=UNT05225 IN WICK,Reach-1         ,2176
     304     394     465     403     545     737     751
River Rch & RM=MATHISCRTRB2,Reach-1         ,2176
     304     394     465     403     545     737     751
Boundary for River Rch & Prof#=MATHISCRTRB2,Reach-1         , 1
Up Type= 0
Dn Type= 3
Dn Slope=0.005
Boundary for River Rch & Prof#=MATHISCRTRB2,Reach-1         , 2
Up Type= 0
Dn Type= 3
Dn Slope=0.005
Boundary for River Rch & Prof#=MATHISCRTRB2,Reach-1         , 3
Up Type= 0
Dn Type= 3
Dn Slope=0.005
Boundary for River Rch & Prof#=MATHISCRTRB2,Reach-1         , 4
Up Type= 0
Dn Type= 3
Dn Slope=0.005
Boundary for River Rch & Prof#=MATHISCRTRB2,Reach-1         , 5
Up Type= 0
Dn Type= 3
Dn Slope=0.005
Boundary for River Rch & Prof#=MATHISCRTRB2,Reach-1         , 6
Up Type= 0
Dn Type= 3
Dn Slope=0.005
Boundary for River Rch & Prof#=MATHISCRTRB2,Reach-1         , 7
Up Type= 0
Dn Type= 3
Dn Slope=0.005
DSS Import GetInterval= 0
DSS Import GetPeak= 0
DSS Import FillOption= 0

--- MATHISCREEKTRIB2.g01 (geometry) ---

Geom Title=Existing Conditions
Program Version=4.10

River Reach=MATHISCRTRB2    ,Reach-1
Reach XY= 30
       3570054.6     10258205.39      3570022.53     10258115.21
      3570040.58     10258070.08      3569978.07      10257989.4
      3569862.85      10257911.5      3569796.75     10257794.37
      3569783.98     10257711.05      3569703.19     10257679.01
      3569649.95      10257637.5      3569584.77      10257563.6
      3569536.44     10257459.29      3569458.05     10257353.89
      3569403.76     10257235.76       3569419.1     10257146.25
      3569394.76     10257095.65      3569390.71     10257022.19
       3569368.5     10256963.12       3569314.5     10256917.55
        3569275.     10256906.75      3569142.24      10256791.2
      3569137.22     10256778.81      3569147.69     10256772.51
      3569218.36     10256778.76      3569220.25     10256748.17
      3569204.67     10256727.83       3569166.8     10256710.79
      3569166.44     10256657.43      3569118.45     10256651.98
      3569108.65     10256610.22      3569082.11     10256571.64

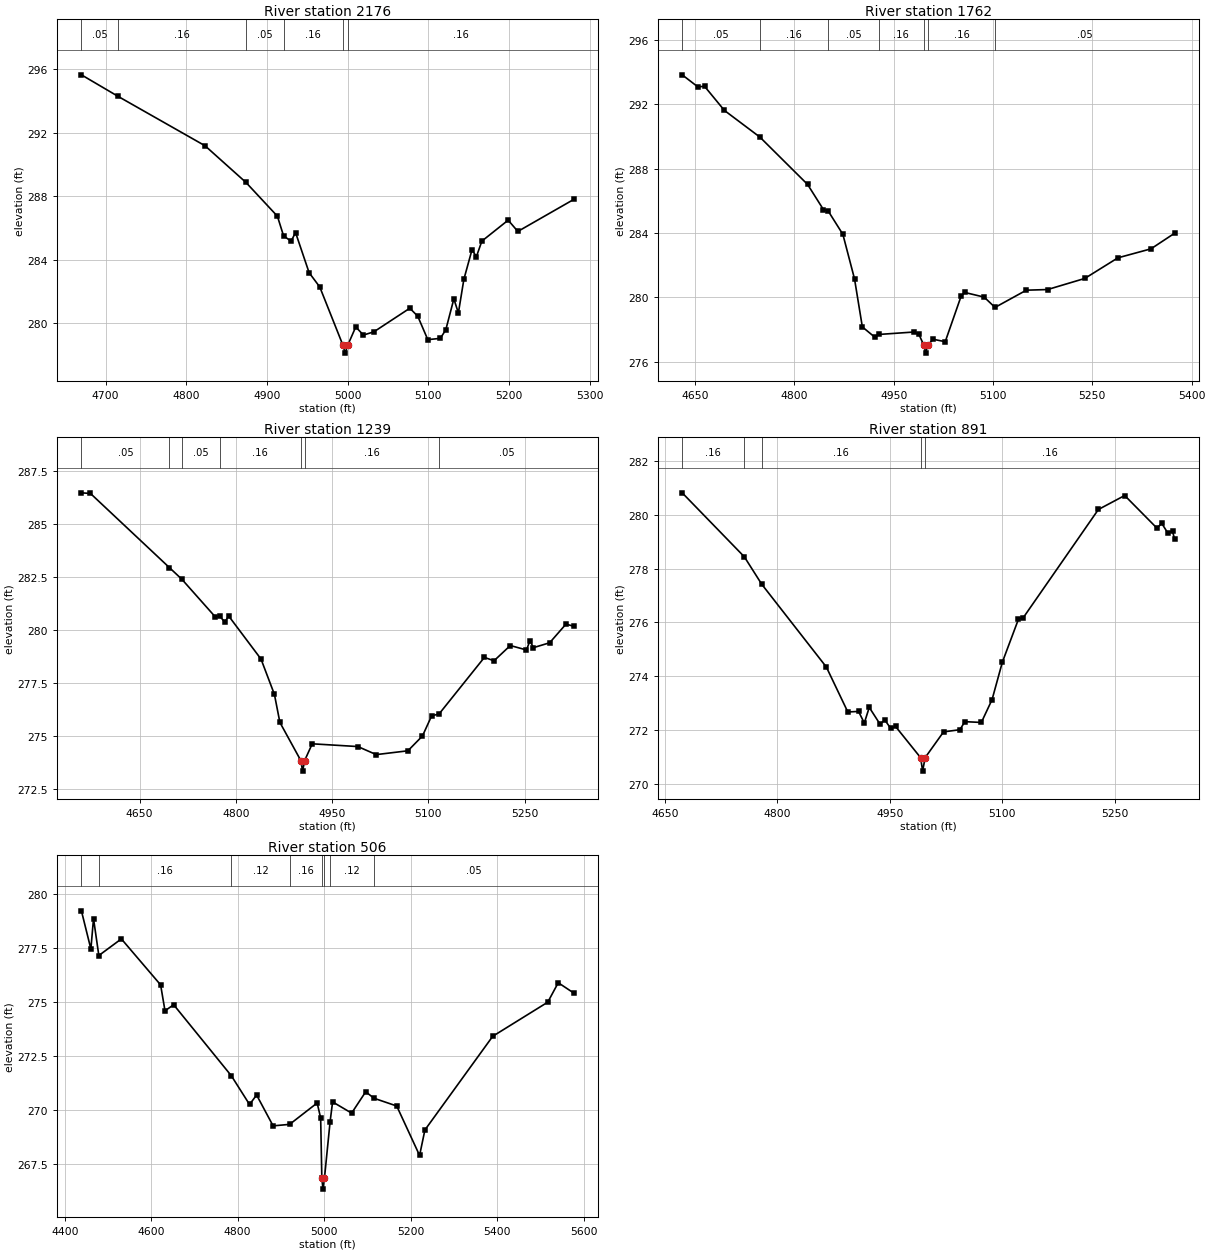
Type RM Length L Ch R = 1 ,2176    ,414,414,414
BEGIN DESCRIPTION:
UNT05225 IN WICK 4.0
END DESCRIPTION:
XS GIS Cut Line= 2
      3570336.83     10258019.82      3569789.92     10258290.67
#Sta/Elev= 30
    4670  295.64  4715.5  294.28  4823.2  291.17  4873.9  288.86  4912.9  286.73
  4920.5   285.5  4929.8  285.15  4935.4   285.7  4952.2  283.17  4965.4  282.27
  4994.1   278.6  4996.8   278.1  5000.1   278.6    5010  279.75  5019.5  279.24
  5032.4  279.44    5077  280.93  5086.8  280.43  5099.3  278.95  5114.8  279.03
  5121.6  279.57  5131.6  281.52  5137.2  280.63    5144  282.75    5154   284.6
  5159.6  284.19  5166.3  285.16  5198.9  286.48  5210.9  285.77  5280.3  287.79
#Mann= 6 ,-1 , 0
    4670     .05       0  4715.5     .16       0  4873.9     .05       0
  4920.5     .16       0  4994.1     .07       0  5000.1     .16       0
Bank Sta=4994.1,5000.1
XS Rating Curve= 0 ,0
Exp/Cntr=0.3,0.1

Type RM Length L Ch R = 1 ,1762    ,523,523,523
BEGIN DESCRIPTION:
UNT05225 IN WICK 3.0
END DESCRIPTION:
XS GIS Cut Line= 4
      3570185.77     10257780.24      3570013.91     10257780.24
       3569633.7     10257936.49      3569638.88     10258097.27
#Sta/Elev= 30
  4630.5  293.83  4654.2  293.08  4664.2  293.12  4694.2  291.62  4747.9  289.96
  4819.9  287.02  4843.8  285.46    4851  285.37  4873.2  283.92  4890.8  281.15
  4902.6  278.17  4921.1  277.54  4927.6   277.7  4979.9  277.85  4988.1   277.7
  4995.4  277.04  4998.2  276.54  5001.4  277.04  5009.7   277.4  5027.8  277.25
  5051.8  280.08  5057.2  280.31  5086.6  280.02    5103  279.38  5150.3  280.45
  5182.4  280.49  5238.6  281.18  5288.6  282.46  5338.6  283.02  5374.3  283.99
#Mann= 7 ,-1 , 0
  4630.5     .05       0  4747.9     .16       0    4851     .05       0
  4927.6     .16       0  4995.4     .07       0  5001.4     .16       0
    5103     .05       0
Bank Sta=4995.4,5001.4
XS Rating Curve= 0 ,0
Exp/Cntr=0.3,0.1

Type RM Length L Ch R = 1 ,1239    ,348,348,348
BEGIN DESCRIPTION:
UNT05225 IN WICK 2.0
END DESCRIPTION:
XS GIS Cut Line= 4
      3569914.98     10257394.84      3569737.86      10257316.7
       3569383.7      10257571.9      3569430.25     10257701.04
#Sta/Elev= 30
  4559.4  286.47  4573.5  286.44  4696.5  282.94  4715.9  282.39  4768.1  280.61
  4775.1  280.64  4782.8  280.37    4789  280.65  4839.3  278.62  4860.2  276.95
  4868.7  275.63  4901.3  273.83  4904.1  273.33  4907.3  273.83  4919.1  274.62
  4990.2  274.49  5018.9  274.11  5068.2  274.29  5090.9  274.99  5105.2  275.94
  5116.8  276.03  5187.4   278.7  5202.4  278.54  5227.8  279.26    5253  279.05
  5258.4  279.49  5263.8  279.16  5289.1  279.39  5314.5  280.27  5326.8  280.17
#Mann= 7 ,-1 , 0
  4559.4     .05       0  4696.5     .16       0  4715.9     .05       0
  4775.1     .16       0  4901.3     .07       0  4907.3     .16       0
  5116.8     .05       0
Bank Sta=4901.3,4907.3
XS Rating Curve= 0 ,0
Exp/Cntr=0.3,0.1

Type RM Length L Ch R = 1 ,891     ,385,385,385
BEGIN DESCRIPTION:
Mapping XS 1a835712
END DESCRIPTION:
XS GIS Cut Line= 2
      3569668.85     10256946.74      3569166.28      10257369.6
#Sta/Elev= 30
    4673  280.82  4755.9  278.44  4779.1  277.42  4865.3  274.34  4893.9  272.67
  4908.2  272.69  4915.9  272.26  4922.5  272.84  4936.8  272.22  4943.3  272.37
  4951.1  272.06  4957.6  272.13    4991  270.97  4993.7  270.47    4997  270.97
  5021.6  271.93  5043.4  272.01    5050  272.31    5072  272.28  5086.3  273.13
    5100  274.52  5121.5  276.12    5128  276.18  5228.1   280.2  5263.2  280.72
  5306.1  279.51  5312.7  279.68  5320.4  279.34    5327  279.39  5329.8  279.09
#Mann= 5 ,-1 , 0
    4673     .16       0  4755.9     .05       0  4779.1     .16       0
    4991     .07       0    4997     .16       0
Bank Sta=4991,4997
XS Rating Curve= 0 ,0
Exp/Cntr=0.3,0.1

Type RM Length L Ch R = 1 ,506     ,0,0,0
BEGIN DESCRIPTION:
UNT05225 IN WICK 1.0
END DESCRIPTION:
XS GIS Cut Line= 4
      3569753.81      10256760.3      3569479.53     10256725.58
      3569035.09     10256961.69      3569085.42     10257317.41
#Sta/Elev= 30
  4438.6  279.23  4460.5  277.46  4466.6  278.87  4478.9  277.16    4531  277.93
  4621.8   275.8  4631.9   274.6    4652  274.88  4785.4  271.59  4827.5  270.26
  4843.8   270.7    4882  269.27  4920.2  269.34  4983.9  270.33    4992  269.63
  4994.7  266.84  4997.4  266.34  5000.7  266.84  5013.8  269.46  5019.6  270.38
  5063.6  269.86  5096.2  270.85  5115.2  270.55  5167.9  270.19  5220.8   267.9
  5233.1  269.08    5390  273.42  5517.3     275  5541.5   275.9  5577.6  275.42
#Mann= 8 ,-1 , 0
  4438.6     .05       0  4478.9     .16       0  4785.4     .12       0
  4920.2     .16       0  4994.7     .07       0  5000.7     .16       0
  5013.8     .12       0  5115.2     .05       0
Bank Sta=4994.7,5000.7
XS Rating Curve= 0 ,0
Exp/Cntr=0.3,0.1

Chan Stop Cuts=-1
Use User Specified Reach Order=0
Composite Channel Slope=5