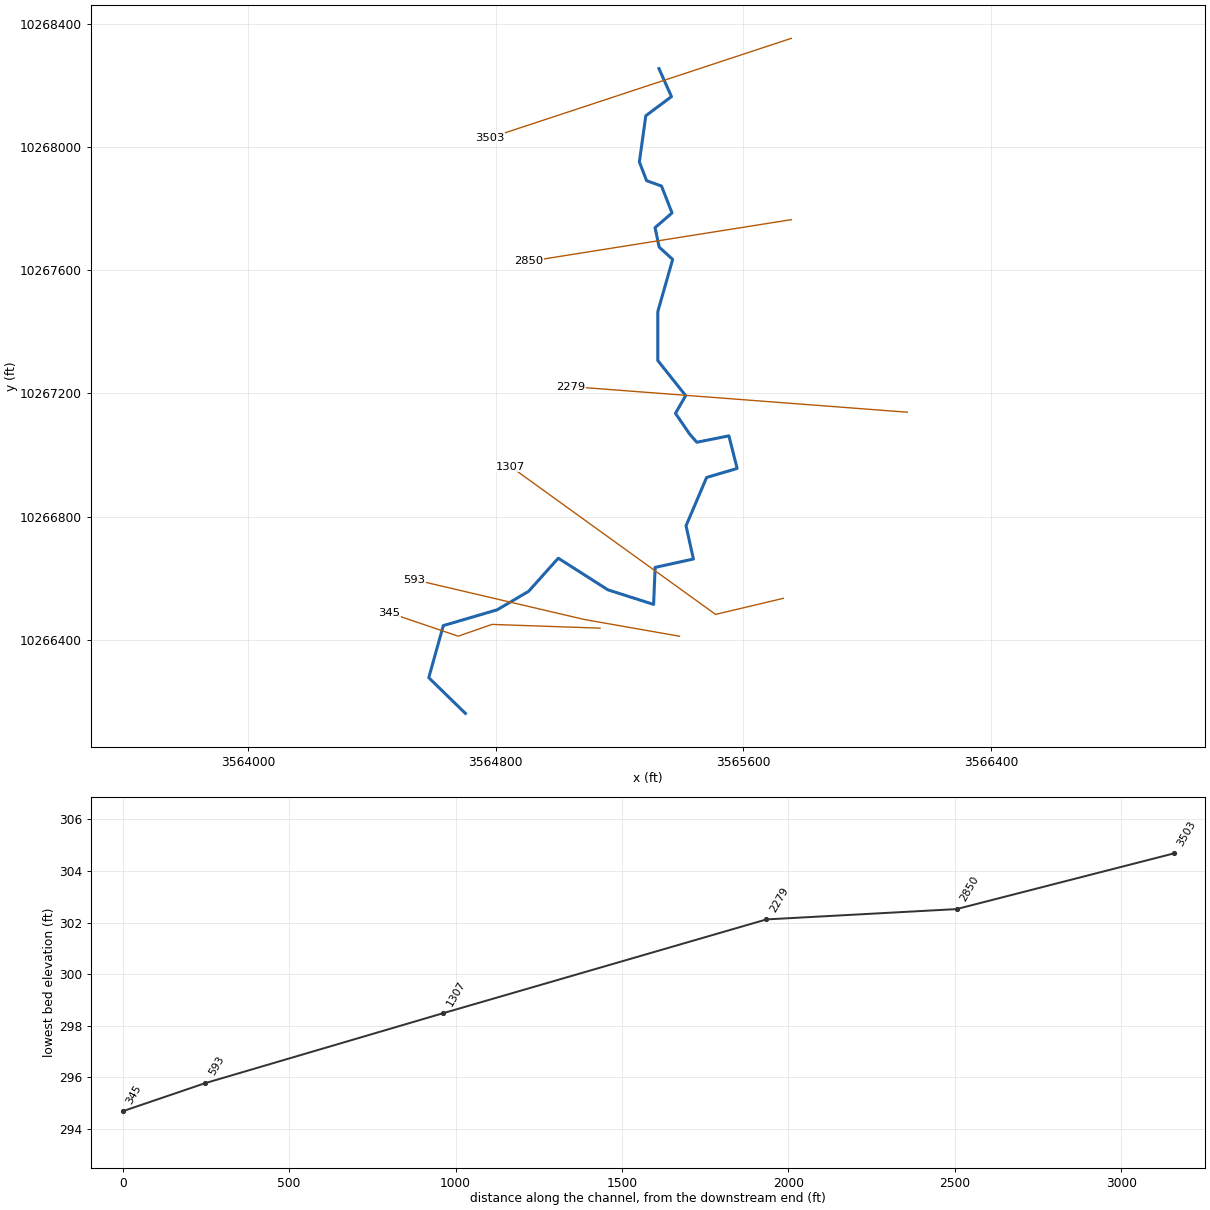
--- MATHIS CREEK TRIB 6 1.prj (project) ---

Proj Title=MATHIS CREEK TRIB 6 1 Base Level Engineering
Current Plan=p01
Default Exp/Contr=0.3,0.1
English Units
Geom File=g01
Flow File=f01
Plan File=p01
BEGIN DESCRIPTION:
MATHIS CREEK TRIB 6 1
END DESCRIPTION:

--- MATHIS CREEK TRIB 6 1.p01 (plan) ---

Plan Title=Multiple Run
Short Identifier=Multiple
Geom File=g01
Flow File=f01
Subcritical Flow
K Sum by GR= 0
Std Step Tol= 0.01
Critical Tol= 0.01
Num of Std Step Trials= 20
Max Error Tol= 0.3
Flow Tol Ratio= 0.001
Split Flow NTrial= 30
Split Flow Tol= 0.02
Split Flow Ratio= 0.02
Log Output Level= 0
Friction Slope Method= 1
Unsteady Friction Slope Method= 2
Unsteady Bridges Friction Slope Method= 1
Parabolic Critical Depth
Global Vel Dist=  1 , 1 , 1
Global Log Level= 0
CheckData=True
Encroach Param= -1, 0, 0, 0
BEGIN DESCRIPTION:
Multiple Run
END DESCRIPTION:

--- MATHIS CREEK TRIB 6 1.f01 (steady flow) ---

Flow Title=Multiple
Number of Profiles=7
Profile Names=10-year,25-year,50-year,1pct_min,100-year,1pct_plu,500-year
River Rch & RM= MATHIS CREEK TRI,Reach-1,3503
     292     376     441     380     514     695     699
Boundary for River Rch & Prof#=MATHIS CREEK TRI,Reach-1,1
Up Type=0
Dn Type=3
Dn Slope=0.005
Boundary for River Rch & Prof#=MATHIS CREEK TRI,Reach-1,2
Up Type=0
Dn Type=3
Dn Slope=0.005
Boundary for River Rch & Prof#=MATHIS CREEK TRI,Reach-1,3
Up Type=0
Dn Type=3
Dn Slope=0.005
Boundary for River Rch & Prof#=MATHIS CREEK TRI,Reach-1,4
Up Type=0
Dn Type=3
Dn Slope=0.005
Boundary for River Rch & Prof#=MATHIS CREEK TRI,Reach-1,5
Up Type=0
Dn Type=3
Dn Slope=0.005
Boundary for River Rch & Prof#=MATHIS CREEK TRI,Reach-1,6
Up Type=0
Dn Type=3
Dn Slope=0.005
Boundary for River Rch & Prof#=MATHIS CREEK TRI,Reach-1,7
Up Type=0
Dn Type=3
Dn Slope=0.005

--- MATHIS CREEK TRIB 6 1.g01 (geometry) ---

Geom Title=Existing Conditions

River Reach=MATHIS CREEK TRI,Reach-1
Reach XY= 30
      3565327.49     10268254.40      3565367.99     10268163.50
      3565285.01     10268101.35      3565264.27     10267951.38
      3565287.66     10267890.64      3565335.70     10267873.22
      3565369.80     10267785.91      3565314.87     10267738.15
      3565328.20     10267675.05      3565371.81     10267635.03
      3565323.84     10267465.82      3565323.72     10267306.95
      3565413.83     10267193.01      3565380.84     10267135.38
      3565426.75     10267068.17      3565449.94     10267041.63
      3565553.41     10267062.46      3565580.14     10266956.59
      3565481.54     10266927.39      3565415.03     10266770.60
      3565438.87     10266662.65      3565315.16     10266635.49
      3565310.23     10266515.31      3565162.52     10266562.64
      3565002.20     10266665.34      3564906.19     10266557.60
      3564804.58     10266497.70      3564630.71     10266446.50
      3564583.79     10266277.54      3564702.11     10266161.64

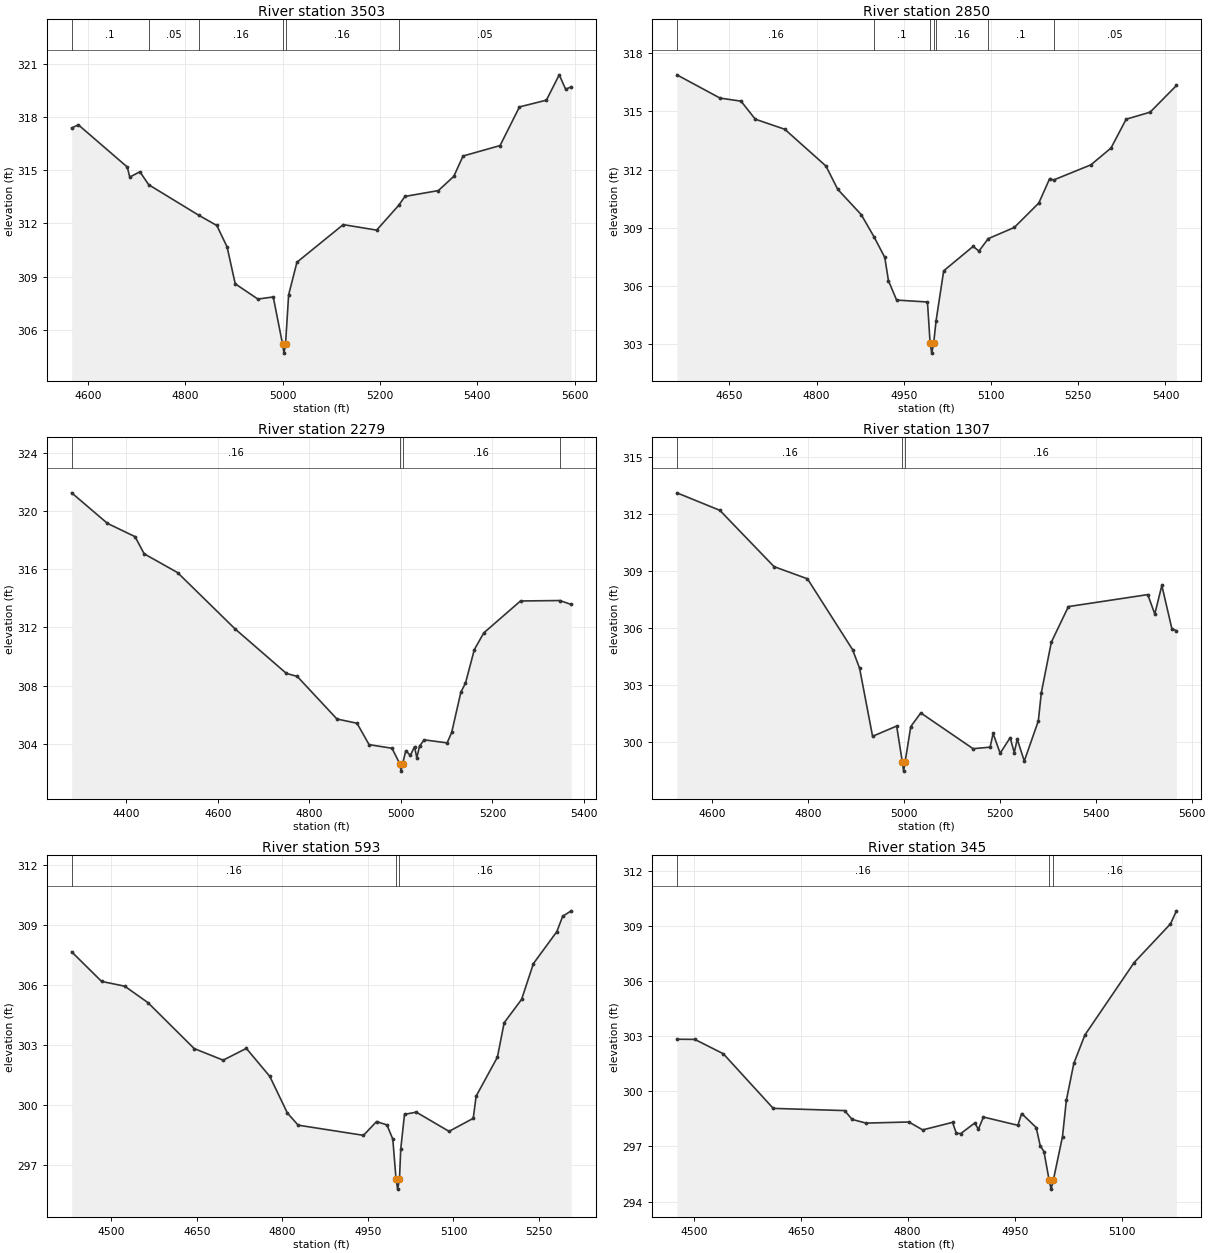
Type RM Length L Ch R = 1,3503,653,653,653
BEGIN DESCRIPTION:
UNT05216 IN WICK 8.0
END DESCRIPTION:
XS GIS Cut Line= 2
      3565755.18     10268352.66      3564781.22     10268029.75
#Sta/Elev= 30
  4566.6  317.38  4580.4  317.56  4680.8  315.18  4686.0  314.61  4706.8  314.91
  4724.9  314.18  4827.6  312.46  4864.8  311.88  4885.9  310.67  4902.6  308.59
  4949.1  307.73  4980.7  307.85  4999.9  305.18  5002.7  304.68  5005.9  305.18
  5012.3  307.97  5029.4  309.81  5124.4  311.93  5193.1  311.62  5238.4  313.02
  5251.2  313.52  5319.8  313.85  5351.5  314.65  5370.5  315.80  5446.6  316.39
  5486.4  318.57  5541.7  318.95  5568.1  320.38  5581.2  319.57  5592.7  319.70
#Mann=6,-1,0
  4566.6     0.1       0  4724.9    0.05       0  4827.6    0.16       0
  4999.9    0.07       0  5005.9    0.16       0  5238.4    0.05       0
Bank Sta=4999.9,5005.9
Exp/Cntr=0.3,0.1

Type RM Length L Ch R = 1,2850,571,571,571
BEGIN DESCRIPTION:
UNT05216 IN WICK 7.0
END DESCRIPTION:
XS GIS Cut Line= 2
      3565755.27     10267764.14      3564906.69     10267628.79
#Sta/Elev= 30
  4559.6  316.89  4633.7  315.69  4669.9  315.53  4694.4  314.60  4745.1  314.08
  4816.0  312.18  4836.2  310.98  4876.7  309.67  4898.8  308.52  4917.2  307.46
  4923.5  306.26  4937.5  305.26  4990.6  305.16  4995.2  303.02  4998.0  302.52
  5001.2  303.02  5005.4  304.19  5018.5  306.77  5069.1  308.03  5079.2  307.79
  5095.1  308.43  5140.0  309.01  5182.1  310.27  5200.8  311.53  5207.5  311.46
  5271.6  312.24  5306.3  313.11  5332.4  314.60  5373.5  314.96  5418.9  316.34
#Mann=7,-1,0
  4559.6    0.16       0  4898.8     0.1       0  4995.2    0.07       0
  5001.2     0.1       0  5005.4    0.16       0  5095.1     0.1       0
  5207.5    0.05       0
Bank Sta=4995.2,5001.2
Exp/Cntr=0.3,0.1

Type RM Length L Ch R = 1,2279,972,972,972
BEGIN DESCRIPTION:
UNT05216 IN WICK 6.0
END DESCRIPTION:
XS GIS Cut Line= 2
      3566130.18     10267139.14      3565041.67     10267222.47
#Sta/Elev= 30
  4280.5  321.24  4358.8  319.14  4419.0  318.23  4439.0  317.05  4512.0  315.76
  4637.7  311.89  4749.9  308.83  4773.4  308.63  4860.3  305.70  4904.1  305.41
  4930.5  303.94  4980.6  303.69  4997.7  302.62  5000.4  302.12  5003.7  302.62
  5010.7  303.52  5020.7  303.20  5029.8  303.80  5034.8  303.04  5040.8  303.84
  5050.8  304.27  5101.0  304.06  5111.0  304.78  5131.1  307.55  5141.1  308.16
  5160.5  310.47  5181.2  311.62  5261.4  313.81  5347.4  313.84  5372.2  313.57
#Mann=4,-1,0
  4280.5    0.16       0  4997.7    0.07       0  5003.7    0.16       0
  5347.4    0.05       0
Bank Sta=4997.7,5003.7
Exp/Cntr=0.3,0.1

Type RM Length L Ch R = 1,1307,714,714,714
BEGIN DESCRIPTION:
UNT05216 IN WICK 4.0
END DESCRIPTION:
XS GIS Cut Line= 3
      3565729.19     10266534.97      3565510.43     10266482.89
      3564849.01     10266962.02
#Sta/Elev= 30
  4526.8  313.11  4616.3  312.19  4729.4  309.23  4799.0  308.59  4893.0  304.87
  4907.7  303.89  4934.8  300.31  4985.0  300.85  4996.7  298.98  4999.5  298.48
  5002.7  298.98  5014.4  300.82  5035.3  301.54  5144.3  299.66  5179.9  299.74
  5186.1  300.46  5200.8  299.42  5221.7  300.24  5230.2  299.45  5236.4  300.16
  5251.1  299.01  5280.4  301.12  5286.6  302.60  5307.5  305.26  5343.1  307.13
  5508.6  307.76  5523.2  306.74  5537.9  308.24  5558.8  305.97  5568.4  305.86
#Mann=3,-1,0
  4526.8    0.16       0  4996.7    0.07       0  5002.7    0.16       0
Bank Sta=4996.7,5002.7
Exp/Cntr=0.3,0.1

Type RM Length L Ch R = 1,593,248,248,248
BEGIN DESCRIPTION:
Mapping XS 134750d1
END DESCRIPTION:
XS GIS Cut Line= 3
      3565393.77     10266412.05      3565086.65     10266466.31
      3564537.60     10266595.44
#Sta/Elev= 30
  4430.5  307.64  4483.0  306.16  4523.6  305.92  4564.2  305.10  4645.4  302.80
  4696.2  302.22  4736.8  302.81  4777.9  301.41  4808.7  299.58  4827.6  298.97
  4942.2  298.46  4965.1  299.15  4983.3  298.98  4993.6  298.27  4999.3  296.27
  5002.1  295.77  5005.3  296.27  5007.5  297.77  5014.1  299.51  5034.7  299.62
  5092.2  298.66  5134.6  299.31  5139.7  300.42  5177.0  302.37  5188.8  304.09
  5219.4  305.26  5240.1  307.05  5281.2  308.65  5291.5  309.42  5306.4  309.69
#Mann=3,-1,0
  4430.5    0.16       0  4999.3    0.07       0  5005.3    0.16       0
Bank Sta=4999.3,5005.3
Exp/Cntr=0.3,0.1

Type RM Length L Ch R = 1,345,0,0,0
BEGIN DESCRIPTION:
Mapping XS 134750d1.a
END DESCRIPTION:
XS GIS Cut Line= 4
      3565137.14     10266438.25      3564788.20     10266450.40
      3564678.82     10266412.20      3564455.94     10266488.23
#Sta/Elev= 30
  4476.4  302.83  4501.5  302.82  4541.5  302.04  4611.5  299.07  4711.6  298.95
  4722.1  298.47  4741.6  298.27  4801.6  298.33  4821.1  297.90  4862.9  298.31
  4868.2  297.72  4874.4  297.70  4893.9  298.27  4899.2  297.94  4906.2  298.60
  4954.5  298.15  4959.8  298.79  4980.2  298.03  4985.8  297.05  4991.1  296.72
  4998.3  295.18  5001.1  294.68  5004.3  295.18  5017.1  297.54  5022.5  299.51
  5033.0  301.52  5048.5  303.06  5117.6  307.00  5168.5  309.10  5176.9  309.81
#Mann=3,-1,0
  4476.4    0.16       0  4998.3    0.07       0  5004.3    0.16       0
Bank Sta=4998.3,5004.3
Exp/Cntr=0.3,0.1

Chan Stop Cuts=-1