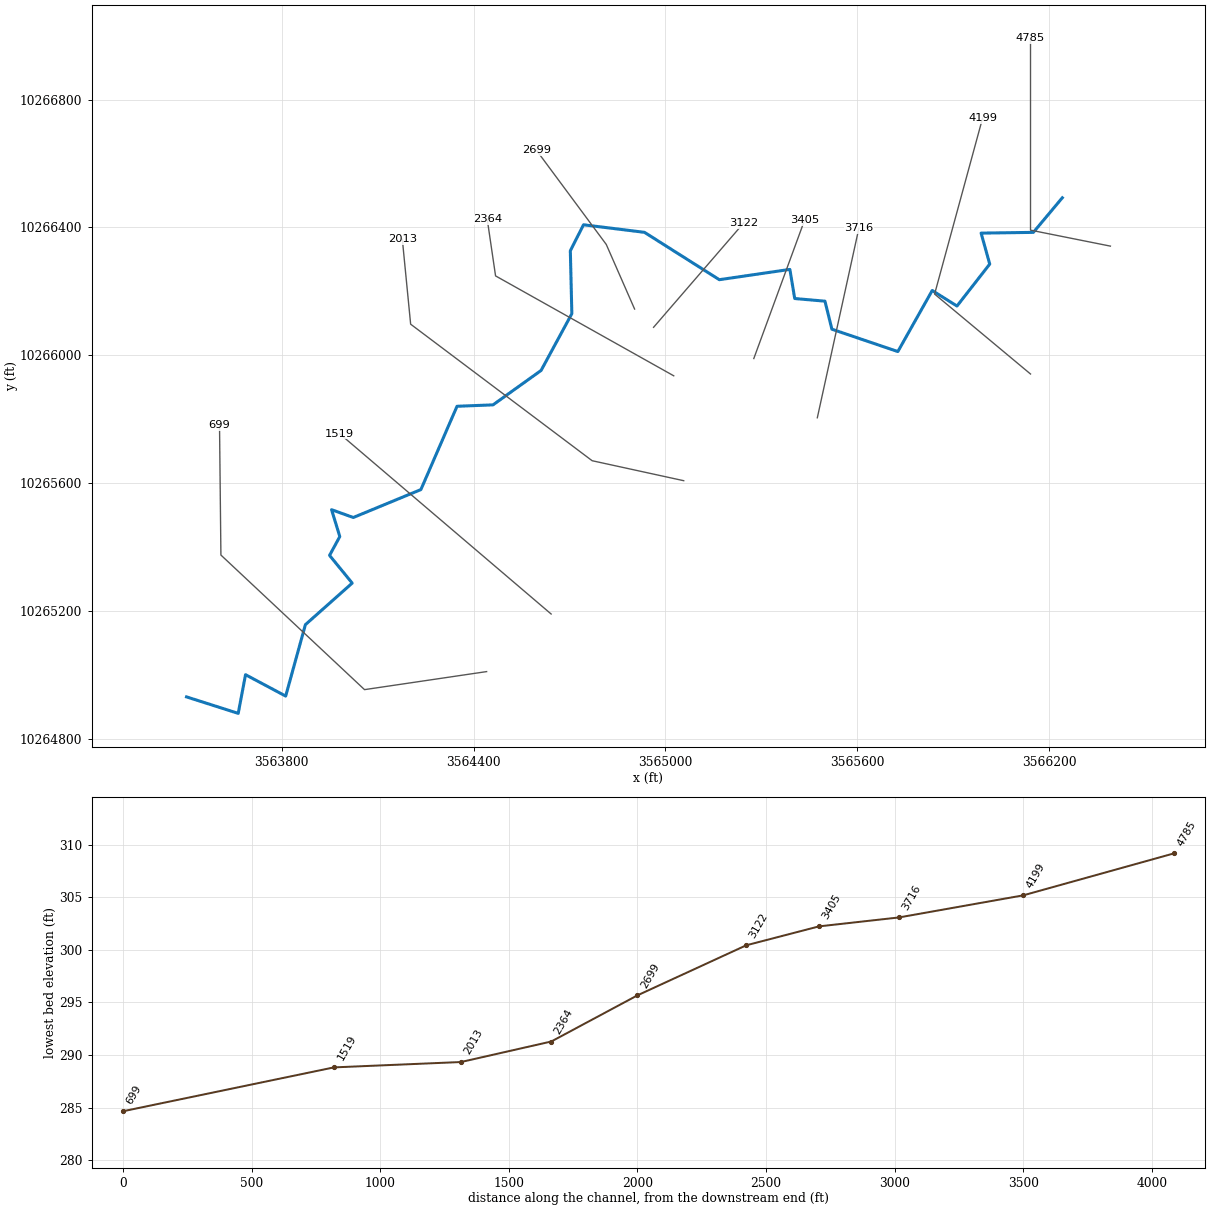
--- MATHISCREEKTRIB6.prj (project) ---

Proj Title=MATHIS CREEK TRIB 6
Current Plan=p01
Default Exp/Contr=0.3,0.1
English Units
Geom File=g01
Flow File=f01
Plan File=p01
Y Axis Title=Elevation
X Axis Title(PF)=Main Channel Distance
X Axis Title(XS)=Station
BEGIN DESCRIPTION:
UNT05216 IN WICK
END DESCRIPTION:
DSS Export Rating Curves= 0
DSS Export Rating Curve Sorted= 0
DSS Export Volume Flow Curves= 0
DXF OffsetX= 0
DXF OffsetY= 0
DXF ScaleX= 1
DXF ScaleY= 10

--- MATHISCREEKTRIB6.p01 (plan) ---

Plan Title=Multiple Run
Short Identifier=Multiple
Geom File=g01
Flow File=f01
Subcritical Flow
K Sum by GR= 0
Std Step Tol= 0.01
Critical Tol= 0.01
Num of Std Step Trials= 20
Max Error Tol= 0.3
Flow Tol Ratio= 0.001
Split Flow NTrial= 30
Split Flow Tol= 0.02
Split Flow Ratio= 0.02
Log Output Level= 0
Friction Slope Method= 1
Unsteady Friction Slope Method= 2
Unsteady Bridges Friction Slope Method= 1
Parabolic Critical Depth
Global Vel Dist=  1 , 1 , 1
Global Log Level= 0
CheckData=True
Encroach Param= -1, 0, 0, 0
BEGIN DESCRIPTION:
Multiple Run
END DESCRIPTION:

--- MATHISCREEKTRIB6.f01 (steady flow) ---

Flow Title=Multiple
Program Version=4.10
Number of Profiles= 7
Profile Names=10-year,25-year,50-year,1pct_min,100-year,1pct_plu,500-year
River Rch & RM=MATHISCRTRIB6,Reach-1         ,4785
     144     177     201     169     228     309     292
River Rch & RM=MATHISCRTRIB6,Reach-1         ,2699
     409     538     640     559     756    1023    1057
River Rch & RM=MATHISCRTRIB6,Reach-1         ,2364
     409     538     640     559     756    1023    1057
Boundary for River Rch & Prof#=MATHISCRTRIB6,Reach-1         , 1
Up Type= 0
Dn Type= 3
Dn Slope=0.005
Boundary for River Rch & Prof#=MATHISCRTRIB6,Reach-1         , 2
Up Type= 0
Dn Type= 3
Dn Slope=0.005
Boundary for River Rch & Prof#=MATHISCRTRIB6,Reach-1         , 3
Up Type= 0
Dn Type= 3
Dn Slope=0.005
Boundary for River Rch & Prof#=MATHISCRTRIB6,Reach-1         , 4
Up Type= 0
Dn Type= 3
Dn Slope=0.005
Boundary for River Rch & Prof#=MATHISCRTRIB6,Reach-1         , 5
Up Type= 0
Dn Type= 3
Dn Slope=0.005
Boundary for River Rch & Prof#=MATHISCRTRIB6,Reach-1         , 6
Up Type= 0
Dn Type= 3
Dn Slope=0.005
Boundary for River Rch & Prof#=MATHISCRTRIB6,Reach-1         , 7
Up Type= 0
Dn Type= 3
Dn Slope=0.005
DSS Import GetInterval= 0
DSS Import GetPeak= 0
DSS Import FillOption= 0

--- MATHISCREEKTRIB6.g01 (geometry) ---

Geom Title=Existing Conditions
Program Version=4.10

River Reach=MATHISCRTRIB6   ,Reach-1
Reach XY= 30
      3566241.62     10266492.96      3566151.01     10266384.68
      3565987.54     10266382.34      3566014.57      10266285.5
      3565912.12     10266154.25      3565834.65     10266202.86
      3565727.14     10266011.83      3565520.84     10266081.77
      3565499.14     10266169.44      3565404.52     10266177.73
      3565389.42     10266268.88       3565168.7      10266236.6
      3564934.63     10266384.78      3564743.87     10266408.41
      3564702.64     10266327.22      3564707.36     10266130.29
      3564611.09     10265952.64      3564460.79     10265845.11
      3564348.18     10265840.69      3564235.16     10265580.01
       3564023.7     10265492.78      3563955.73     10265517.25
      3563981.51     10265433.14      3563949.47     10265374.24
      3564020.32     10265287.57      3563873.96     10265157.62
      3563812.24     10264934.18      3563686.63     10265001.03
      3563663.77     10264880.06      3563502.11     10264931.64

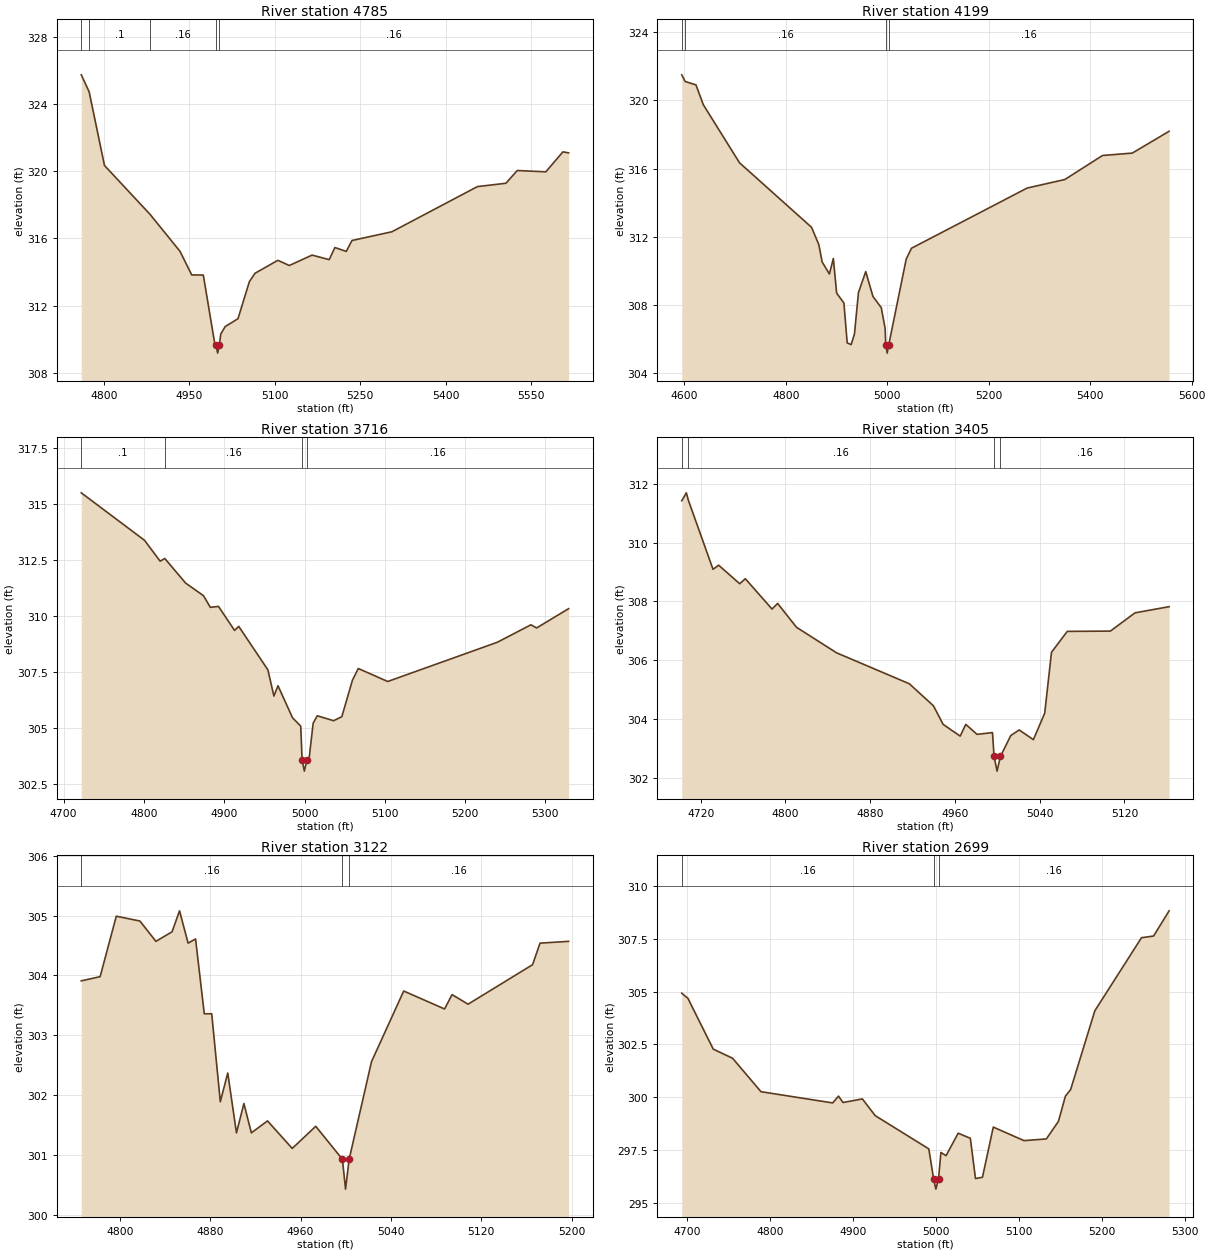
Type RM Length L Ch R = 1 ,4785    ,586,586,586
BEGIN DESCRIPTION:
UNT05217 IN WICK 4.0
END DESCRIPTION:
XS GIS Cut Line= 3
      3566392.06     10266341.65      3566142.11     10266391.64
      3566142.11     10266991.63
#Sta/Elev= 30
  4760.6  325.75  4774.4  324.74  4801.3  320.35  4881.2  317.44  4933.9  315.23
  4954.3  313.83  4974.7  313.82  4995.1  309.67    4997  309.67  4999.8  309.17
    5003  309.67  5005.3  310.31    5013  310.75  5035.5  311.22  5055.5  313.43
  5065.5  313.93  5105.5   314.7  5125.5  314.39  5165.5  315.01  5195.5  314.74
  5205.5  315.46  5225.5  315.23  5235.5  315.88  5305.5   316.4  5455.5  319.09
  5505.5  319.29  5525.5  320.05  5575.5  319.97  5605.5  321.16  5615.5   321.1
#Mann= 5 ,-1 , 0
  4760.6     .05       0  4774.4      .1       0  4881.2     .16       0
    4997     .07       0    5003     .16       0
Bank Sta=4997,5003
XS Rating Curve= 0 ,0
Exp/Cntr=0.3,0.1

Type RM Length L Ch R = 1 ,4199    ,483,483,483
BEGIN DESCRIPTION:
UNT05217 IN WICK 3.0
END DESCRIPTION:
XS GIS Cut Line= 3
      3566142.14     10265941.61      3565842.11     10266191.64
      3565992.09     10266741.59
#Sta/Elev= 30
  4594.9   321.5  4601.6  321.11  4622.9  320.91  4637.3  319.75  4708.8  316.34
  4850.7  312.56  4865.1  311.54  4871.6  310.53  4885.9  309.82  4893.7  310.73
  4900.2   308.7  4914.5  308.12    4921  305.78  4928.8  305.68  4935.3   306.3
  4943.2  308.73  4957.5  309.96  4971.8   308.5  4988.1  307.85  4995.8  306.63
    4997  305.68  4999.8  305.18    5003  305.68  5037.3  310.69  5047.7  311.33
  5275.7  314.86    5350  315.36  5424.3  316.77    5483  316.91  5555.5  318.19
#Mann= 4 ,-1 , 0
  4594.9      .1       0  4601.6     .16       0    4997     .07       0
    5003     .16       0
Bank Sta=4997,5003
XS Rating Curve= 0 ,0
Exp/Cntr=0.3,0.1

Type RM Length L Ch R = 1 ,3716    ,311,311,311
BEGIN DESCRIPTION:
UNT05217 IN WICK 2.0
END DESCRIPTION:
XS GIS Cut Line= 2
      3565475.21     10265804.68      3565605.21     10266397.49
#Sta/Elev= 30
    4722   315.5  4800.8  313.38  4820.2  312.45    4826  312.57    4852  311.47
  4874.2  310.91  4882.7  310.39  4892.9  310.43  4912.9  309.36  4918.1  309.54
  4954.4   307.6  4961.9  306.43    4967  306.89  4985.1  305.46  4995.3  305.09
    4997  303.58  4999.8  303.08    5003  303.58  5005.5  303.58  5010.8  305.22
  5015.9  305.55  5036.3  305.33  5046.5  305.51  5059.7  307.14    5067  307.66
  5103.6  307.08  5240.1  308.83    5282  309.61  5289.1  309.47  5328.9  310.33
#Mann= 4 ,-1 , 0
    4722      .1       0    4826     .16       0    4997     .07       0
    5003     .16       0
Bank Sta=4997,5003
XS Rating Curve= 0 ,0
Exp/Cntr=0.3,0.1

Type RM Length L Ch R = 1 ,3405    ,283,283,283
BEGIN DESCRIPTION:
Mapping XS 908326f1
END DESCRIPTION:
XS GIS Cut Line= 2
      3565276.56     10265990.01      3565434.98     10266421.87
#Sta/Elev= 30
  4702.2  311.42  4706.5  311.69  4708.5  311.43  4731.7  309.09    4737  309.23
  4756.9   308.6  4762.2  308.77  4787.4  307.74  4792.7  307.93  4810.5  307.12
  4848.4  306.25    4917   305.2  4939.8  304.45  4948.9  303.82    4965  303.42
  4970.3  303.82  4980.9  303.48  4995.5  303.54    4997  302.73  4999.8  302.23
    5003  302.73  5012.8  303.44  5020.7  303.63  5034.1   303.3  5044.8   304.2
  5051.2  306.27  5066.1  306.98  5106.8  306.99    5130  307.61  5162.2  307.82
#Mann= 4 ,-1 , 0
  4702.2      .1       0  4708.5     .16       0    4997     .07       0
    5003     .16       0
Bank Sta=4997,5003
XS Rating Curve= 0 ,0
Exp/Cntr=0.3,0.1

Type RM Length L Ch R = 1 ,3122    ,423,423,423
BEGIN DESCRIPTION:
Mapping XS 49a8d2fa
END DESCRIPTION:
XS GIS Cut Line= 2
      3564962.99     10266087.66      3565245.05      10266414.2
#Sta/Elev= 30
  4765.8  303.91  4782.5  303.98  4796.8  304.99  4817.7  304.91  4831.9  304.57
  4846.2  304.73  4852.8  305.08  4860.4  304.54    4867  304.61  4874.7  303.36
  4881.3  303.36  4888.9  301.89  4895.5  302.37  4903.2  301.37  4909.8  301.86
  4916.4  301.37  4930.7  301.57  4952.6  301.11  4973.4  301.48    4997  300.93
  4999.8  300.43    5003  300.93  5022.8  302.56  5051.3  303.74  5087.5  303.44
  5094.1  303.68  5108.3  303.52  5165.4  304.18    5172  304.54  5197.3  304.57
#Mann= 3 ,-1 , 0
  4765.8     .16       0    4997     .07       0    5003     .16       0
Bank Sta=4997,5003
XS Rating Curve= 0 ,0
Exp/Cntr=0.3,0.1

Type RM Length L Ch R = 1 ,2699    ,335,335,335
BEGIN DESCRIPTION:
UNT05217 IN WICK 1.0
END DESCRIPTION:
XS GIS Cut Line= 3
      3564903.65     10266144.84      3564815.04      10266346.9
      3564596.29     10266642.03
#Sta/Elev= 30
  4693.2  304.92  4700.6  304.68  4731.2  302.28  4754.5  301.85  4788.8  300.27
  4875.3  299.74  4882.3  300.06  4887.8  299.76  4911.1  299.93  4926.6  299.14
  4991.3  297.57    4997  296.17  4999.8  295.67    5003  296.17  5005.9   297.4
  5012.1  297.25  5026.7  298.31  5041.4  298.07  5047.6  296.17    5056  296.23
  5069.1   298.6  5106.1  297.96  5133.1  298.04  5147.7  298.87  5156.1  300.06
  5162.4  300.37  5191.6  304.09  5247.9  307.54  5262.5  307.62  5281.2  308.81
#Mann= 3 ,-1 , 0
  4693.2     .16       0    4997     .07       0    5003     .16       0
Bank Sta=4997,5003
XS Rating Curve= 0 ,0
Exp/Cntr=0.3,0.1

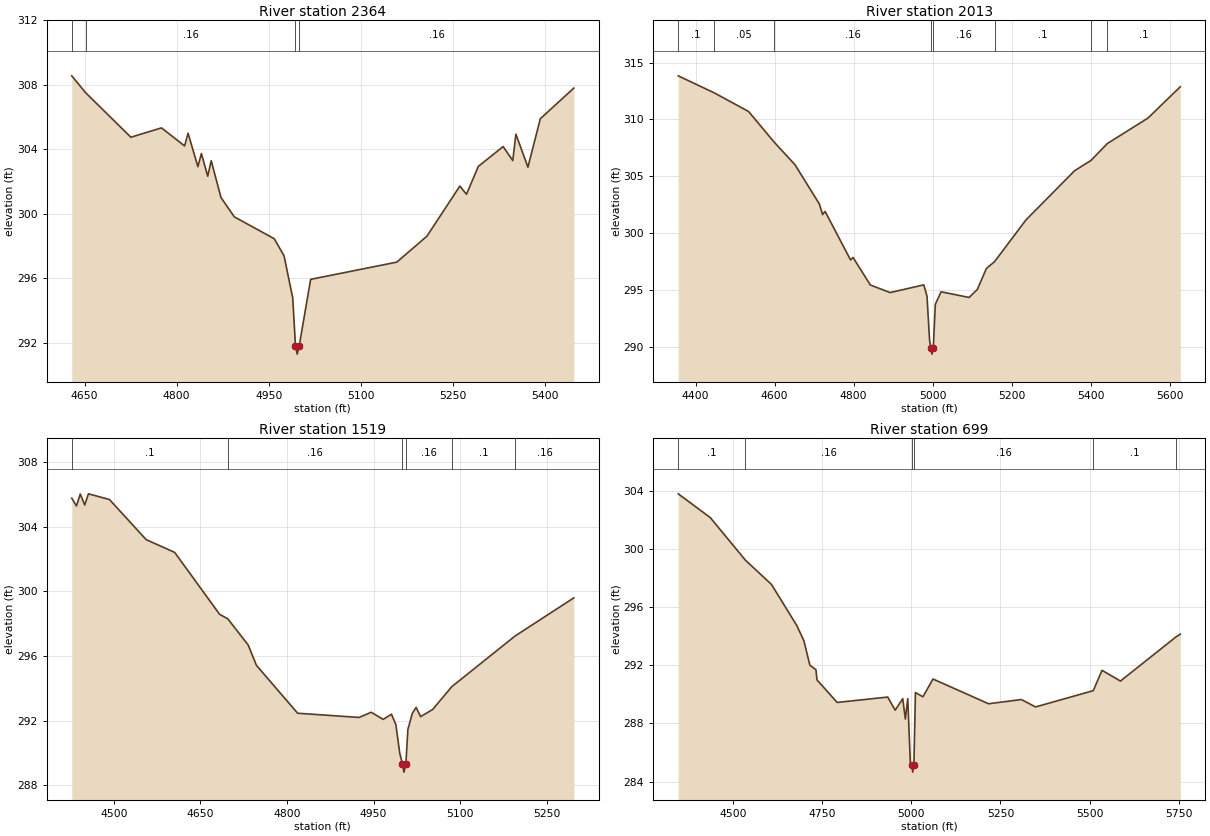
Type RM Length L Ch R = 1 ,2364    ,351,351,351
BEGIN DESCRIPTION:
UNT05216 IN WICK 3.0
END DESCRIPTION:
XS GIS Cut Line= 3
       3565026.1     10265935.99      3564468.77     10266248.51
      3564442.72     10266425.63
#Sta/Elev= 30
  4629.2  308.55  4651.6  307.51  4725.5  304.74  4775.4  305.32    4813   304.2
  4818.7  304.99  4834.7  302.91  4840.4  303.73  4850.7  302.32  4856.4  303.28
  4872.3     301    4894   299.8  4959.1  298.44  4975.1  297.38  4989.2  294.76
  4993.7  291.78  4996.5  291.28  4999.7  291.78  5018.4  295.92  5158.8  296.99
  5207.9   298.6  5261.5  301.71  5272.3   301.2  5291.6  302.93    5332  304.16
  5347.7  303.29  5352.8  304.93  5372.4  302.88  5392.6  305.89  5447.2  307.79
#Mann= 4 ,-1 , 0
  4629.2      .1       0  4651.6     .16       0  4993.7     .07       0
  4999.7     .16       0
Bank Sta=4993.7,4999.7
XS Rating Curve= 0 ,0
Exp/Cntr=0.3,0.1

Type RM Length L Ch R = 1 ,2013    ,494,494,494
BEGIN DESCRIPTION:
UNT05216 IN WICK 2.0
END DESCRIPTION:
XS GIS Cut Line= 4
      3565057.31     10265607.89      3564770.85     10265670.39
      3564203.14     10266097.47       3564177.1     10266363.08
#Sta/Elev= 30
  4356.3  313.84  4447.4  312.34  4534.3   310.7  4598.8  308.01  4651.8  306.01
  4713.3  302.56  4721.6  301.62  4727.9   301.9  4792.4  297.62  4798.7  297.84
  4842.4  295.42  4892.4  294.75  4977.7  295.43  4985.8  294.44  4992.3  290.57
  4995.6  289.83  4998.3  289.33  5001.6  289.83  5006.9  293.72  5021.5  294.82
  5092.3  294.32  5113.1  295.02    5136  296.87  5156.7  297.47    5236  301.14
  5359.2  305.48  5400.8  306.39  5441.9  307.87    5545  310.12  5626.8  312.88
#Mann= 8 ,-1 , 0
  4356.3      .1       0  4447.4     .05       0  4598.8     .16       0
  4995.6     .07       0  5001.6     .16       0  5156.7      .1       0
  5400.8     .16       0  5441.9      .1       0
Bank Sta=4995.6,5001.6
XS Rating Curve= 0 ,0
Exp/Cntr=0.3,0.1

Type RM Length L Ch R = 1 ,1519    ,820,820,820
BEGIN DESCRIPTION:
Mapping XS 921ca955
END DESCRIPTION:
XS GIS Cut Line= 2
      3564642.62     10265190.86      3563980.69     10265755.12
#Sta/Elev= 30
  4427.2  305.75  4435.3  305.27  4441.9  306.01  4449.6  305.33  4456.1  306.02
  4492.4  305.67  4556.1  303.19  4605.5   302.4  4683.4  298.57  4697.4   298.3
  4732.8  296.68  4747.1  295.42  4818.5  292.46    4925   292.2  4945.9  292.52
  4966.7  292.08    4981   292.4  4988.7  291.76  4995.3  290.01    5000  289.32
  5002.7  288.82    5006  289.32  5009.5  291.46  5017.2  292.45  5023.8  292.82
  5031.5  292.25  5052.4  292.69  5085.5   294.1  5195.1  297.23    5297  299.59
#Mann= 6 ,-1 , 0
  4427.2      .1       0  4697.4     .16       0    5000     .07       0
    5006     .16       0  5085.5      .1       0  5195.1     .16       0
Bank Sta=5000,5006
XS Rating Curve= 0 ,0
Exp/Cntr=0.3,0.1

Type RM Length L Ch R = 1 ,699     ,0,0,0
BEGIN DESCRIPTION:
UNT05216 IN WICK 1.0
END DESCRIPTION:
XS GIS Cut Line= 4
      3564440.82     10265010.75      3564058.83     10264954.32
      3563609.62     10265375.33      3563605.28     10265781.11
#Sta/Elev= 30
  4346.6  303.78  4436.3  302.15  4534.9  299.22  4608.1  297.55  4678.9  294.73
  4699.1  293.67  4715.6     292  4732.7  291.69  4735.6  290.99  4792.3  289.44
  4933.8  289.81  4954.9  288.91    4976   289.7  4983.3   288.3  4990.1   289.7
  4997.4  285.24  5001.3  285.15    5004  284.65  5007.3  285.15  5011.6  290.12
  5032.6  289.83  5060.9  291.05  5216.7  289.35  5308.6  289.64  5348.4  289.13
  5510.2  290.25  5534.7  291.65  5586.4  290.91  5743.4  293.97  5754.2  294.13
#Mann= 6 ,-1 , 0
  4346.6      .1       0  4534.9     .16       0  5001.3     .07       0
  5007.3     .16       0  5510.2      .1       0  5743.4     .12       0
Bank Sta=5001.3,5007.3
XS Rating Curve= 0 ,0
Exp/Cntr=0.3,0.1

Chan Stop Cuts=-1
Use User Specified Reach Order=0
Composite Channel Slope=5