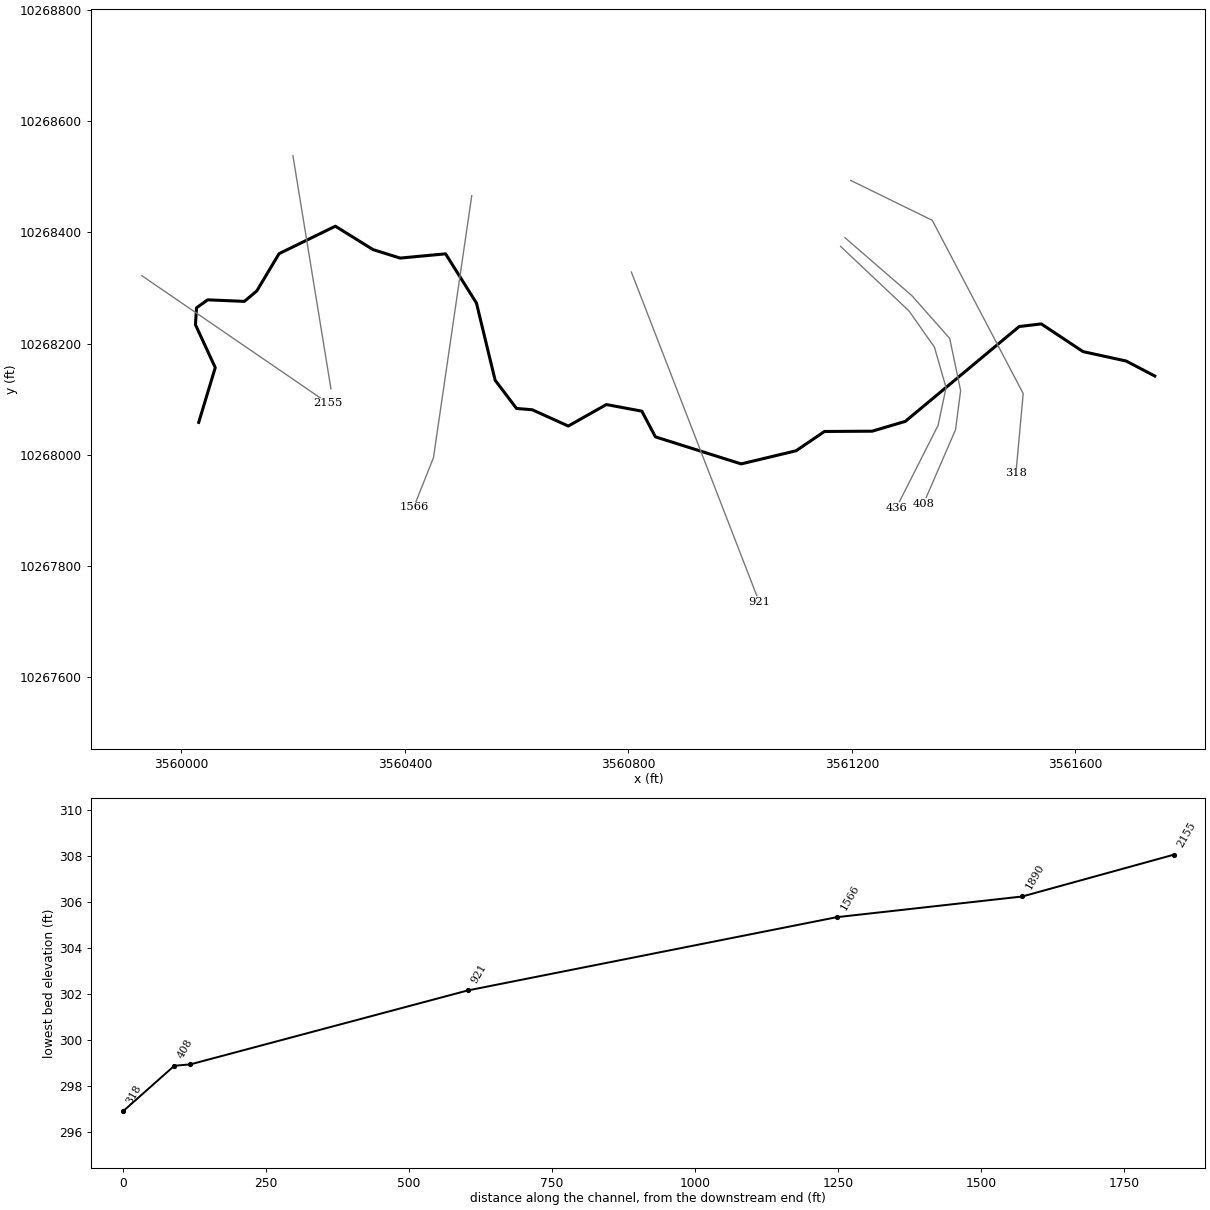
--- MATHISCREEKTRIB7.prj (project) ---

Proj Title=MATHIS CREEK TRIB 7
Current Plan=p01
Default Exp/Contr=0.3,0.1
English Units
Geom File=g01
Flow File=f01
Plan File=p01
Y Axis Title=Elevation
X Axis Title(PF)=Main Channel Distance
X Axis Title(XS)=Station
BEGIN DESCRIPTION:
UNT05214 IN WICK
END DESCRIPTION:
DSS Export Rating Curves= 0
DSS Export Rating Curve Sorted= 0
DSS Export Volume Flow Curves= 0
DXF Filename=UNT05214 IN WICK.
DXF OffsetX= 0
DXF OffsetY= 0
DXF ScaleX= 1
DXF ScaleY= 10

--- MATHISCREEKTRIB7.p01 (plan) ---

Plan Title=Multiple Run
Short Identifier=Multiple
Geom File=g01
Flow File=f01
Subcritical Flow
K Sum by GR= 0
Std Step Tol= 0.01
Critical Tol= 0.01
Num of Std Step Trials= 20
Max Error Tol= 0.3
Flow Tol Ratio= 0.001
Split Flow NTrial= 30
Split Flow Tol= 0.02
Split Flow Ratio= 0.02
Log Output Level= 0
Friction Slope Method= 1
Unsteady Friction Slope Method= 2
Unsteady Bridges Friction Slope Method= 1
Parabolic Critical Depth
Global Vel Dist=  1 , 1 , 1
Global Log Level= 0
CheckData=True
Encroach Param= -1, 0, 0, 0
BEGIN DESCRIPTION:
Multiple Run
END DESCRIPTION:

--- MATHISCREEKTRIB7.f01 (steady flow) ---

Flow Title=Multiple
Program Version=4.10
Number of Profiles= 7
Profile Names=10-year,25-year,50-year,1pct_min,100-year,1pct_plu,500-year
River Rch & RM=UNT05214 IN WICK,Reach-1         ,2155
     248     318     373     322     435     588     591
River Rch & RM=MATHISCRTRB7,Reach-1         ,2155
     248     318     373     322     435     588     591
Boundary for River Rch & Prof#=MATHISCRTRB7,Reach-1         , 1
Up Type= 0
Dn Type= 3
Dn Slope=0.005
Boundary for River Rch & Prof#=MATHISCRTRB7,Reach-1         , 2
Up Type= 0
Dn Type= 3
Dn Slope=0.005
Boundary for River Rch & Prof#=MATHISCRTRB7,Reach-1         , 3
Up Type= 0
Dn Type= 3
Dn Slope=0.005
Boundary for River Rch & Prof#=MATHISCRTRB7,Reach-1         , 4
Up Type= 0
Dn Type= 3
Dn Slope=0.005
Boundary for River Rch & Prof#=MATHISCRTRB7,Reach-1         , 5
Up Type= 0
Dn Type= 3
Dn Slope=0.005
Boundary for River Rch & Prof#=MATHISCRTRB7,Reach-1         , 6
Up Type= 0
Dn Type= 3
Dn Slope=0.005
Boundary for River Rch & Prof#=MATHISCRTRB7,Reach-1         , 7
Up Type= 0
Dn Type= 3
Dn Slope=0.005
DSS Import GetInterval= 0
DSS Import GetPeak= 0
DSS Import FillOption= 0

--- MATHISCREEKTRIB7.g01 (geometry) ---

Geom Title=Existing Conditions
Program Version=4.10

River Reach=MATHISCRTRB7    ,Reach-1
Reach XY= 30
      3560031.18     10268058.36      3560060.79     10268156.77
      3560025.34     10268233.76      3560027.28     10268264.19
      3560047.07     10268278.53      3560112.86     10268275.74
      3560135.09     10268294.49      3560175.02     10268361.51
      3560275.71     10268410.81      3560343.07      10268368.8
      3560391.68     10268353.52      3560472.93     10268361.16
      3560528.19     10268272.77      3560561.65     10268134.08
      3560599.87     10268083.38        3560628.     10268081.04
      3560692.56     10268051.78      3560760.65     10268090.39
      3560824.15     10268078.52      3560848.46     10268032.34
      3561001.93     10267983.73       3561100.2     10268007.34
      3561151.03     10268042.01      3561236.44     10268042.53
      3561295.82     10268060.23      3561499.46     10268230.55
      3561538.98     10268235.27       3561613.7     10268185.51
      3561690.85     10268168.61      3561742.11     10268141.64

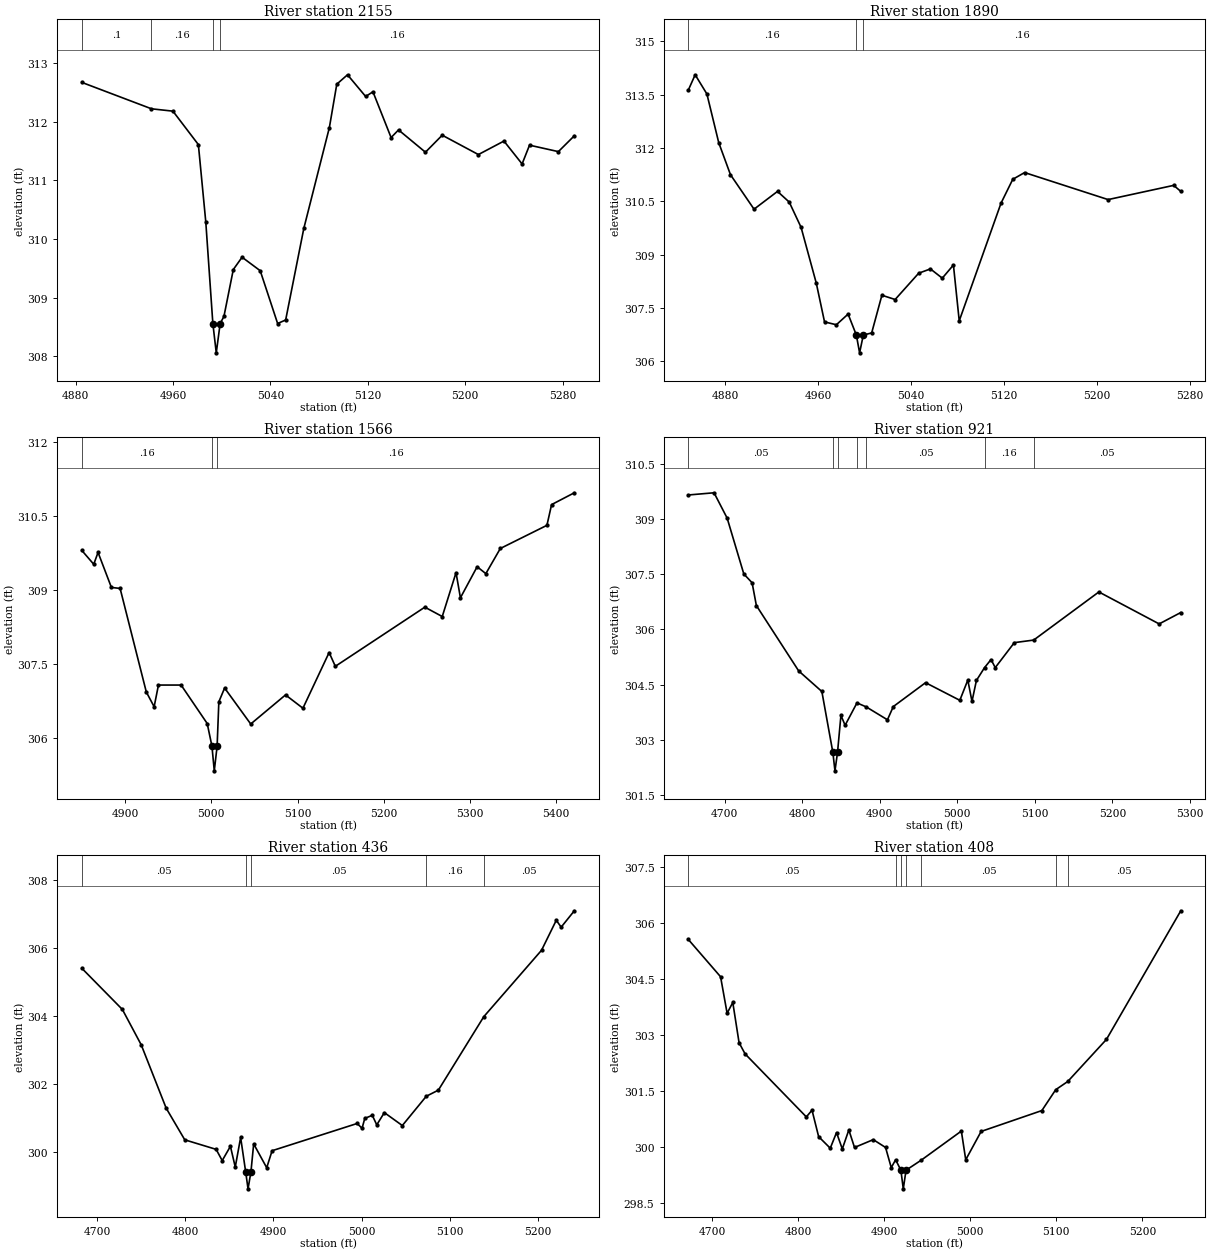
Type RM Length L Ch R = 1 ,2155    ,265,265,265
BEGIN DESCRIPTION:
UNT05214 IN WICK 3.0
END DESCRIPTION:
XS GIS Cut Line= 2
      3559929.56     10268321.78      3560262.88     10268092.62
#Sta/Elev= 30
  4885.2  312.67  4942.4  312.22    4960  312.18  4980.9  311.61    4987  310.29
  4992.8  308.56  4995.6  308.06  4998.8  308.56  5001.9  308.68  5009.6  309.48
  5016.8  309.69  5031.7  309.46    5046  308.56  5052.6  308.62  5067.5  310.18
  5088.5   311.9  5094.6  312.64  5103.4   312.8  5118.3  312.43  5124.3  312.51
  5139.2  311.73  5145.3  311.86  5167.4  311.48  5181.2  311.77  5210.9  311.44
  5231.9  311.67  5246.8  311.28  5252.9   311.6  5276.6  311.49  5289.7  311.76
#Mann= 4 ,-1 , 0
  4885.2      .1       0  4942.4     .16       0  4992.8     .07       0
  4998.8     .16       0
Bank Sta=4992.8,4998.8
XS Rating Curve= 0 ,0
Exp/Cntr=0.3,0.1

Type RM Length L Ch R = 1 ,1890    ,324,324,324
BEGIN DESCRIPTION:
Mapping XS 279dee6f
END DESCRIPTION:
XS GIS Cut Line= 2
      3560199.77     10268537.46      3560267.79     10268118.85
#Sta/Elev= 30
    4848  313.63  4853.9  314.06    4864  313.52  4874.2  312.15  4884.3  311.25
  4904.6  310.28  4924.8  310.78  4934.9  310.48  4945.1  309.77  4958.2   308.2
  4965.3  307.11  4975.5  307.03  4985.6  307.33  4992.7  306.74  4995.5  306.24
  4998.7  306.74  5005.9   306.8  5014.7  307.86  5026.1  307.74  5046.4  308.48
  5056.5   308.6  5066.7  308.34  5076.3  308.71  5081.3  307.14  5117.3  310.45
  5127.4  311.12  5137.6  311.31  5209.5  310.55    5266  310.95  5272.1  310.78
#Mann= 3 ,-1 , 0
    4848     .16       0  4992.7     .07       0  4998.7     .16       0
Bank Sta=4992.7,4998.7
XS Rating Curve= 0 ,0
Exp/Cntr=0.3,0.1

Type RM Length L Ch R = 1 ,1566    ,645,645,645
BEGIN DESCRIPTION:
UNT05214 IN WICK 2.0
END DESCRIPTION:
XS GIS Cut Line= 3
      3560519.77     10268465.62       3560451.3     10267995.04
      3560415.95     10267905.71
#Sta/Elev= 30
  4849.7  309.81  4863.5  309.53  4868.5  309.77    4884  309.06  4894.1  309.04
  4924.5  306.94  4933.6  306.64  4938.6  307.08  4964.9  307.08  4995.2   306.3
  5000.7  305.84  5003.4  305.34  5006.7  305.84  5008.7  306.74  5015.4  307.02
  5045.7  306.29  5086.1  306.88  5106.3  306.61  5136.7  307.74  5143.9  307.46
  5247.8  308.66    5268  308.47    5284  309.36  5289.1  308.85  5308.5  309.48
  5318.6  309.34  5335.4  309.85  5389.5  310.32  5394.9  310.74  5421.3  310.98
#Mann= 3 ,-1 , 0
  4849.7     .16       0  5000.7     .07       0  5006.7     .16       0
Bank Sta=5000.7,5006.7
XS Rating Curve= 0 ,0
Exp/Cntr=0.3,0.1

Type RM Length L Ch R = 1 ,921     ,485,485,485
BEGIN DESCRIPTION:
Mapping XS 82895263
END DESCRIPTION:
XS GIS Cut Line= 2
      3560805.45     10268328.41      3561034.24     10267735.63
#Sta/Elev= 30
  4652.9  309.66  4686.1  309.72    4703  309.03  4724.5  307.51  4735.2  307.27
  4740.7  306.65  4795.3  304.87  4825.2  304.31  4839.4  302.65  4842.1  302.15
  4845.4  302.65  4849.8  303.66  4855.2  303.39  4870.5     304  4882.5  303.89
  4909.8  303.54  4917.4   303.9    4959  304.55  5003.2  304.07  5013.5  304.62
  5018.9  304.04  5024.6  304.61  5035.1  304.96  5043.5  305.18  5048.9  304.96
  5073.5  305.64  5098.5  305.71  5182.6  307.02  5260.4  306.15  5288.3  306.46
#Mann= 7 ,-1 , 0
  4652.9     .05       0  4839.4     .03       0  4845.4     .05       0
  4870.5     .16       0  4882.5     .05       0  5035.1     .16       0
  5098.5     .05       0
Bank Sta=4839.4,4845.4
XS Rating Curve= 0 ,0
Exp/Cntr=0.3,0.1

Type RM Length L Ch R = 1 ,436     ,28,28,28
BEGIN DESCRIPTION:
Mapping XS 3667cb8b
END DESCRIPTION:
XS GIS Cut Line= 6
       3561179.8     10268374.56      3561302.22     10268258.65
      3561347.79     10268193.55      3561368.62     10268120.63
       3561354.3     10268052.92      3561279.63     10267904.88
#Sta/Elev= 30
  4682.6  305.41  4728.6   304.2    4750  303.16  4778.3   301.3  4799.4  300.37
    4835  300.09  4841.9  299.76  4851.2  300.18  4856.7  299.57  4862.8  300.44
  4868.5  299.43  4871.2  298.93  4874.5  299.43  4877.6  300.25  4892.4  299.55
  4898.5  300.05    4995  300.85  5000.6  300.71  5003.7     301  5012.2  301.09
  5017.3  300.81  5025.9  301.17  5046.3  300.79  5073.5  301.65  5087.2  301.83
  5138.8  303.99  5204.3  305.94    5221  306.82  5226.6  306.62  5241.5   307.1
#Mann= 5 ,-1 , 0
  4682.6     .05       0  4868.5     .03       0  4874.5     .05       0
  5073.5     .16       0  5138.8     .05       0
Bank Sta=4868.5,4874.5
XS Rating Curve= 0 ,0
Exp/Cntr=0.3,0.1

Type RM Length L Ch R = 1 ,408     ,90,90,90
BEGIN DESCRIPTION:
Mapping XS 9b258b9c
END DESCRIPTION:
XS GIS Cut Line= 6
       3561187.6     10268390.19      3561307.43       10268286.
      3561375.13     10268209.17      3561394.66     10268115.42
      3561385.55     10268045.11      3561328.26      10267912.3
#Sta/Elev= 30
  4672.2  305.56  4709.7  304.56  4717.3  303.58  4723.9  303.87  4731.2  302.79
  4738.2  302.49  4809.4   300.8    4816  300.98  4823.7  300.27  4837.2  299.96
  4844.5  300.38  4851.2  299.94  4858.8  300.45  4865.4  299.98  4887.2  300.19
  4901.5  299.98  4908.1  299.44  4913.2  299.65  4919.3  299.37  4922.1  298.87
  4925.3  299.37    4943  299.64  4989.6  300.42  4994.7  299.65  5012.6  300.41
  5083.2  300.97  5099.3  301.53  5113.3  301.75  5158.3  302.88  5244.7  306.33
#Mann= 7 ,-1 , 0
  4672.2     .05       0  4913.2     .12       0  4919.3     .03       0
  4925.3     .12       0    4943     .05       0  5099.3     .16       0
  5113.3     .05       0
Bank Sta=4919.3,4925.3
XS Rating Curve= 0 ,0
Exp/Cntr=0.3,0.1

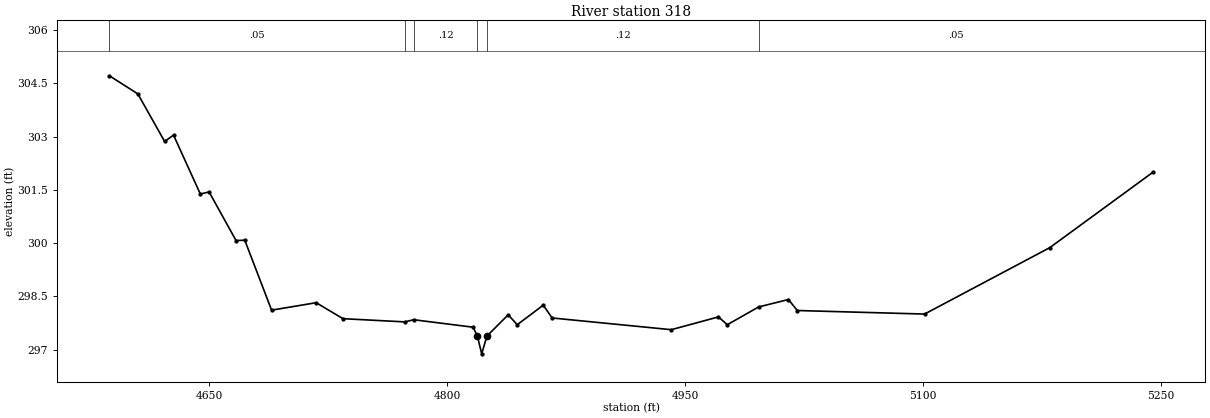
Type RM Length L Ch R = 1 ,318     ,0,0,0
BEGIN DESCRIPTION:
UNT05214 IN WICK 1.0
END DESCRIPTION:
XS GIS Cut Line= 4
      3561198.03     10268493.04      3561343.88     10268421.41
      3561506.64     10268110.21      3561493.63     10267966.69
#Sta/Elev= 30
  4587.2  304.71  4605.1   304.2    4622  302.86  4627.6  303.04  4644.5  301.38
    4650  301.44    4667  300.07  4672.5  300.08  4689.4  298.11  4717.5  298.32
  4734.4  297.87  4773.3  297.78    4779  297.84  4816.4  297.63  4819.1  297.38
  4821.8  296.88  4825.1  297.38  4838.5  297.98  4844.2   297.7  4860.6  298.25
  4866.2  297.89  4941.3  297.56    4971  297.92  4976.6   297.7  4996.3   298.2
  5015.1  298.41  5020.7   298.1  5100.9     298  5179.8  299.87    5245     302
#Mann= 6 ,-1 , 0
  4587.2     .05       0  4773.3     .16       0    4779     .12       0
  4819.1     .03       0  4825.1     .12       0  4996.3     .05       0
Bank Sta=4819.1,4825.1
XS Rating Curve= 0 ,0
Exp/Cntr=0.3,0.1

Chan Stop Cuts=-1
Use User Specified Reach Order=0
Composite Channel Slope=5