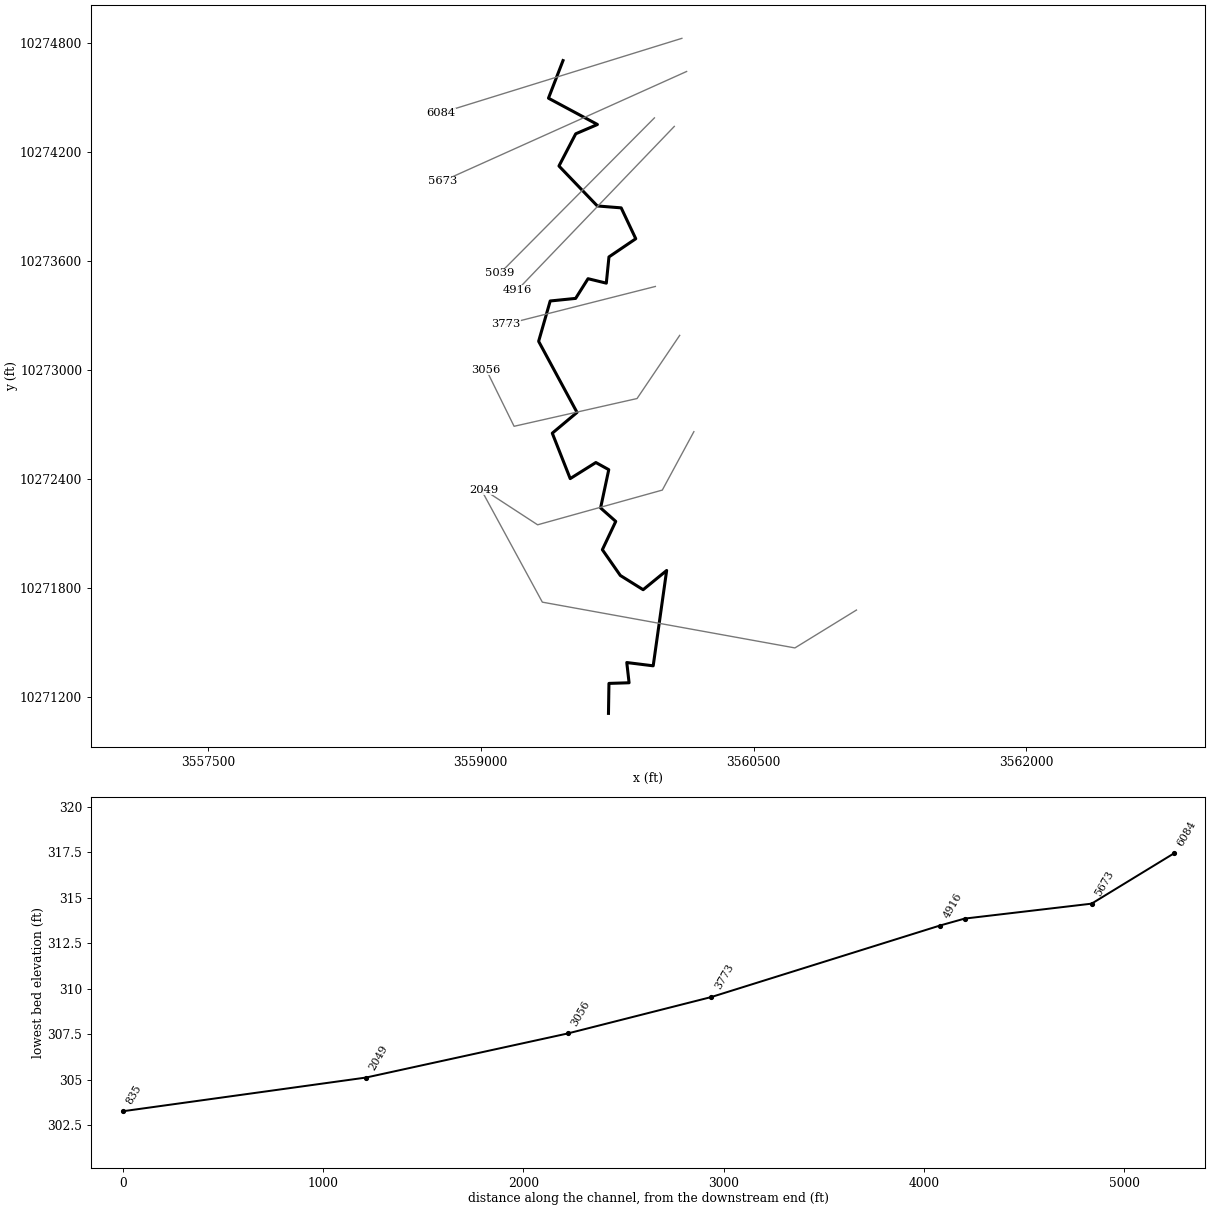
--- MATHISCREEKTRIB9.prj (project) ---

Proj Title=MATHIS CREEK TRIB 9 1
Current Plan=p01
Default Exp/Contr=0.3,0.1
English Units
Geom File=g01
Flow File=f01
Plan File=p01
Y Axis Title=Elevation
X Axis Title(PF)=Main Channel Distance
X Axis Title(XS)=Station
BEGIN DESCRIPTION:
UNT0502 IN WICK
END DESCRIPTION:
DSS Export Rating Curves= 0
DSS Export Rating Curve Sorted= 0
DSS Export Volume Flow Curves= 0
DXF Filename=UNT0502 IN WICK.
DXF OffsetX= 0
DXF OffsetY= 0
DXF ScaleX= 1
DXF ScaleY= 10

--- MATHISCREEKTRIB9.p01 (plan) ---

Plan Title=Multiple Run
Short Identifier=Multiple
Geom File=g01
Flow File=f01
Subcritical Flow
K Sum by GR= 0
Std Step Tol= 0.01
Critical Tol= 0.01
Num of Std Step Trials= 20
Max Error Tol= 0.3
Flow Tol Ratio= 0.001
Split Flow NTrial= 30
Split Flow Tol= 0.02
Split Flow Ratio= 0.02
Log Output Level= 0
Friction Slope Method= 1
Unsteady Friction Slope Method= 2
Unsteady Bridges Friction Slope Method= 1
Parabolic Critical Depth
Global Vel Dist=  1 , 1 , 1
Global Log Level= 0
CheckData=True
Encroach Param= -1, 0, 0, 0
BEGIN DESCRIPTION:
Multiple Run
END DESCRIPTION:

--- MATHISCREEKTRIB9.f01 (steady flow) ---

Flow Title=Multiple
Program Version=4.10
Number of Profiles= 7
Profile Names=10-year,25-year,50-year,1pct_min,100-year,1pct_plu,500-year
River Rch & RM=UNT0502 IN WICK,Reach-1         ,6084
     422     557     664     581     786    1063    1103
River Rch & RM=UNT0502 IN WICK,Reach-1         ,835
     579     780     943     835    1129    1527    1625
River Rch & RM=MATHISCRTRIB91,Reach-1         ,6084
     422     557     664     581     786    1063    1103
River Rch & RM=MATHISCRTRIB91,Reach-1         ,835
     579     780     943     835    1129    1527    1625
Boundary for River Rch & Prof#=MATHISCRTRIB91,Reach-1         , 1
Up Type= 0
Dn Type= 3
Dn Slope=0.005
Boundary for River Rch & Prof#=MATHISCRTRIB91,Reach-1         , 2
Up Type= 0
Dn Type= 3
Dn Slope=0.005
Boundary for River Rch & Prof#=MATHISCRTRIB91,Reach-1         , 3
Up Type= 0
Dn Type= 3
Dn Slope=0.005
Boundary for River Rch & Prof#=MATHISCRTRIB91,Reach-1         , 4
Up Type= 0
Dn Type= 3
Dn Slope=0.005
Boundary for River Rch & Prof#=MATHISCRTRIB91,Reach-1         , 5
Up Type= 0
Dn Type= 3
Dn Slope=0.005
Boundary for River Rch & Prof#=MATHISCRTRIB91,Reach-1         , 6
Up Type= 0
Dn Type= 3
Dn Slope=0.005
Boundary for River Rch & Prof#=MATHISCRTRIB91,Reach-1         , 7
Up Type= 0
Dn Type= 3
Dn Slope=0.005
DSS Import GetInterval= 0
DSS Import GetPeak= 0
DSS Import FillOption= 0

--- MATHISCREEKTRIB9.g01 (geometry) ---

Geom Title=Existing Conditions
Program Version=4.10

River Reach=MATHISCRTRIB91  ,Reach-1
Reach XY= 30
      3559452.11     10274701.64       3559372.1     10274494.84
      3559641.48     10274350.21        3559522.     10274299.03
      3559429.81     10274121.94      3559640.75     10273902.15
        3559772.     10273891.74      3559852.21     10273721.94
      3559704.81     10273621.94      3559690.23     10273477.67
      3559589.71     10273502.15      3559521.48     10273393.82
      3559381.65     10273379.63      3559318.01     10273157.78
      3559529.22     10272766.74       3559393.1     10272652.55
      3559491.66     10272402.75      3559632.74     10272491.19
       3559703.7      10272451.9      3559658.76     10272241.44
      3559742.13     10272167.36       3559668.5     10272011.76
      3559767.27     10271870.06      3559892.76     10271791.74
      3560022.08      10271897.5      3559948.09     10271373.15
      3559802.78     10271391.23      3559815.41     10271279.93
      3559704.77     10271276.51      3559702.11     10271111.64

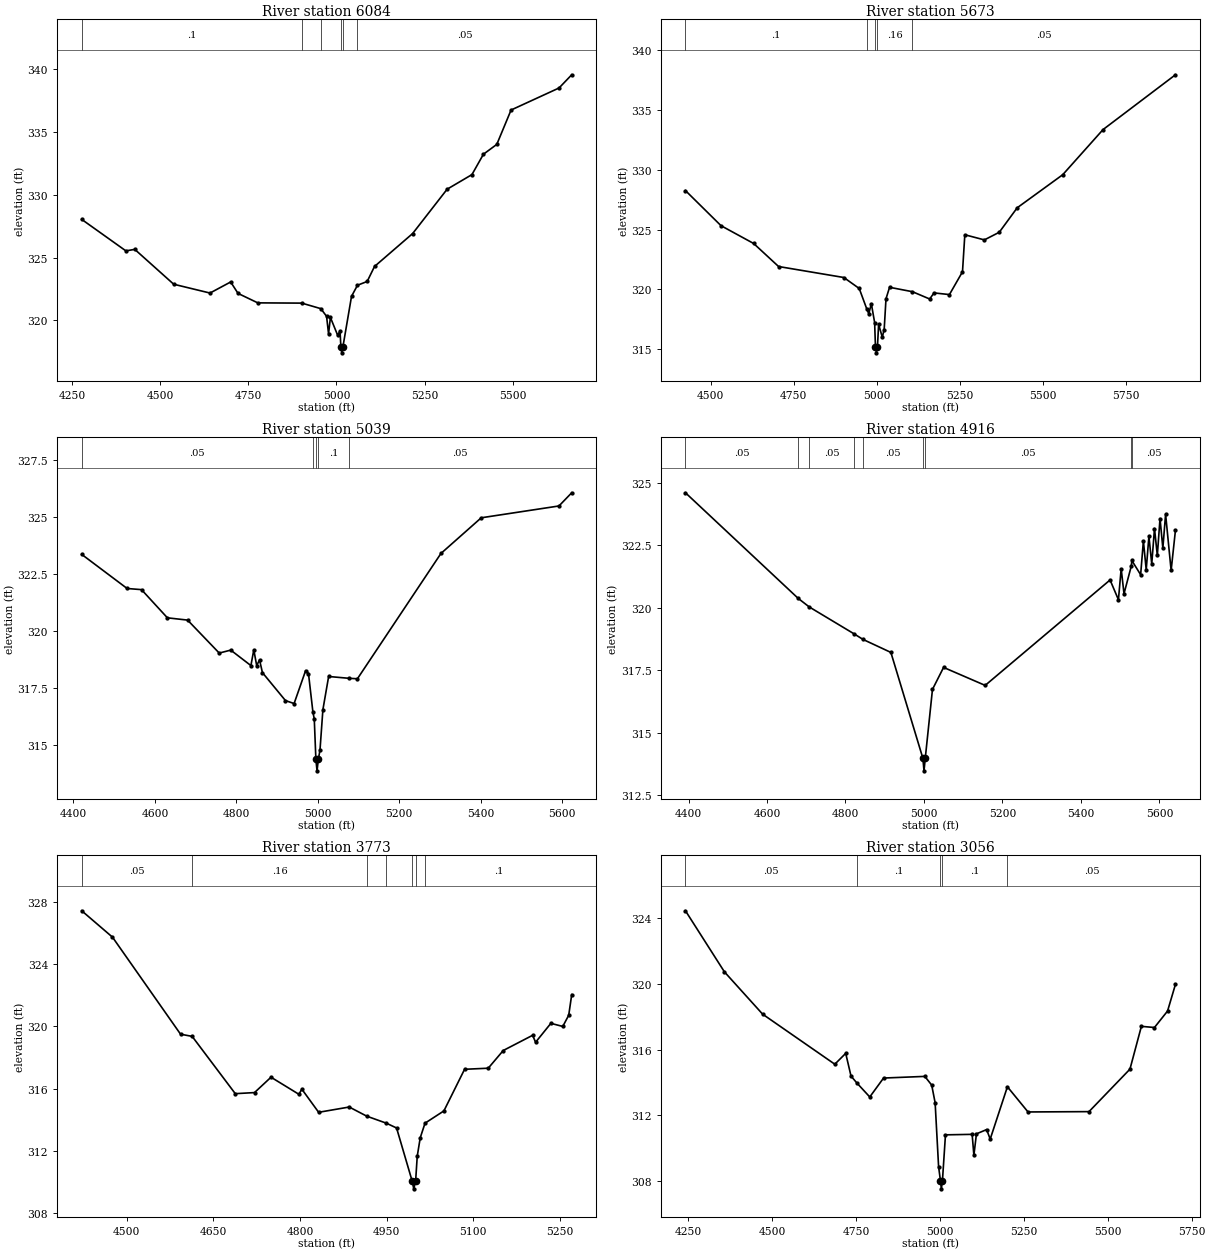
Type RM Length L Ch R = 1 ,6084    ,411,411,411
BEGIN DESCRIPTION:
UNT0502 IN WICK 8.0
END DESCRIPTION:
XS GIS Cut Line= 2
      3560105.82     10274824.03       3558777.7     10274412.58
#Sta/Elev= 30
  4277.1  328.03  4402.4  325.53  4427.6  325.65  4538.1  322.88  4641.1  322.18
  4699.7  323.06  4720.7  322.15  4776.7   321.4  4901.6  321.38  4955.6  320.94
  4971.9  320.33  4977.5  318.94  4982.8  320.24  5003.3  318.83  5010.1  319.17
  5012.4  317.93  5015.1  317.43  5018.4  317.93  5042.7  321.92  5059.6   322.8
  5087.1   323.1  5107.9  324.29  5216.2  326.91    5314  330.43  5384.4  331.59
    5417  333.21  5454.9  333.99  5495.4  336.72  5631.5  338.47  5667.5  339.52
#Mann= 6 ,-1 , 0
  4277.1      .1       0  4901.6     .16       0  4955.6      .1       0
  5012.4     .07       0  5018.4      .1       0  5059.6     .05       0
Bank Sta=5012.4,5018.4
XS Rating Curve= 0 ,0
Exp/Cntr=0.3,0.1

Type RM Length L Ch R = 1 ,5673    ,634,634,634
BEGIN DESCRIPTION:
UNT0502 IN WICK 7.0
END DESCRIPTION:
XS GIS Cut Line= 2
      3560131.85     10274641.74      3558788.12     10274037.58
#Sta/Elev= 30
  4424.5  328.26  4531.4  325.32  4629.5  323.83  4704.5   321.9  4900.7  320.98
    4947  320.06  4969.9  318.33  4975.7  317.94  4983.4  318.79  4993.3  317.21
  4995.8  315.17  4998.6  314.67  5001.8  315.17  5005.3  317.06  5016.3  315.98
    5022  316.62  5027.5   319.2  5038.2  320.16  5107.1  319.79  5158.8  319.18
  5171.9  319.69  5218.2  319.55  5257.5  321.46  5264.5  324.56  5323.3  324.13
  5368.1  324.77    5422  326.82  5558.9  329.59  5680.1  333.37  5897.8  337.96
#Mann= 5 ,-1 , 0
  4424.5      .1       0  4969.9     .16       0  4995.8     .07       0
  5001.8     .16       0  5107.1     .05       0
Bank Sta=4995.8,5001.8
XS Rating Curve= 0 ,0
Exp/Cntr=0.3,0.1

Type RM Length L Ch R = 1 ,5039    ,123,123,123
BEGIN DESCRIPTION:
UNT0502 IN WICK 6.0
END DESCRIPTION:
XS GIS Cut Line= 2
       3559954.8     10274386.57      3559106.48     10273533.04
#Sta/Elev= 30
  4420.3  323.37  4531.8  321.87  4567.1  321.82  4630.7  320.58  4680.3  320.48
    4758  319.03  4786.3  319.16  4835.8  318.48  4842.9  319.17    4850  318.48
    4857  318.73  4864.1  318.17  4920.7  316.94  4941.9  316.81  4970.2  318.26
  4977.2  318.13  4988.2  316.42  4991.4  316.14  4995.4  314.35  4998.2  313.85
  5001.4  314.35  5005.5  314.77  5012.6  316.54  5026.7     318  5076.6  317.92
  5097.4   317.9  5302.5  323.41  5401.5  324.98  5592.4   325.5  5623.7  326.08
#Mann= 5 ,-1 , 0
  4420.3     .05       0  4988.2      .1       0  4995.4     .07       0
  5001.4      .1       0  5076.6     .05       0
Bank Sta=4995.4,5001.4
XS Rating Curve= 0 ,0
Exp/Cntr=0.3,0.1

Type RM Length L Ch R = 1 ,4916    ,1143,1143,1143
BEGIN DESCRIPTION:
UNT0502 IN WICK 5.0
END DESCRIPTION:
XS GIS Cut Line= 2
      3560064.13     10274339.64      3559199.58     10273438.64
#Sta/Elev= 30
  4392.2   324.6  4679.7  320.37  4707.7  320.03  4821.2  318.96  4844.7  318.73
  4915.7  318.21  4997.3  313.97  5000.1  313.47  5003.3  313.97  5021.7  316.73
    5050  317.61    5156  316.89  5474.3  321.11  5495.6  320.32  5502.6  321.56
  5509.8  320.56  5528.6  321.68  5529.7  321.89  5552.2  321.32  5559.2  322.67
  5566.4  321.52  5573.3  322.86  5580.5  321.75  5587.5  323.17  5594.7  322.09
  5601.6  323.57  5608.8  322.38  5615.8  323.74  5629.9  321.49  5640.9   323.1
#Mann= 9 ,-1 , 0
  4392.2     .05       0  4679.7      .1       0  4707.7     .05       0
  4821.2      .1       0  4844.7     .05       0  4997.3     .04       0
  5003.3     .05       0  5528.6      .1       0  5529.7     .05       0
Bank Sta=4997.3,5003.3
XS Rating Curve= 0 ,0
Exp/Cntr=0.3,0.1

Type RM Length L Ch R = 1 ,3773    ,717,717,717
BEGIN DESCRIPTION:
UNT0502 IN WICK 4.0
END DESCRIPTION:
XS GIS Cut Line= 2
      3559959.93     10273459.44      3559137.09     10273251.12
#Sta/Elev= 30
    4422  327.45  4475.3  325.75  4593.2   319.5  4613.3  319.36    4688  315.67
  4721.3  315.74  4749.9  316.73  4798.2  315.63  4803.3  315.96  4832.4  314.47
  4885.4  314.81  4915.8  314.22  4949.6  313.77  4967.4  313.46  4994.4  310.04
  4997.2  309.54  5000.4  310.04  5003.2  311.64  5008.4  312.83  5016.7  313.77
  5049.4  314.56  5085.2  317.24  5126.2  317.31  5152.2  318.45  5203.1  319.43
  5208.2  318.98  5234.7   320.2  5255.3     320  5265.6  320.72  5270.8  322.05
#Mann= 7 ,-1 , 0
    4422     .05       0  4613.3     .16       0  4915.8      .1       0
  4949.6     .16       0  4994.4     .07       0  5000.4     .16       0
  5016.7      .1       0
Bank Sta=4994.4,5000.4
XS Rating Curve= 0 ,0
Exp/Cntr=0.3,0.1

Type RM Length L Ch R = 1 ,3056    ,1007,1007,1007
BEGIN DESCRIPTION:
UNT0502 IN WICK 3.0
END DESCRIPTION:
XS GIS Cut Line= 4
      3560093.69     10273190.39      3559859.28     10272843.13
      3559183.01     10272690.45      3559029.41     10273002.76
#Sta/Elev= 30
  4241.4  324.43  4357.5  320.72  4471.4  318.15  4686.5  315.11    4719  315.77
  4734.8  314.39  4752.7  313.96  4790.7  313.12  4831.8  314.27  4954.8  314.37
  4975.3  313.84  4985.5  312.77  4995.8  308.89  5001.3  308.04    5004  307.54
  5007.3  308.04  5016.3  310.82  5095.8  310.85    5101  309.58  5108.6  310.88
    5139  311.14  5149.6  310.56  5200.9  313.74  5262.3  312.21  5444.1  312.23
  5566.1  314.81  5600.2  317.41  5639.1  317.34  5678.2  318.34  5701.7  319.96
#Mann= 5 ,-1 , 0
  4241.4     .05       0  4752.7      .1       0  5001.3     .07       0
  5007.3      .1       0  5200.9     .05       0
Bank Sta=5001.3,5007.3
XS Rating Curve= 0 ,0
Exp/Cntr=0.3,0.1

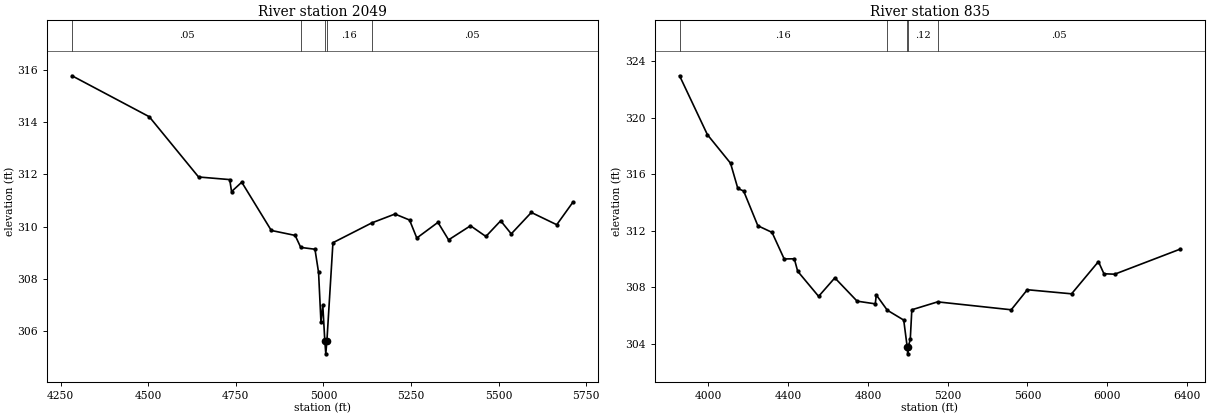
Type RM Length L Ch R = 1 ,2049    ,1214,1214,1214
BEGIN DESCRIPTION:
UNT0502 IN WICK 2.0
END DESCRIPTION:
XS GIS Cut Line= 4
      3560171.77     10272660.82      3559998.17     10272339.66
      3559312.41     10272148.68       3559017.5     10272340.98
#Sta/Elev= 30
  4282.7  315.78  4503.1  314.21  4643.8   311.9  4732.7   311.8  4737.9  311.34
    4767   311.7  4851.3  309.85  4919.4  309.66  4935.3   309.2  4975.9  309.13
  4986.2  308.24    4993  306.34  4998.2     307    5004  305.62  5006.8  305.12
    5010  305.62  5027.2  309.38  5138.1  310.14  5204.2  310.48  5245.8  310.25
  5266.5  309.56  5326.8  310.16  5357.2  309.49  5419.7  310.03  5463.6  309.62
  5505.8  310.22    5536  309.72  5593.3  310.54  5665.8  310.07  5711.7  310.93
#Mann= 5 ,-1 , 0
  4282.7     .05       0  4935.3     .16       0    5004     .07       0
    5010     .16       0  5138.1     .05       0
Bank Sta=5004,5010
XS Rating Curve= 0 ,0
Exp/Cntr=0.3,0.1

Type RM Length L Ch R = 1 ,835     ,0,0,0
BEGIN DESCRIPTION:
UNT0502 IN WICK 1.0
END DESCRIPTION:
XS GIS Cut Line= 4
      3561065.85     10271679.91      3560727.34      10271471.6
      3559338.45     10271723.34      3559002.68      10272341.1
#Sta/Elev= 30
  3854.9  322.96  3994.5  318.79  4110.5  316.77  4147.2  314.98  4176.3   314.8
  4247.6  312.34  4318.7  311.87  4379.6  309.99  4430.5     310  4447.3  309.12
  4552.4  307.34  4633.7  308.65  4745.5     307  4836.6  306.81  4841.7  307.44
  4896.9  306.36  4979.3  305.66  4996.6  303.77  4999.3  303.27  5002.6  303.77
  5012.2  304.31  5019.9  306.39  5149.3  306.95  5518.6  306.39  5599.2  307.81
  5821.3  307.52    5956   309.8  5983.6  308.94  6037.6  308.91    6367  310.69
#Mann= 5 ,-1 , 0
  3854.9     .16       0  4896.9     .12       0  4996.6     .07       0
  5002.6     .12       0  5149.3     .05       0
Bank Sta=4996.6,5002.6
XS Rating Curve= 0 ,0
Exp/Cntr=0.3,0.1

Chan Stop Cuts=-1
Use User Specified Reach Order=0
Composite Channel Slope=5