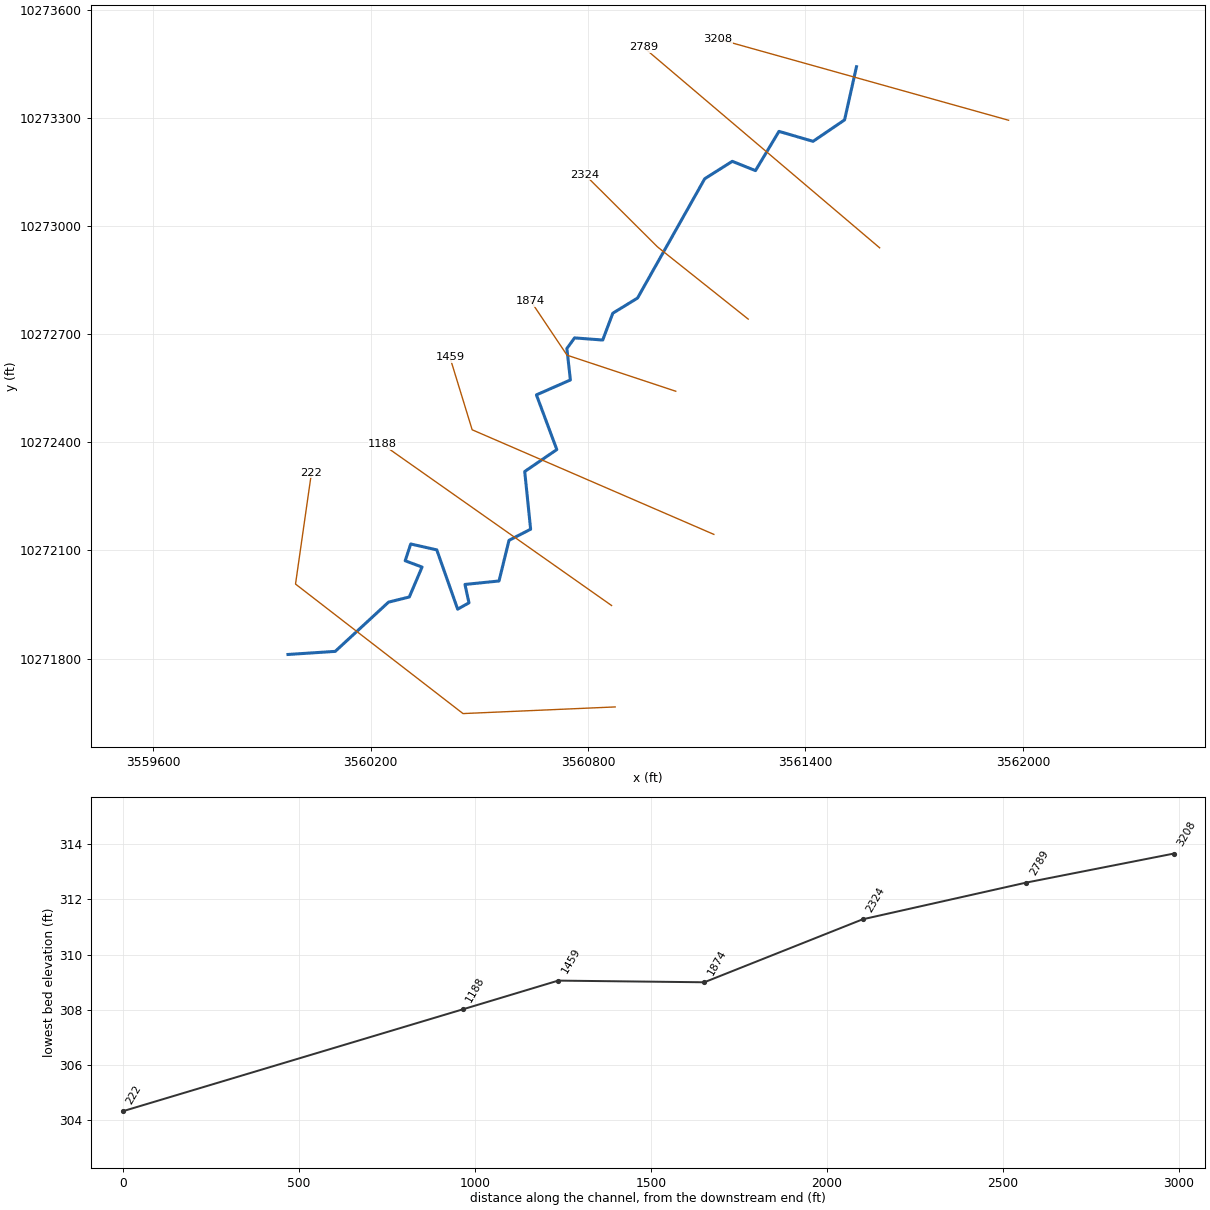
--- MATHISCREEKTRIB9.prj (project) ---

Proj Title=MATHIS CREEK TRIB 9
Current Plan=p01
Default Exp/Contr=0.3,0.1
English Units
Geom File=g01
Flow File=f01
Plan File=p01
Y Axis Title=Elevation
X Axis Title(PF)=Main Channel Distance
X Axis Title(XS)=Station
BEGIN DESCRIPTION:
UNT05210 IN WICK
END DESCRIPTION:
DSS Export Rating Curves= 0
DSS Export Rating Curve Sorted= 0
DSS Export Volume Flow Curves= 0
DXF OffsetX= 0
DXF OffsetY= 0
DXF ScaleX= 1
DXF ScaleY= 10

--- MATHISCREEKTRIB9.p01 (plan) ---

Plan Title=Multiple Run
Short Identifier=Multiple
Geom File=g01
Flow File=f01
Subcritical Flow
K Sum by GR= 0
Std Step Tol= 0.01
Critical Tol= 0.01
Num of Std Step Trials= 20
Max Error Tol= 0.3
Flow Tol Ratio= 0.001
Split Flow NTrial= 30
Split Flow Tol= 0.02
Split Flow Ratio= 0.02
Log Output Level= 0
Friction Slope Method= 1
Unsteady Friction Slope Method= 2
Unsteady Bridges Friction Slope Method= 1
Parabolic Critical Depth
Global Vel Dist=  1 , 1 , 1
Global Log Level= 0
CheckData=True
Encroach Param= -1, 0, 0, 0
BEGIN DESCRIPTION:
Multiple Run
END DESCRIPTION:

--- MATHISCREEKTRIB9.f01 (steady flow) ---

Flow Title=Multiple
Program Version=4.10
Number of Profiles= 7
Profile Names=10-year,25-year,50-year,1pct_min,100-year,1pct_plu,500-year
River Rch & RM=UNT05210 IN WICK,Reach-1         ,3208
     254     328     384     332     449     607     613
River Rch & RM=MATHISCRTRB9,Reach-1         ,3208
     254     328     384     332     449     607     613
Boundary for River Rch & Prof#=MATHISCRTRB9,Reach-1         , 1
Up Type= 0
Dn Type= 3
Dn Slope=0.005
Boundary for River Rch & Prof#=MATHISCRTRB9,Reach-1         , 2
Up Type= 0
Dn Type= 3
Dn Slope=0.005
Boundary for River Rch & Prof#=MATHISCRTRB9,Reach-1         , 3
Up Type= 0
Dn Type= 3
Dn Slope=0.005
Boundary for River Rch & Prof#=MATHISCRTRB9,Reach-1         , 4
Up Type= 0
Dn Type= 3
Dn Slope=0.005
Boundary for River Rch & Prof#=MATHISCRTRB9,Reach-1         , 5
Up Type= 0
Dn Type= 3
Dn Slope=0.005
Boundary for River Rch & Prof#=MATHISCRTRB9,Reach-1         , 6
Up Type= 0
Dn Type= 3
Dn Slope=0.005
Boundary for River Rch & Prof#=MATHISCRTRB9,Reach-1         , 7
Up Type= 0
Dn Type= 3
Dn Slope=0.005
DSS Import GetInterval= 0
DSS Import GetPeak= 0
DSS Import FillOption= 0

--- MATHISCREEKTRIB9.g01 (geometry) ---

Geom Title=Existing Conditions
Program Version=4.10

River Reach=MATHISCRTRB9    ,Reach-1
Reach XY= 30
      3561540.89     10273441.48        3561508.     10273294.06
      3561421.01     10273234.62      3561326.99     10273262.28
      3561262.17     10273153.43       3561198.2      10273179.2
      3561122.15     10273130.95      3560936.68     10272800.05
      3560868.42     10272757.95      3560840.61     10272683.64
      3560762.86     10272689.55      3560741.68     10272660.03
      3560751.41     10272572.88      3560657.66     10272531.56
      3560713.91     10272379.82      3560625.36     10272319.06
      3560641.68     10272158.99      3560581.96     10272128.09
      3560554.41     10272015.42      3560460.43     10272005.86
      3560471.54     10271954.82      3560440.27     10271937.35
      3560382.66      10272101.7      3560310.78     10272118.02
       3560295.5     10272071.49      3560342.03     10272054.06
      3560306.88     10271971.04       3560249.5     10271956.73
      3560102.45     10271820.21      3559972.11     10271811.64

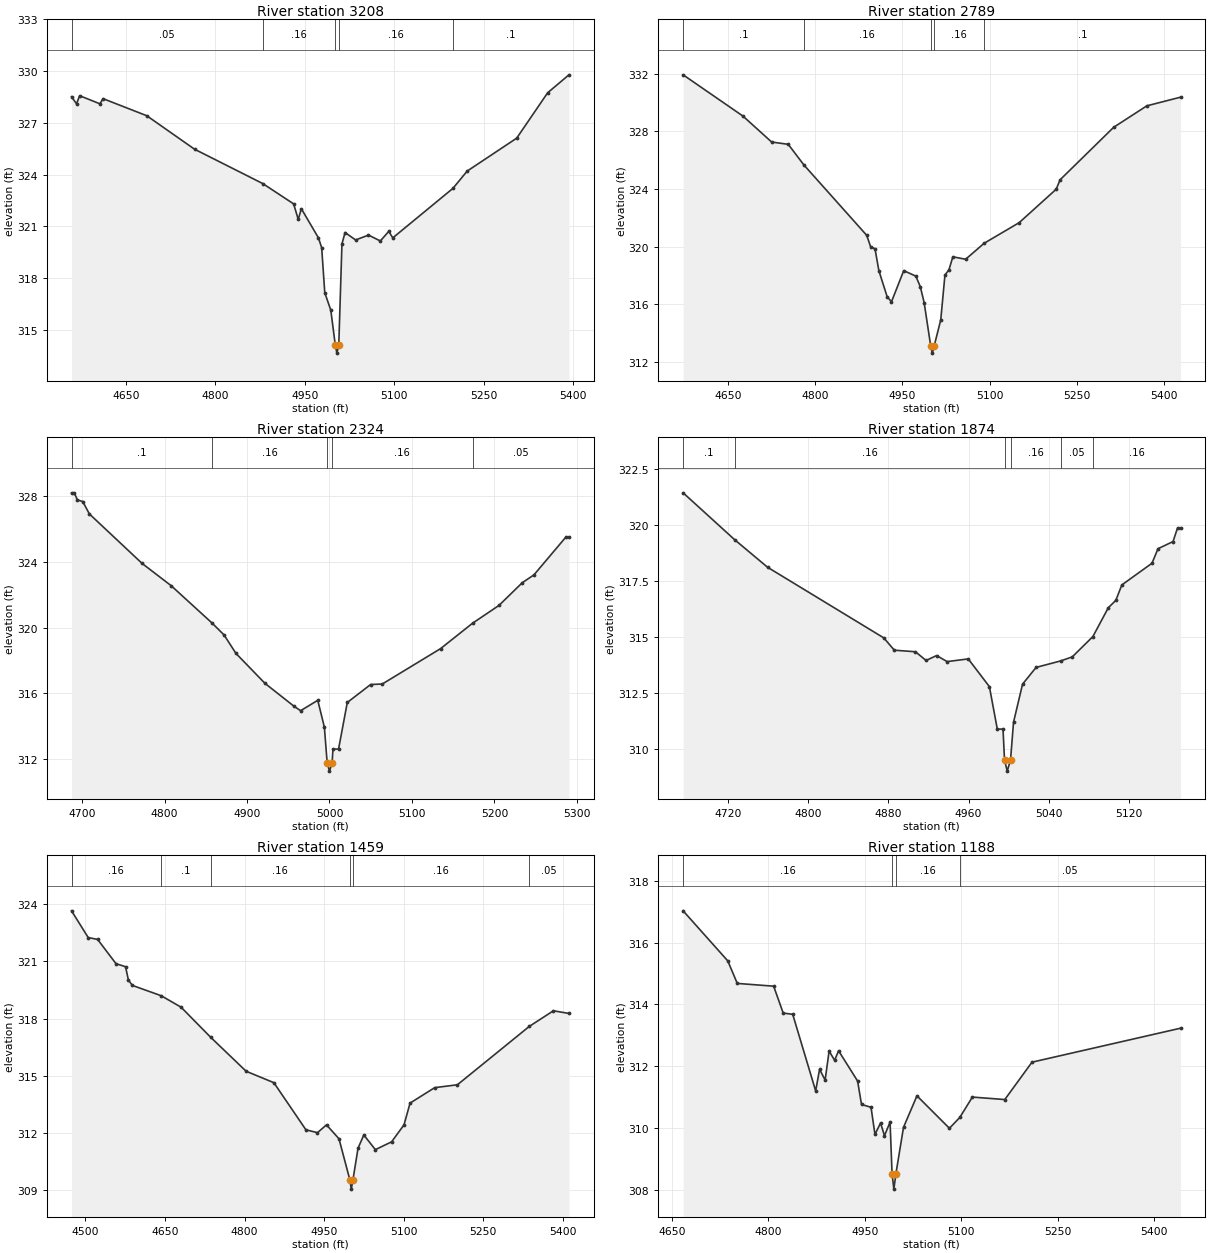
Type RM Length L Ch R = 1 ,3208    ,419,419,419
BEGIN DESCRIPTION:
UNT05210 IN WICK 5.0
END DESCRIPTION:
XS GIS Cut Line= 2
      3561960.62      10273293.1      3561157.73     10273518.78
#Sta/Elev= 30
  4558.7  328.52  4567.1  328.11  4572.3  328.58  4606.3  328.11  4611.5  328.41
  4684.8  327.42  4764.9  325.48  4879.2  323.49  4931.1  322.31  4938.8  321.41
    4944  322.03  4972.7  320.34  4978.1  319.77  4983.3  317.16  4993.4  316.15
  5000.8  314.16  5003.6  313.66  5006.8  314.16  5012.1  319.99  5017.3  320.65
    5035  320.22  5056.6   320.5  5076.5  320.16  5090.6  320.72  5097.3  320.34
  5198.2  323.21    5222  324.21  5305.1  326.12    5357  328.75  5392.7  329.79
#Mann= 5 ,-1 , 0
  4558.7     .05       0  4879.2     .16       0  5000.8     .07       0
  5006.8     .16       0  5198.2      .1       0
Bank Sta=5000.8,5006.8
XS Rating Curve= 0 ,0
Exp/Cntr=0.3,0.1

Type RM Length L Ch R = 1 ,2789    ,465,465,465
BEGIN DESCRIPTION:
Mapping XS 00286600
END DESCRIPTION:
XS GIS Cut Line= 2
      3561604.79     10272939.33      3560953.72     10273494.91
#Sta/Elev= 30
  4572.6  331.91  4675.5  329.05  4724.9  327.25  4753.5  327.09  4780.4  325.66
  4888.5  320.78  4895.1     320  4902.8  319.84  4909.4  318.33  4923.6  316.53
  4931.1  316.17  4952.2  318.33    4973  317.95  4980.7  317.22  4987.3  316.12
  4998.6  313.11  5001.3  312.61  5004.6  313.11  5015.9  314.92  5023.1  318.02
  5030.1   318.4  5036.7  319.29  5058.7  319.12  5090.6  320.23  5150.9  321.66
  5214.6  323.98  5221.2  324.63  5313.4  328.27  5370.5  329.76  5428.5  330.36
#Mann= 5 ,-1 , 0
  4572.6      .1       0  4780.4     .16       0  4998.6     .07       0
  5004.6     .16       0  5090.6      .1       0
Bank Sta=4998.6,5004.6
XS Rating Curve= 0 ,0
Exp/Cntr=0.3,0.1

Type RM Length L Ch R = 1 ,2324    ,450,450,450
BEGIN DESCRIPTION:
UNT05210 IN WICK 4.0
END DESCRIPTION:
XS GIS Cut Line= 3
      3561242.09     10272741.66      3560992.11     10272941.64
      3560792.09     10273141.66
#Sta/Elev= 30
  4687.3  328.18  4690.5  328.18  4694.5  327.75  4700.9  327.65  4708.9   326.9
  4772.9  323.89  4808.1  322.54  4857.7  320.27  4872.2  319.55  4886.6  318.43
  4921.8  316.61    4957  315.22    4965  314.95  4985.8  315.58  4993.8  313.95
  4997.2  311.78    5000  311.28  5003.2  311.78  5004.2  312.62    5011  312.62
  5021.6  315.45  5049.9  316.54    5064  316.57  5134.7  318.72  5173.4  320.26
  5205.4  321.34  5233.7  322.72  5247.9   323.2  5286.7   325.5  5290.3   325.5
#Mann= 5 ,-1 , 0
  4687.3      .1       0  4857.7     .16       0  4997.2     .07       0
  5003.2     .16       0  5173.4     .05       0
Bank Sta=4997.2,5003.2
XS Rating Curve= 0 ,0
Exp/Cntr=0.3,0.1

Type RM Length L Ch R = 1 ,1874    ,415,415,415
BEGIN DESCRIPTION:
UNT05210 IN WICK 3.0
END DESCRIPTION:
XS GIS Cut Line= 3
      3561042.12     10272541.64      3560742.11     10272641.64
      3560642.12     10272791.62
#Sta/Elev= 30
  4675.1  321.45  4726.6  319.35  4759.4  318.12  4875.4  314.96  4885.9  314.41
    4907  314.34  4917.6  313.95  4928.1  314.17  4938.6   313.9  4959.7  314.02
  4980.8  312.78  4988.7  310.88  4994.4  310.88  4995.9   309.5  4998.6     309
  5001.9   309.5  5004.9  311.19  5013.9  312.89  5027.4  313.64  5051.9  313.93
  5063.5  314.11  5084.1  315.02  5099.5  316.31    5107  316.64    5113  317.33
  5143.1   318.3  5149.1  318.95  5164.1  319.27  5168.6  319.88  5171.6  319.88
#Mann= 6 ,-1 , 0
  4675.1      .1       0  4726.6     .16       0  4995.9     .07       0
  5001.9     .16       0  5051.9     .05       0  5084.1     .16       0
Bank Sta=4995.9,5001.9
XS Rating Curve= 0 ,0
Exp/Cntr=0.3,0.1

Type RM Length L Ch R = 1 ,1459    ,271,271,271
BEGIN DESCRIPTION:
UNT05210 IN WICK 2.0
END DESCRIPTION:
XS GIS Cut Line= 3
      3561147.25     10272144.69      3560480.32     10272434.75
      3560418.91     10272635.91
#Sta/Elev= 30
  4473.8  323.65  4505.2  322.25    4523  322.15  4557.6  320.88  4575.6  320.72
    4581  320.02  4588.5  319.74  4642.7   319.2  4680.2   318.6  4736.1  317.02
  4802.9  315.24  4855.2  314.64  4915.6  312.17  4937.4  312.02  4954.4  312.43
  4977.9   311.7  4998.3  309.56  5001.1  309.06  5004.3  309.56  5013.8   311.2
  5024.7   311.9  5046.5  311.13  5077.1  311.54  5100.5  312.43  5111.9  313.57
  5158.3  314.38  5201.1  314.53  5336.6  317.59  5382.1  318.41  5411.4  318.27
#Mann= 6 ,-1 , 0
  4473.8     .16       0  4642.7      .1       0  4736.1     .16       0
  4998.3     .07       0  5004.3     .16       0  5336.6     .05       0
Bank Sta=4998.3,5004.3
XS Rating Curve= 0 ,0
Exp/Cntr=0.3,0.1

Type RM Length L Ch R = 1 ,1188    ,966,966,966
BEGIN DESCRIPTION:
Mapping XS 6c8504ca
END DESCRIPTION:
XS GIS Cut Line= 2
      3560865.03     10271947.44       3560233.5     10272394.07
#Sta/Elev= 30
  4667.5  317.03  4736.9  315.41  4751.7  314.68  4808.3  314.59  4823.1  313.72
  4837.9  313.68  4873.6   311.2  4879.7   311.9  4888.3  311.55  4894.5  312.49
  4903.1  312.19  4909.2   312.5  4938.8  311.52  4944.9  310.76  4959.7  310.67
  4965.8  309.79  4974.5  310.16  4980.6  309.75  4989.3  310.19  4992.4  308.52
  4995.2  308.02  4998.4  308.52  5010.2  310.02  5031.1  311.04  5081.6  309.99
  5097.7  310.34  5117.3     311  5167.7  310.92    5210  312.13    5441  313.23
#Mann= 4 ,-1 , 0
  4667.5     .16       0  4992.4     .07       0  4998.4     .16       0
  5097.7     .05       0
Bank Sta=4992.4,4998.4
XS Rating Curve= 0 ,0
Exp/Cntr=0.3,0.1

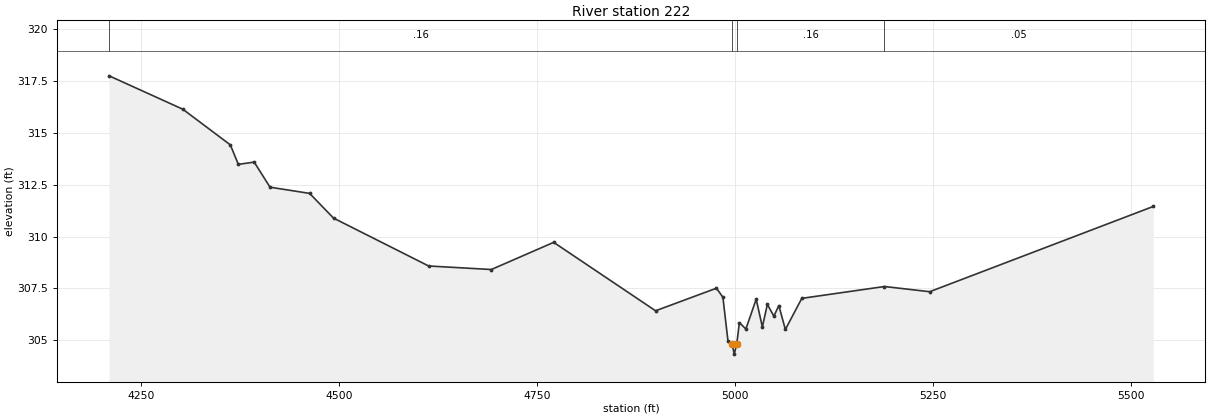
Type RM Length L Ch R = 1 ,222     ,0,0,0
BEGIN DESCRIPTION:
UNT05210 IN WICK 1.0
END DESCRIPTION:
XS GIS Cut Line= 4
        3560875.     10271666.17      3560455.11     10271647.73
      3559992.87     10272006.89      3560036.92     10272315.89
#Sta/Elev= 30
  4209.7  317.75  4302.7  316.14  4362.7  314.42  4372.8  313.48  4392.8  313.59
  4412.8  312.38  4462.8  312.08  4492.9  310.89    4613  308.58  4692.1  308.41
  4770.8  309.72  4899.4  306.42  4976.3  307.51  4984.4  307.07  4990.8  304.96
  4995.9  304.83  4998.7  304.33  5001.9  304.83  5005.2  305.85  5013.4  305.54
  5026.4  306.98  5034.2  305.64  5040.5  306.73  5048.7  306.16    5055  306.67
  5063.2  305.52    5084  307.02  5188.3  307.59  5245.4  307.34  5527.5  311.45
#Mann= 4 ,-1 , 0
  4209.7     .16       0  4995.9     .07       0  5001.9     .16       0
  5188.3     .05       0
Bank Sta=4995.9,5001.9
XS Rating Curve= 0 ,0
Exp/Cntr=0.3,0.1

Chan Stop Cuts=-1
Use User Specified Reach Order=0
Composite Channel Slope=5