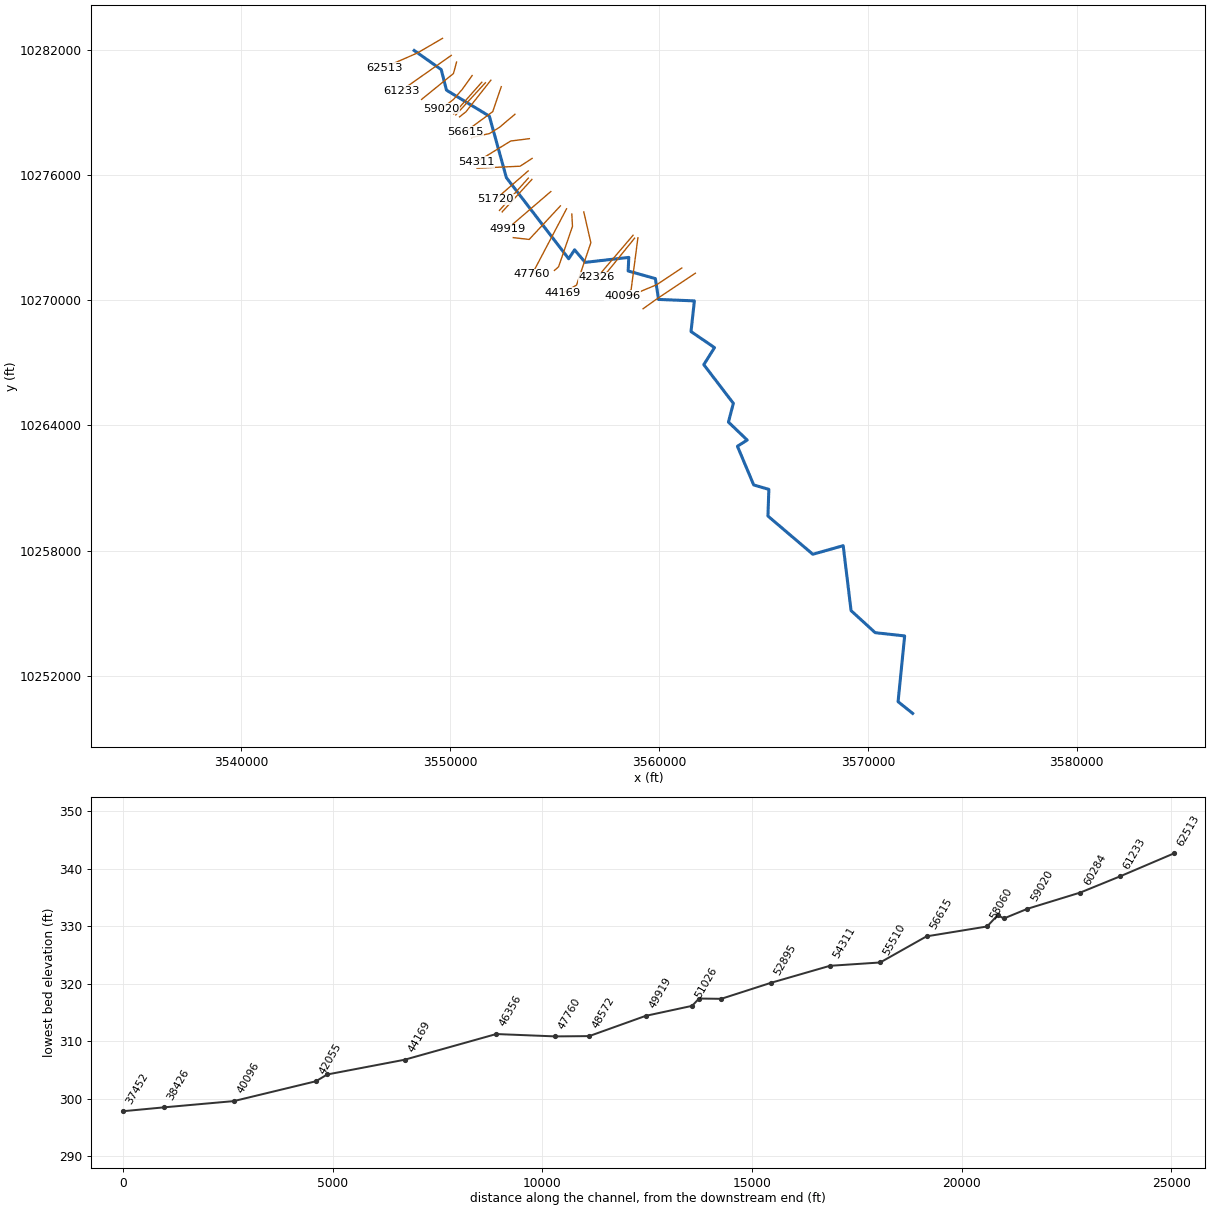
--- MATHIS CREEK.prj (project) ---

Proj Title=MATHIS CREEK Base Level Engineering
Current Plan=p01
Default Exp/Contr=0.3,0.1
English Units
Geom File=g01
Flow File=f01
Plan File=p01
Y Axis Title=Elevation
X Axis Title(PF)=Main Channel Distance
X Axis Title(XS)=Station
BEGIN DESCRIPTION:
MATHIS CREEK
END DESCRIPTION:
DSS Export Rating Curves= 0
DSS Export Rating Curve Sorted= 0
DSS Export Volume Flow Curves= 0
DXF OffsetX= 0
DXF OffsetY= 0
DXF ScaleX= 1
DXF ScaleY= 10

--- MATHIS CREEK.p01 (plan) ---

Plan Title=Multiple Run
Short Identifier=Multiple
Geom File=g01
Flow File=f01
Subcritical Flow
K Sum by GR= 0
Std Step Tol= 0.01
Critical Tol= 0.01
Num of Std Step Trials= 20
Max Error Tol= 0.3
Flow Tol Ratio= 0.001
Split Flow NTrial= 30
Split Flow Tol= 0.02
Split Flow Ratio= 0.02
Log Output Level= 0
Friction Slope Method= 1
Unsteady Friction Slope Method= 2
Unsteady Bridges Friction Slope Method= 1
Parabolic Critical Depth
Global Vel Dist=  1 , 1 , 1
Global Log Level= 0
CheckData=True
Encroach Param= -1, 0, 0, 0
BEGIN DESCRIPTION:
Multiple Run
END DESCRIPTION:

--- MATHIS CREEK.f01 (steady flow) ---

Flow Title=Multiple
Program Version=4.10
Number of Profiles= 7
Profile Names=10-year,25-year,50-year,1pct_min,100-year,1pct_plu,500-year
River Rch & RM=MATHIS CREEK,Reach-1         ,62513
     562     745     891     780    1054    1426    1480
River Rch & RM=MATHIS CREEK,Reach-1         ,58060
     884    1204    1466    1304    1764    2386    2561
River Rch & RM=MATHIS CREEK,Reach-1         ,55510
    1064    1457    1780    1588    2148    2905    3136
River Rch & RM=MATHIS CREEK,Reach-1         ,47760
    1220    1677    2055    1837    2484    3360    3643
River Rch & RM=MATHIS CREEK,Reach-1         ,42326
    1357    1872    2298    2057    2783    3763    4093
River Rch & RM=MATHIS CREEK,Reach-1         ,38426
    1718    2394    2958    2664    3603    4873    5366
River Rch & RM=MATHIS CREEK,Reach-1         ,32882
    1758    2444    3016    2712    3668    4961    5443
River Rch & RM=MATHIS CREEK,Reach-1         ,26791
    1996    2791    3458    3122    4221    5709    6313
River Rch & RM=MATHIS CREEK,Reach-1         ,22876
    2011    2811    3482    3141    4248    5745    6346
River Rch & RM=MATHIS CREEK,Reach-1         ,18911
    2023    2822    3490    3143    4250    5748    6328
River Rch & RM=MATHIS CREEK,Reach-1         ,13982
    2150    3006    3723    3359    4542    6143    6783
River Rch & RM=MATHIS CREEK,Reach-1         ,11199
    2222    3104    3843    3464    4684    6335    6985
River Rch & RM=MATHIS CREEK,Reach-1         ,3224
    2233    3117    3857    3474    4698    6354    6997
Boundary for River Rch & Prof#=MATHIS CREEK,Reach-1         , 1
Up Type= 0
Dn Type= 3
Dn Slope=0.00118
Boundary for River Rch & Prof#=MATHIS CREEK,Reach-1         , 2
Up Type= 0
Dn Type= 3
Dn Slope=0.00118
Boundary for River Rch & Prof#=MATHIS CREEK,Reach-1         , 3
Up Type= 0
Dn Type= 3
Dn Slope=0.00118
Boundary for River Rch & Prof#=MATHIS CREEK,Reach-1         , 4
Up Type= 0
Dn Type= 3
Dn Slope=0.00118
Boundary for River Rch & Prof#=MATHIS CREEK,Reach-1         , 5
Up Type= 0
Dn Type= 3
Dn Slope=0.00118
Boundary for River Rch & Prof#=MATHIS CREEK,Reach-1         , 6
Up Type= 0
Dn Type= 3
Dn Slope=0.00118
Boundary for River Rch & Prof#=MATHIS CREEK,Reach-1         , 7
Up Type= 0
Dn Type= 3
Dn Slope=0.00118
DSS Import GetInterval= 0
DSS Import GetPeak= 0
DSS Import FillOption= 0

--- MATHIS CREEK.g01 (geometry) ---

Geom Title=Existing Conditions
Program Version=4.10

River Reach=MATHIS CREEK    ,Reach-1
Reach XY= 30
       3548284.8     10281960.45       3549578.5     10281045.01
      3549830.34     10280059.43      3551880.81     10278815.72
      3552696.94     10275869.06      3555677.88     10271985.44
      3555962.51     10272411.89      3556469.01     10271812.48
      3558555.55     10272049.67      3558525.86     10271399.33
      3559827.43     10271034.61       3559979.5     10270037.14
      3561694.28     10269966.78      3561534.32     10268497.56
      3562658.55     10267730.01      3562145.74     10266913.07
       3563559.9     10265060.61      3563325.69     10264162.61
      3564222.11     10263301.64      3563755.25     10263005.24
      3564534.43     10261152.07      3565259.37     10260940.03
      3565215.23     10259661.98      3567364.14     10257832.22
      3568816.86      10258243.1      3569194.25     10255132.64
      3570349.19     10254075.95      3571758.71     10253920.31
      3571443.48     10250771.62      3572142.11     10250211.64

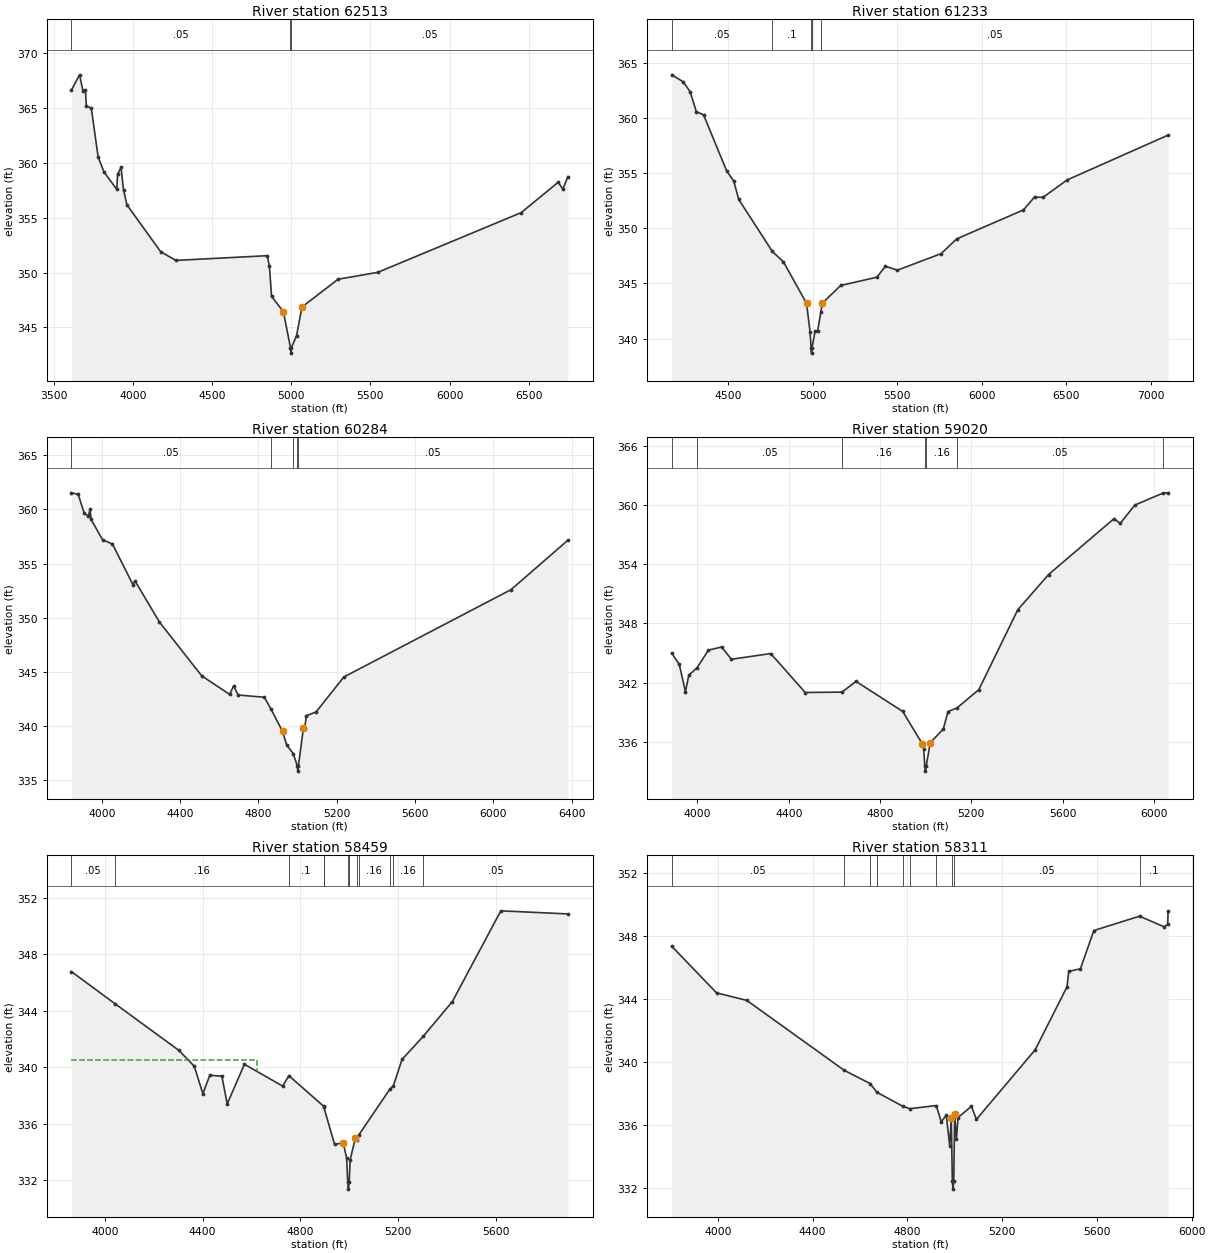
Type RM Length L Ch R = 1 ,62513   ,1280,1280,1280
BEGIN DESCRIPTION:
MATHIS CREEK 85.0
END DESCRIPTION:
XS GIS Cut Line= 3
      3549642.09     10282541.63      3548442.11     10281841.64
      3546842.06     10281141.62
#Sta/Elev= 30
  3611.7  366.67  3662.5  368.05    3684   366.6  3699.8   366.7  3705.5  365.24
    3737  364.99    3780  360.56  3817.2  359.18  3897.4  357.61  3903.2  358.99
  3924.7  359.61  3940.4  357.55  3961.9  356.19  4175.2  351.91  4271.2  351.12
  4848.4  351.55    4862  350.59  4875.6  347.83  4950.1  346.45    4995  343.16
  4997.8  342.66    5001  343.16  5033.3  344.25  5067.6  346.87  5295.6   349.4
  5546.7  350.03  6452.6  355.48  6686.1  358.25    6715  357.62  6747.4  358.76
#Mann= 3 ,-1 , 0
  3611.7     .05       0    4995    .035       0    5001     .05       0
Bank Sta=4950.1,5067.6
XS Rating Curve= 0 ,0
Exp/Cntr=0.3,0.1

Type RM Length L Ch R = 1 ,61233   ,949,949,949
BEGIN DESCRIPTION:
MATHIS CREEK 82.0
END DESCRIPTION:
XS GIS Cut Line= 2
      3550061.07     10281725.69      3547656.86      10280033.2
#Sta/Elev= 30
    4164  363.94  4230.9  363.32  4272.8  362.42  4309.5  360.61  4352.9   360.3
  4489.6  355.21  4531.4  354.29    4561  352.63  4759.5  347.92  4825.9  346.96
  4962.6   343.2  4983.5   340.6  4989.2  339.18    4992  338.68  4995.2  339.18
  5013.1  340.69  5027.9  340.66  5047.5  342.43  5055.5  343.21  5164.7  344.82
    5379  345.57  5429.5  346.56  5500.9  346.21  5759.6  347.71    5852  349.05
  6247.4  351.68  6312.7  352.85  6363.3  352.82  6506.1   354.4  7104.2  358.47
#Mann= 5 ,-1 , 0
    4164     .05       0  4759.5      .1       0  4989.2     .07       0
  4995.2      .1       0  5047.5     .05       0
Bank Sta=4962.6,5055.5
XS Rating Curve= 0 ,0
Exp/Cntr=0.3,0.1

Type RM Length L Ch R = 1 ,60284   ,1264,1264,1264
BEGIN DESCRIPTION:
MATHIS CREEK 80.0
END DESCRIPTION:
XS GIS Cut Line= 3
      3550312.82     10281404.54      3550165.25     10280857.65
      3548637.67     10279616.48
#Sta/Elev= 30
  3845.6  361.52  3879.7  361.38  3910.9  359.63  3931.5  359.38  3940.5     360
  3945.7  359.07    4004   357.2    4055  356.79  4159.3  353.06  4169.6  353.41
  4294.5  349.61  4510.8  344.64    4653  342.94  4673.8  343.73  4696.1  342.88
  4830.4  342.67  4864.8  341.56  4923.1  339.53  4944.4  338.27    4978  337.47
  4998.4  336.36  5001.1  335.86  5004.4  336.36  5030.1  339.86  5036.6  339.78
  5044.5  340.97    5094  341.31  5236.3  344.54  6089.6  352.59  6380.3  357.15
#Mann= 5 ,-1 , 0
  3845.6     .05       0  4864.8     .16       0    4978     .05       0
  4998.4     .03       0  5004.4     .05       0
Bank Sta=4923.1,5030.1
XS Rating Curve= 0 ,0
Exp/Cntr=0.3,0.1

Type RM Length L Ch R = 1 ,59020   ,561,561,561
BEGIN DESCRIPTION:
MATHIS CREEK 77.0
END DESCRIPTION:
XS GIS Cut Line= 4
       3551059.5      10280759.2      3550587.27     10280099.46
      3550163.66     10279613.35      3549594.23     10279175.86
#Sta/Elev= 30
  3887.6     345  3920.7  343.84  3947.7  341.09  3962.5  342.76  3998.2  343.49
  4048.5   345.3    4106  345.61  4149.2  344.37  4321.2  344.95  4472.3     341
  4633.7  341.04  4694.5  342.13  4899.3  339.08  4984.8  335.81  4991.4  335.27
    4996  333.53  4998.8  333.03    5002  333.53  5019.9  335.91  5076.9  337.29
  5097.8  339.07  5137.5  339.44  5232.6  341.29  5403.2  349.38  5538.2  352.96
  5824.7  358.62  5851.8  358.14  5916.1     360  6040.9  361.23  6061.8  361.24
#Mann= 7 ,-1 , 0
  3887.6     .16       0  3998.2     .05       0  4633.7     .16       0
    4996     .07       0    5002     .16       0  5137.5     .05       0
  6040.9      .1       0
Bank Sta=4984.8,5019.9
XS Rating Curve= 0 ,0
Exp/Cntr=0.3,0.1

Type RM Length L Ch R = 1 ,58459   ,148,148,148
BEGIN DESCRIPTION:
Mapping XS 11d24d08
END DESCRIPTION:
XS GIS Cut Line= 2
      3551521.95     10280440.57      3550174.18      10278922.4
#Sta/Elev= 30
  3863.6  346.76  4040.6   344.5  4302.2  341.19  4365.8  340.06  4400.9  338.11
  4429.3  339.42  4478.7  339.35  4500.4  337.39  4570.9   340.2  4727.1  338.65
  4752.7  339.39  4894.3  337.23  4895.1  337.19  4939.5  334.52  4974.6  334.63
  4988.8  333.56  4993.3  331.85  4996.1  331.35  4999.3  331.85    5003  333.41
  5024.8     335  5030.4   334.8  5037.5  335.16  5166.6  338.46  5179.9  338.67
  5215.4  340.54  5302.7  342.19  5421.2  344.64  5619.4  351.07  5893.7  350.85
#Mann= 12 ,-1 , 0
  3863.6     .05       0  4040.6     .16       0  4752.7      .1       0
  4894.3     .05       0  4895.1     .16       0  4993.3     .07       0
  4999.3     .16       0  5030.4     .05       0  5037.5     .16       0
  5166.6     .05       0  5179.9     .16       0  5302.7     .05       0
#XS Ineff= 2 , 0
         4623.58  340.51
Permanent Ineff=
       F       F
Bank Sta=4974.6,5024.8
XS Rating Curve= 0 ,0
Exp/Cntr=0.3,0.1

Type RM Length L Ch R = 1 ,58311   ,251,251,251
BEGIN DESCRIPTION:
Mapping XS 3b02a9b1
END DESCRIPTION:
XS GIS Cut Line= 2
      3551694.62     10280416.27      3550276.54     10278874.31
#Sta/Elev= 30
  3805.8  347.36  3994.8   344.4  4122.5  343.92  4533.6  339.48  4642.5  338.64
  4672.1  338.08  4782.4  337.18  4810.5  337.04  4922.3  337.24  4943.1  336.21
  4964.6  336.62  4978.8  334.69  4985.6  336.46    4990  332.43  4992.8  331.93
    4996  332.43  4999.8  336.68  5007.2   335.1    5014  336.48  5070.7  337.19
  5091.7  336.36  5339.5  340.78  5473.9  344.78  5481.3  345.76  5530.6  345.93
  5587.3  348.36  5779.9  349.27  5884.5  348.59  5898.7  348.76  5900.7  349.61
#Mann= 10 ,-1 , 0
  3805.8     .05       0  4533.6     .16       0  4642.5     .05       0
  4672.1     .16       0  4782.4     .05       0  4810.5      .1       0
  4922.3     .05       0    4990     .03       0    4996     .05       0
  5779.9      .1       0
Bank Sta=4985.6,4999.8
XS Rating Curve= 0 ,0
Exp/Cntr=0.3,0.1

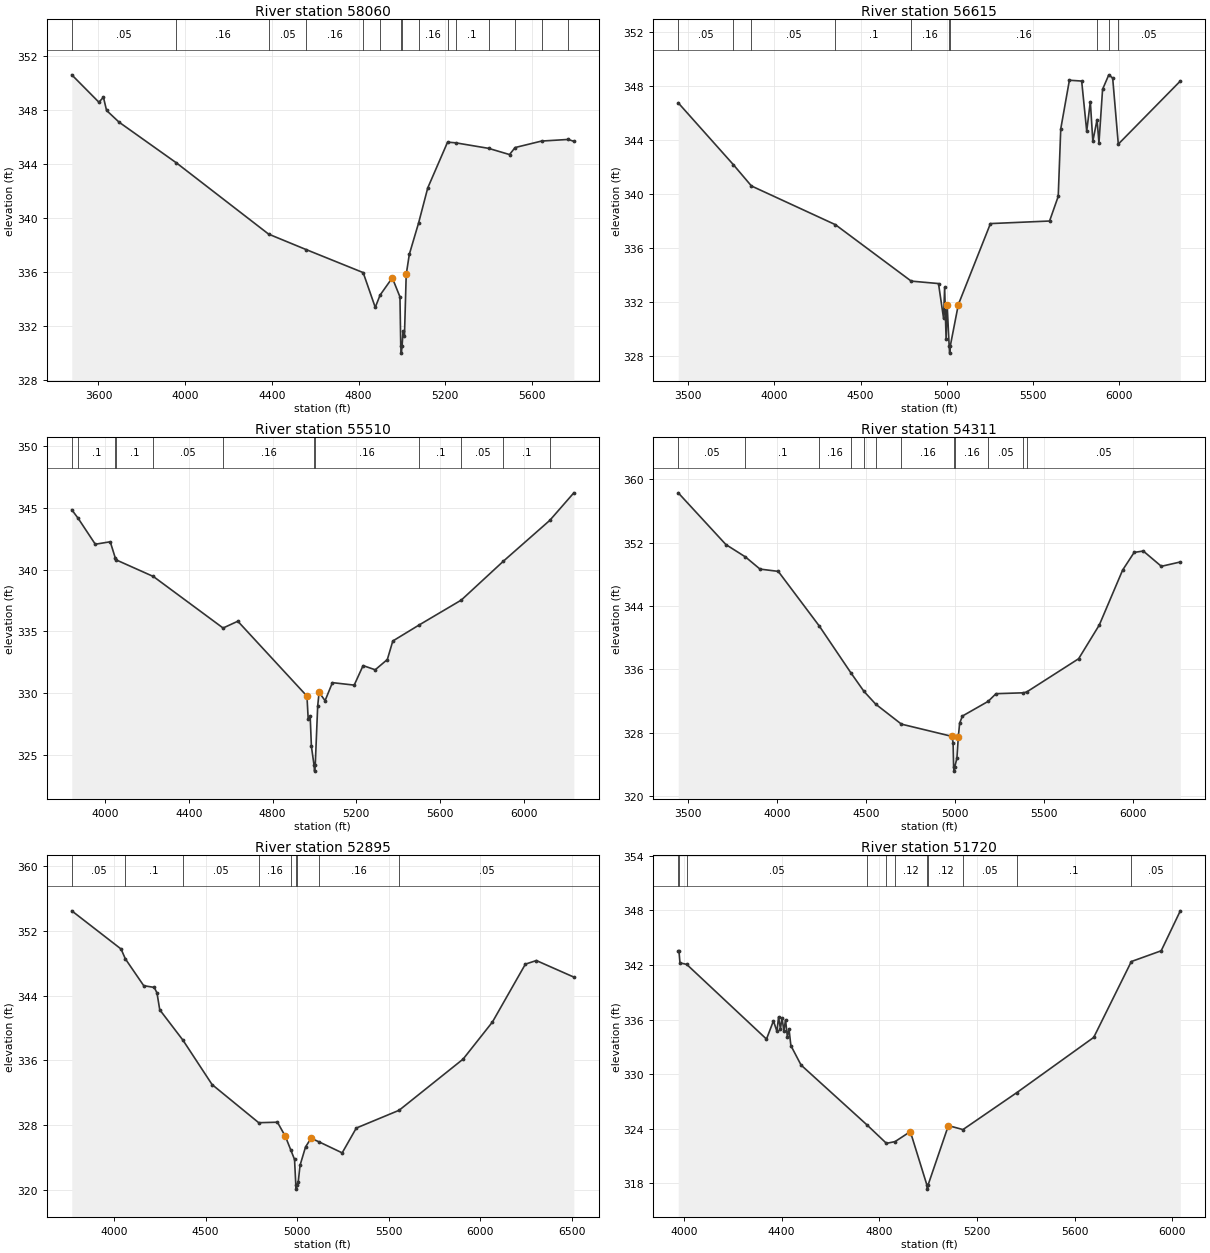
Type RM Length L Ch R = 1 ,58060   ,1445,1445,1445
BEGIN DESCRIPTION:
MATHIS CREEK 75.0
END DESCRIPTION:
XS GIS Cut Line= 3
      3551953.44     10280536.46      3550764.21     10279026.05
      3550456.18     10278780.69
#Sta/Elev= 30
    3477  350.59  3602.2  348.56  3623.1  348.93  3637.5  347.95  3695.3  347.08
    3960  344.06  4385.3  338.78  4557.6  337.64  4821.3  335.93  4877.1  333.35
  4899.2  334.26  4955.7  335.54    4991  334.13  4994.7  330.46  4997.5  329.96
  5000.7  330.46  5005.4  331.61  5011.8  331.26  5019.9  335.79  5034.3  337.29
    5077  339.61  5119.3  342.21  5210.7   345.6    5248  345.55  5399.9  345.14
  5496.4  344.68  5522.3   345.2  5644.3  345.68  5767.1   345.8  5793.2  345.66
#Mann= 15 ,-1 , 0
    3477     .05       0    3960     .16       0  4385.3     .05       0
  4557.6     .16       0  4821.3      .1       0  4899.2     .12       0
  4994.7     .07       0  5000.7     .12       0    5077     .16       0
  5210.7     .05       0    5248      .1       0  5399.9     .05       0
  5522.3      .1       0  5644.3     .05       0  5767.1      .1       0
Bank Sta=4955.7,5019.9
XS Rating Curve= 0 ,0
Exp/Cntr=0.3,0.1

Type RM Length L Ch R = 1 ,56615   ,1105,1105,1105
BEGIN DESCRIPTION:
MATHIS CREEK 73.0
END DESCRIPTION:
XS GIS Cut Line= 3
      3552452.15     10280227.91      3552044.16     10279029.96
      3550716.57     10278058.13
#Sta/Elev= 30
  3442.6  346.73  3761.7  342.17  3866.9  340.59  4353.7  337.73  4793.3  333.56
  4951.5  333.38  4980.9  330.81  4987.1  333.09  4995.5  329.28  5001.7  331.79
  5013.4  328.74  5016.1  328.24  5019.4  328.74  5066.6  331.83  5252.6  337.81
  5595.4     338  5645.6  339.82  5660.3  344.81  5710.4   348.4  5781.5  348.34
  5810.8  344.64  5831.7  346.82  5846.3  343.89  5870.7  345.49  5881.8  343.77
  5902.7  347.73  5938.8   348.8  5961.3  348.56  5993.9  343.68  6353.4  348.34
#Mann= 10 ,-1 , 0
  3442.6     .05       0  3761.7      .1       0  3866.9     .05       0
  4353.7      .1       0  4793.3     .16       0  5013.4     .07       0
  5019.4     .16       0  5870.7     .05       0  5938.8      .1       0
  5993.9     .05       0
Bank Sta=5001.7,5066.6
XS Rating Curve= 0 ,0
Exp/Cntr=0.3,0.1

Type RM Length L Ch R = 1 ,55510   ,1199,1199,1199
BEGIN DESCRIPTION:
MATHIS CREEK 70.0
END DESCRIPTION:
XS GIS Cut Line= 4
      3553108.07     10278904.99       3552358.1     10278273.07
      3551885.88      10277981.4      3551042.09     10277791.64
#Sta/Elev= 30
  3839.5  344.85  3869.9  344.16    3952  342.06  4023.5  342.26  4047.7  340.94
  4049.6  340.81  4229.6  339.45    4563  335.28  4633.4  335.83    4964  329.77
  4969.9  327.92  4979.4  328.15  4985.3   325.7  4997.7   324.2  5000.4   323.7
  5003.7   324.2  5015.3  328.96    5022  330.08  5050.6   329.4  5085.8  330.86
  5189.9  330.66  5232.4  332.24  5290.3   331.9  5348.3  332.73  5374.5  334.23
  5501.7  335.54  5701.8  337.54  5903.3  340.69    6125  343.99  6240.1  346.22
#Mann= 12 ,-1 , 0
  3839.5     .16       0  3869.9      .1       0  4047.7     .16       0
  4049.6      .1       0  4229.6     .05       0    4563     .16       0
  4997.7     .07       0  5003.7     .16       0  5501.7      .1       0
  5701.8     .05       0  5903.3      .1       0    6125     .05       0
Bank Sta=4964,5022
XS Rating Curve= 0 ,0
Exp/Cntr=0.3,0.1

Type RM Length L Ch R = 1 ,54311   ,1416,1416,1416
BEGIN DESCRIPTION:
MATHIS CREEK 68.0
END DESCRIPTION:
XS GIS Cut Line= 3
      3553797.61     10277736.55      3552903.53     10277623.71
      3551271.56     10276616.75
#Sta/Elev= 30
  3446.8   358.3  3714.4  351.76  3823.9   350.2  3905.9  348.66  4008.4  348.37
  4239.5  341.44    4416  335.55  4489.6   333.2  4555.7  331.58  4699.8  329.06
  4984.1  327.51    4990  326.68  4992.9  323.62  4995.7  323.12  4998.9  323.62
  5011.2  324.73  5019.4  327.48  5026.6  329.16    5042  330.08  5186.8  331.94
  5230.9  332.91  5384.4  333.02  5403.4  333.13  5694.8  337.33  5810.7  341.59
  5941.9  348.54  6006.5  350.77  6057.8  350.94  6159.2  349.01  6265.6  349.56
#Mann= 12 ,-1 , 0
  3446.8     .05       0  3823.9      .1       0  4239.5     .16       0
    4416     .05       0  4489.6     .16       0  4555.7     .05       0
  4699.8     .16       0  4992.9     .07       0  4998.9     .16       0
  5186.8     .05       0  5384.4     .16       0  5403.4     .05       0
Bank Sta=4984.1,5019.4
XS Rating Curve= 0 ,0
Exp/Cntr=0.3,0.1

Type RM Length L Ch R = 1 ,52895   ,1175,1175,1175
BEGIN DESCRIPTION:
MATHIS CREEK 64.0
END DESCRIPTION:
XS GIS Cut Line= 3
      3553927.86     10276790.39      3553354.92     10276417.11
      3551297.65     10276321.62
#Sta/Elev= 30
    3769  354.45  4038.4  349.74  4061.5  348.54  4162.2  345.22  4219.5  345.01
  4234.6  344.33  4249.7  342.25  4376.9  338.49  4535.7  333.03  4790.4  328.33
  4892.7  328.39  4936.2  326.64  4965.4  324.98  4986.2   323.8  4993.2  320.64
    4996  320.14  4999.2  320.64  5006.2  320.97  5016.2  323.07  5046.3  325.34
  5076.3  326.41  5121.9  325.95  5246.5  324.61  5323.6  327.67  5557.5  329.86
  5907.2  336.17  6067.4  340.74  6247.6  347.88  6307.6  348.32  6512.3  346.28
#Mann= 9 ,-1 , 0
    3769     .05       0  4061.5      .1       0  4376.9     .05       0
  4790.4     .16       0  4965.4     .05       0  4993.2    .035       0
  4999.2     .05       0  5121.9     .16       0  5557.5     .05       0
Bank Sta=4936.2,5076.3
XS Rating Curve= 0 ,0
Exp/Cntr=0.3,0.1

Type RM Length L Ch R = 1 ,51720   ,529,529,529
BEGIN DESCRIPTION:
MATHIS CREEK 62.0
END DESCRIPTION:
XS GIS Cut Line= 3
      3553742.08     10276191.62      3552992.11     10275541.64
      3552192.14     10274841.68
#Sta/Elev= 30
  3976.6  343.51  3979.7  343.51  3983.7  342.24  4011.6  342.06  4337.9  333.86
  4366.4  335.86  4380.7  334.71  4387.3   336.3  4394.9     335  4401.5  336.18
  4409.2  334.74  4415.8  335.99  4423.4   334.1    4430  334.98  4437.7  333.15
  4479.4  331.01  4749.5  324.43  4828.9  322.41  4864.2   322.6  4926.8   323.7
    4994  317.88  4996.8  317.38    5000  317.88  5082.5  324.36  5142.2  323.92
  5362.6  327.98  5677.6  334.05  5831.5  342.38  5953.7  343.56    6032  347.95
#Mann= 11 ,-1 , 0
  3976.6     .05       0  3979.7      .1       0  4011.6     .05       0
  4749.5     .16       0  4828.9     .05       0  4864.2     .12       0
    4994     .07       0    5000     .12       0  5142.2     .05       0
  5362.6      .1       0  5831.5     .05       0
Bank Sta=4926.8,5082.5
XS Rating Curve= 0 ,0
Exp/Cntr=0.3,0.1

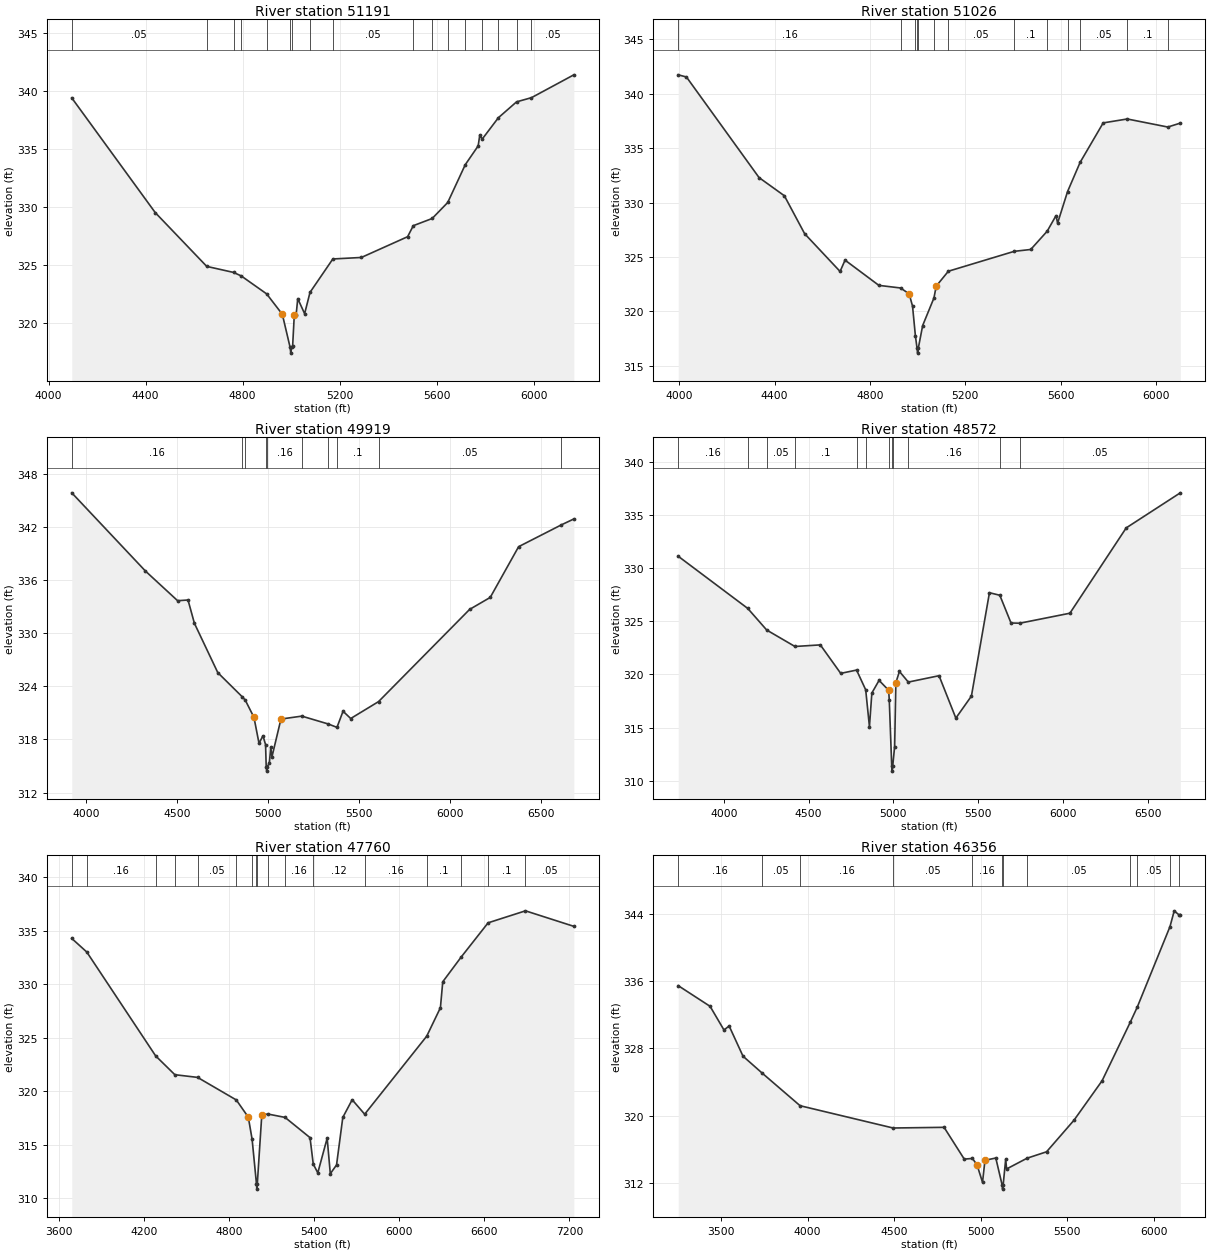
Type RM Length L Ch R = 1 ,51191   ,165,165,165
BEGIN DESCRIPTION:
MATHIS CREEK 61.0
END DESCRIPTION:
XS GIS Cut Line= 2
      3553745.57     10275844.22      3552366.24     10274300.06
#Sta/Elev= 30
  4095.7  339.44  4439.9  329.55  4652.3  324.91  4762.8  324.39  4794.3  324.09
  4899.3  322.54    4964  320.78  4996.1  317.93  4998.9  317.43  5002.1  317.93
  5006.6  318.07  5013.3   320.7  5020.9  320.72  5027.6  322.13    5056  320.83
  5078.2  322.67  5172.3  325.55    5290  325.68  5480.7  327.47  5504.1  328.42
  5581.9  329.04  5646.1  330.42  5718.4  333.68  5771.6   335.3  5778.3  336.23
    5788  335.88    5855  337.73    5930   339.1  5991.5  339.46  6166.2  341.43
#Mann= 17 ,-1 , 0
  4095.7     .05       0  4652.3     .16       0  4762.8     .05       0
  4794.3     .16       0  4899.3     .05       0  4996.1     .03       0
  5002.1     .05       0  5078.2     .16       0  5172.3     .05       0
  5504.1      .1       0  5581.9     .05       0  5646.1      .1       0
  5718.4     .05       0    5788      .1       0    5855     .05       0
    5930      .1       0  5991.5     .05       0
Bank Sta=4964,5013.3
XS Rating Curve= 0 ,0
Exp/Cntr=0.3,0.1

Type RM Length L Ch R = 1 ,51026   ,1107,1107,1107
BEGIN DESCRIPTION:
MATHIS CREEK 60.0
END DESCRIPTION:
XS GIS Cut Line= 2
      3553919.16     10275783.43      3552496.34     10274230.48
#Sta/Elev= 30
  3995.5  341.75    4030  341.55  4334.6   332.3  4440.7  330.63  4525.8  327.14
  4674.4  323.67  4695.3  324.71  4837.2  322.39  4928.1  322.15  4964.2  321.61
  4978.4  320.48  4990.3  317.77    4997  316.66  4999.7  316.16    5003  316.66
  5020.9   318.7  5068.2  321.23  5077.7  322.32  5128.6  323.69    5405  325.52
  5474.2  325.69  5543.2  327.37  5580.2   328.8    5587  328.12  5628.8  331.02
  5681.4   333.7  5778.2  337.33  5879.1  337.69  6049.2  336.95  6101.7  337.31
#Mann= 13 ,-1 , 0
  3995.5     .16       0  4928.1     .05       0  4990.3      .1       0
    4997     .07       0    5003      .1       0  5068.2     .16       0
  5128.6     .05       0    5405      .1       0  5543.2     .05       0
  5628.8      .1       0  5681.4     .05       0  5879.1      .1       0
  6049.2     .05       0
Bank Sta=4964.2,5077.7
XS Rating Curve= 0 ,0
Exp/Cntr=0.3,0.1

Type RM Length L Ch R = 1 ,49919   ,1347,1347,1347
BEGIN DESCRIPTION:
MATHIS CREEK 59.0
END DESCRIPTION:
XS GIS Cut Line= 2
      3554821.94     10275201.84      3552730.89     10273405.79
#Sta/Elev= 30
  3922.7  345.84  4327.1  337.01  4503.8  333.66  4560.9  333.74    4596  331.11
  4724.4  325.54  4857.2  322.84  4875.1  322.44    4923  320.49  4950.7  317.56
  4972.4  318.41  4986.7  317.41  4990.2  314.92    4993  314.42  4996.2  314.92
  5007.5  315.35  5015.2  317.11  5021.8  316.04  5071.2   320.3  5185.6  320.63
  5331.3  319.74  5378.7  319.36  5412.1  321.18  5454.2  320.36  5607.1  322.27
  6107.1  332.68  6220.1  334.03    6376  339.76  6610.4  342.22  6679.2  342.89
#Mann= 10 ,-1 , 0
  3922.7     .16       0  4857.2     .05       0  4875.1     .16       0
  4990.2     .07       0  4996.2     .16       0  5185.6      .1       0
  5331.3     .16       0  5378.7      .1       0  5607.1     .05       0
  6610.4      .1       0
Bank Sta=4923,5071.2
XS Rating Curve= 0 ,0
Exp/Cntr=0.3,0.1

Type RM Length L Ch R = 1 ,48572   ,812,812,812
BEGIN DESCRIPTION:
MATHIS CREEK 56.0
END DESCRIPTION:
XS GIS Cut Line= 3
        3555282.     10274516.07      3553788.95     10272910.16
      3553025.01     10272996.97
#Sta/Elev= 30
  3731.6  331.12  4141.8  326.21  4253.4  324.18    4420  322.63  4569.8  322.78
    4690   320.1  4783.6  320.41  4837.4  318.55  4859.5  315.08  4873.7  318.25
  4916.2  319.44  4972.9  318.51  4976.5  317.56  4990.9   311.4  4993.6   310.9
  4996.9   311.4  5008.1  313.21  5015.4  319.23  5036.4  320.28  5088.8  319.28
    5270  319.88  5369.2  315.89    5461  317.96  5567.3  327.69  5628.5  327.45
  5694.6  324.84  5746.3  324.82  6041.9  325.76  6374.1  333.79  6693.2  337.09
#Mann= 12 ,-1 , 0
  3731.6     .16       0  4141.8      .1       0  4253.4     .05       0
    4420      .1       0  4783.6     .05       0  4837.4     .16       0
  4976.5     .12       0  4990.9     .07       0  4996.9     .12       0
  5088.8     .16       0  5628.5      .1       0  5746.3     .05       0
Bank Sta=4972.9,5015.4
XS Rating Curve= 0 ,0
Exp/Cntr=0.3,0.1

Type RM Length L Ch R = 1 ,47760   ,1404,1404,1404
BEGIN DESCRIPTION:
MATHIS CREEK 55.0
END DESCRIPTION:
XS GIS Cut Line= 2
      3555577.15      10274377.2      3553928.65     10271245.04
#Sta/Elev= 30
  3691.6  334.27  3797.5     333  4282.8   323.3  4418.3  321.54  4578.3  321.29
  4851.6  319.18  4936.2  317.57    4963   315.5  4993.6  311.35  4996.4  310.85
  4999.6  311.35  5031.3  317.81  5076.4  317.86  5195.3  317.55  5371.2  315.66
  5394.1  313.19    5426  312.37  5492.1  315.61  5514.2  312.29  5558.2  313.11
  5602.3  317.55  5668.4   319.2  5756.5  317.85    6194  325.14  6290.5   327.8
  6306.9  330.22  6436.7  332.53  6626.7  335.73  6890.1  336.85  7231.1   335.4
#Mann= 17 ,-1 , 0
  3691.6      .1       0  3797.5     .16       0  4282.8     .05       0
  4418.3      .1       0  4578.3     .05       0  4851.6     .12       0
    4963     .16       0  4993.6     .07       0  4999.6     .16       0
  5076.4     .12       0  5195.3     .16       0  5394.1     .12       0
  5756.5     .16       0    6194      .1       0  6436.7     .16       0
  6626.7      .1       0  6890.1     .05       0
#XS Ineff= 2 , 0
                         5670.45          319.12
Permanent Ineff=
       F       F
Bank Sta=4936.2,5031.3
XS Rating Curve= 0 ,0
Exp/Cntr=0.3,0.1

Type RM Length L Ch R = 1 ,46356   ,2187,2187,2187
BEGIN DESCRIPTION:
MATHIS CREEK 53.0
END DESCRIPTION:
XS GIS Cut Line= 4
      3555828.88     10274125.43      3555861.25     10273537.37
       3555195.2      10271599.4       3554996.8     10271426.88
#Sta/Elev= 30
  3252.6  335.46  3436.7     333  3516.8  330.19  3546.8  330.66  3626.9  327.07
  3738.1  325.05  3956.7  321.18  4494.1  318.53  4788.7  318.61  4905.3  314.83
  4952.6  314.91    4979  314.15  5010.8  312.07    5025  314.69  5087.5  314.96
  5124.1  311.76  5126.8  311.26  5130.1  311.76  5144.7  314.81    5150  313.66
  5268.5  314.94  5380.9   315.7  5539.5  319.46  5701.8  324.15  5864.3   331.1
    5905  332.91    6094  342.48  6118.6  344.36  6147.6  343.85  6153.7  343.91
#Mann= 12 ,-1 , 0
  3252.6     .16       0  3738.1     .05       0  3956.7     .16       0
  4494.1     .05       0  4952.6     .16       0  5124.1     .07       0
  5130.1     .16       0  5268.5     .05       0  5864.3     .16       0
    5905     .05       0    6094      .1       0  6147.6     .05       0
Bank Sta=4979,5025
XS Rating Curve= 0 ,0
Exp/Cntr=0.3,0.1

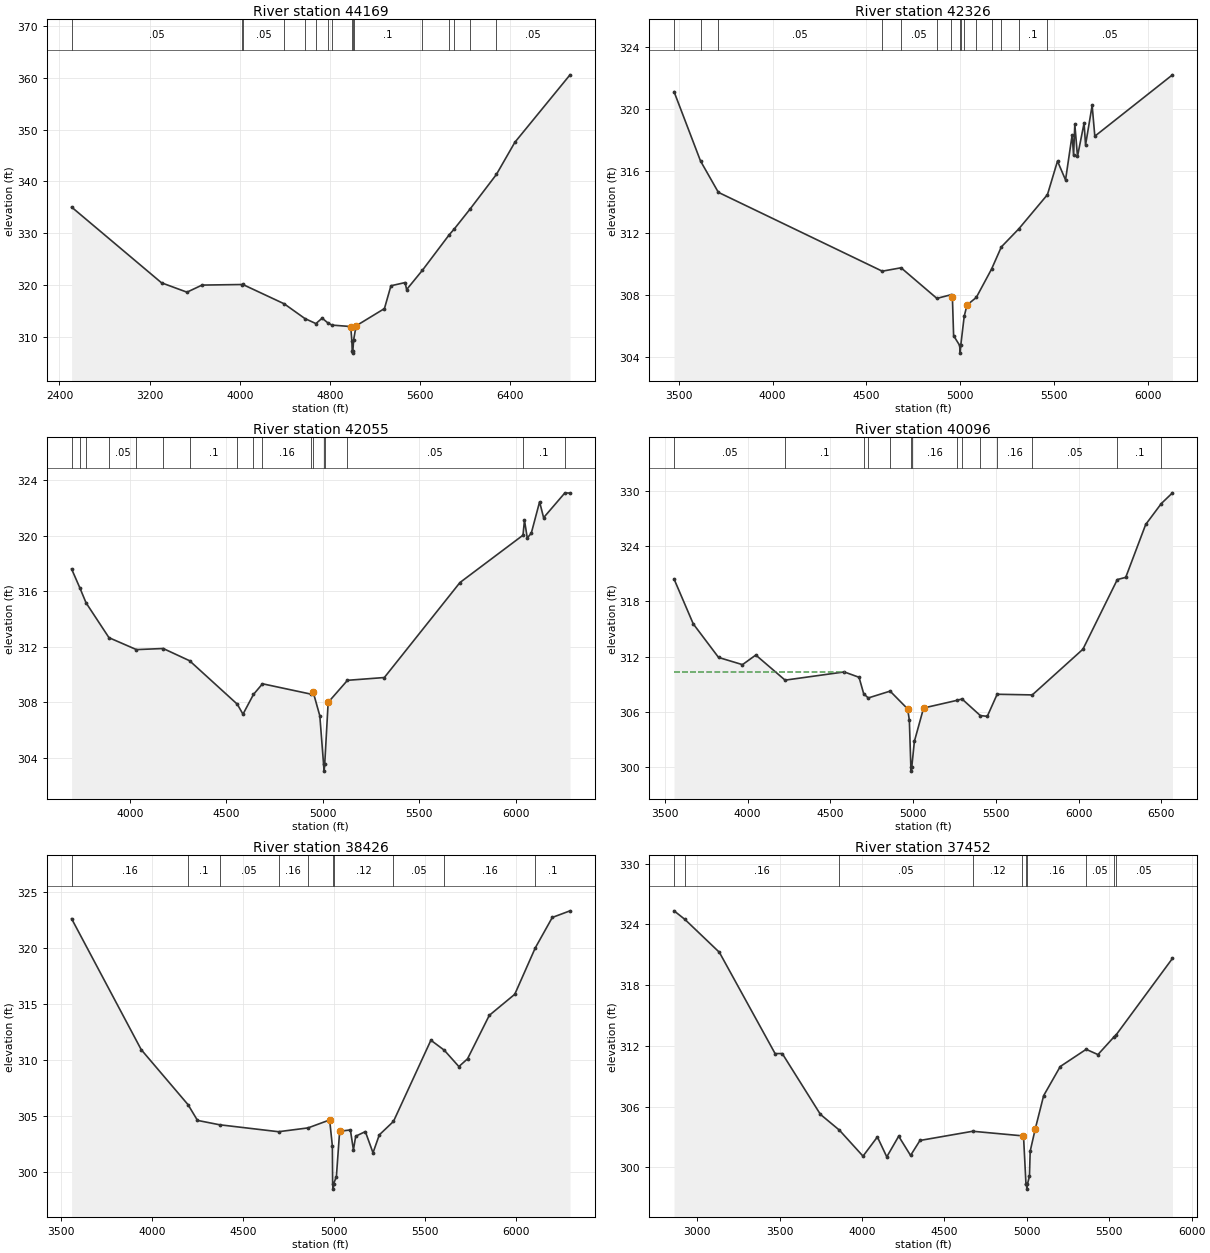
Type RM Length L Ch R = 1 ,44169   ,1843,1843,1843
BEGIN DESCRIPTION:
MATHIS CREEK 52.0
END DESCRIPTION:
XS GIS Cut Line= 4
       3556401.8     10274229.58      3556740.34     10272753.91
      3556054.57     10270722.66      3555386.65     10270349.67
#Sta/Elev= 30
  2507.7  335.02  3305.8  320.38  3531.6  318.57  3664.9  319.94  4015.6  320.05
  4024.8  320.08  4394.5  316.32  4577.6  313.48  4675.6   312.5  4731.2  313.55
  4780.7  312.65  4816.9  312.21  4984.6  311.93  4995.1  309.05  4997.7  307.29
  5000.4  306.79  5003.7  307.29  5010.5  309.34  5032.1  312.06  5283.8   315.4
  5341.5  319.81  5467.3  320.43  5480.6  319.07  5621.3  322.82  5857.3  329.63
  5903.8   330.8  6041.6  334.58  6277.2  341.32  6441.1  347.54  6930.6  360.58
#Mann= 16 ,-1 , 0
  2507.7     .05       0  4015.6      .1       0  4024.8     .05       0
  4394.5     .16       0  4577.6     .05       0  4675.6     .16       0
  4780.7      .1       0  4816.9     .16       0  4997.7     .07       0
  5003.7     .16       0  5010.5      .1       0  5621.3     .05       0
  5857.3      .1       0  5903.8     .05       0  6041.6      .1       0
  6277.2     .05       0
Bank Sta=4984.6,5032.1
XS Rating Curve= 0 ,0
Exp/Cntr=0.3,0.1

Type RM Length L Ch R = 1 ,42326   ,271,271,271
BEGIN DESCRIPTION:
MATHIS CREEK 51.0
END DESCRIPTION:
XS GIS Cut Line= 2
      3558761.55      10273111.8      3557039.36     10271091.01
#Sta/Elev= 30
  3475.5  321.14  3616.4  316.66  3711.5  314.63  4584.6  309.53  4684.8  309.75
  4875.6  307.77  4951.9  308.01  4958.1  307.89  4964.7  305.36  4996.8  304.73
  4999.6  304.23  5002.8  304.73  5021.1  306.61  5036.1  307.34  5085.5  307.83
  5166.6  309.66    5219   311.1  5312.1  312.27  5464.5  314.48  5518.1  316.65
  5560.9  315.43  5596.1  318.34  5603.8  317.02  5610.3  319.04  5624.6  316.95
  5659.7  319.11  5667.5  317.69  5702.6  320.25  5716.9  318.26  6130.6  322.23
#Mann= 15 ,-1 , 0
  3475.5     .05       0  3616.4      .1       0  3711.5     .05       0
  4584.6     .16       0  4684.8     .05       0  4875.6     .16       0
  4951.9     .05       0  4996.8     .04       0  5002.8     .05       0
  5021.1     .16       0  5085.5     .05       0  5166.6      .1       0
    5219     .05       0  5312.1      .1       0  5464.5     .05       0
Bank Sta=4958.1,5036.1
XS Rating Curve= 0 ,0
Exp/Cntr=0.3,0.1

Type RM Length L Ch R = 1 ,42055   ,1959,1959,1959
BEGIN DESCRIPTION:
MATHIS CREEK 50.0
END DESCRIPTION:
XS GIS Cut Line= 2
      3558833.49     10272969.17      3557209.24     10270962.57
#Sta/Elev= 30
  3698.6  317.61  3742.5  316.21  3773.5  315.17  3892.2  312.66  4034.6   311.8
  4173.2  311.88  4309.6     311  4556.8  307.87  4586.3  307.15  4640.5  308.57
  4687.4  309.34  4939.8  308.59  4948.5  308.75  4949.2  308.78  4984.3  307.03
  5003.7  303.55  5006.4  303.05  5009.7  303.55  5027.5     308  5127.6  309.59
  5318.5  309.79  5710.1  316.63  6036.7  320.04  6044.3  321.12  6058.7  319.84
  6079.5  320.18  6122.6  322.44  6143.4   321.3  6253.9  323.09  6280.2  323.07
#Mann= 17 ,-1 , 0
  3698.6      .1       0  3742.5     .05       0  3773.5      .1       0
  3892.2     .05       0  4034.6      .1       0  4173.2     .05       0
  4309.6      .1       0  4556.8     .16       0  4640.5     .05       0
  4687.4     .16       0  4939.8     .05       0  4948.5     .16       0
  5003.7     .07       0  5009.7     .16       0  5127.6     .05       0
  6036.7      .1       0  6253.9     .05       0
Bank Sta=4949.2,5027.5
XS Rating Curve= 0 ,0
Exp/Cntr=0.3,0.1

Type RM Length L Ch R = 1 ,40096   ,1670,1670,1670
BEGIN DESCRIPTION:
MATHIS CREEK 49.0
END DESCRIPTION:
XS GIS Cut Line= 3
      3558992.11     10272991.64      3558667.54     10270502.46
      3558268.23     10270198.64
#Sta/Elev= 30
  3555.3  320.42  3671.3  315.56  3824.3  311.92  3968.8  311.14  4049.4  312.18
  4226.3  309.46  4583.9  310.35  4673.2  309.77  4701.4  307.98  4728.9  307.53
  4860.9  308.27  4967.1  306.34  4977.2  305.11  4986.2   300.1    4989   299.6
  4992.2   300.1  5007.5  302.82  5063.2  306.44    5265  307.27  5295.4  307.42
  5406.1  305.62  5448.2  305.54  5507.7  307.93    5720  307.86    6026  312.81
  6233.9  320.36  6284.8   320.6  6405.4  326.33  6499.9   328.6  6567.3  329.76
#Mann= 14 ,-1 , 0
  3555.3     .05       0  4226.3      .1       0  4701.4     .16       0
  4728.9     .05       0  4860.9     .16       0  4986.2     .07       0
  4992.2     .16       0    5265     .05       0  5295.4     .16       0
  5406.1     .12       0  5507.7     .16       0    5720     .05       0
  6233.9      .1       0  6499.9     .05       0
#XS Ineff= 2 , 0
          4585.8  310.38
Permanent Ineff=
       F       F
Bank Sta=4967.1,5063.2
XS Rating Curve= 0 ,0
Exp/Cntr=0.3,0.1

Type RM Length L Ch R = 1 ,38426   ,974,974,974
BEGIN DESCRIPTION:
MATHIS CREEK 47.0
END DESCRIPTION:
XS GIS Cut Line= 3
      3561092.11     10271541.64      3559892.11     10270741.64
      3558692.13     10270241.65
#Sta/Elev= 30
  3556.9  322.63    3940  310.95  4197.7  306.04  4249.5  304.64  4370.9  304.25
  4695.5  303.63  4857.6  303.97  4976.6  304.68  4991.6  302.36  4993.1  299.01
  4995.9  298.51  4999.1  299.01  5013.7  299.62  5031.6  303.67  5090.7  303.79
  5107.5  302.01  5119.9  303.23    5173  303.64  5215.2  301.75  5249.9  303.35
  5327.8  304.55  5533.7  311.79  5607.3   310.9  5687.6  309.44  5735.2  310.13
    5855  314.01  5995.2  315.89  6108.1  320.03  6201.6  322.74  6299.1  323.33
#Mann= 10 ,-1 , 0
  3556.9     .16       0  4197.7      .1       0  4370.9     .05       0
  4695.5     .16       0  4857.6     .12       0  4993.1     .07       0
  4999.1     .12       0  5327.8     .05       0  5607.3     .16       0
  6108.1      .1       0
Bank Sta=4976.6,5031.6
XS Rating Curve= 0 ,0
Exp/Cntr=0.3,0.1

Type RM Length L Ch R = 1 ,37452   ,2098,2098,2098
BEGIN DESCRIPTION:
MATHIS CREEK 45.0
END DESCRIPTION:
XS GIS Cut Line= 3
      3561742.07     10271291.62      3559942.11     10270091.64
      3559242.12     10269591.65
#Sta/Elev= 30
  2860.2  325.35  2925.5  324.51  3135.1  321.25  3473.1  311.24  3516.7  311.24
    3748  305.23  3863.2  303.67  4006.4   301.1  4093.6     303  4150.6  301.03
  4222.8  303.07  4294.9  301.17  4351.9  302.65  4671.8  303.56  4971.5  303.11
  4979.9  303.14  4994.9  298.36  4997.9  298.34  5000.7  297.84  5003.9  298.34
    5016  299.09  5020.5  301.59  5051.7  303.82  5102.1  307.08  5202.9  309.96
  5360.1  311.66  5431.5  311.14  5530.7  312.92  5539.2  313.03  5883.7  320.65
#Mann= 10 ,-1 , 0
  2860.2     .05       0  2925.5     .16       0  3863.2     .05       0
  4671.8     .12       0  4971.5     .16       0  4997.9     .07       0
  5003.9     .16       0  5360.1     .05       0  5530.7      .1       0
  5539.2     .05       0
Bank Sta=4979.9,5051.7
XS Rating Curve= 0 ,0
Exp/Cntr=0.3,0.1