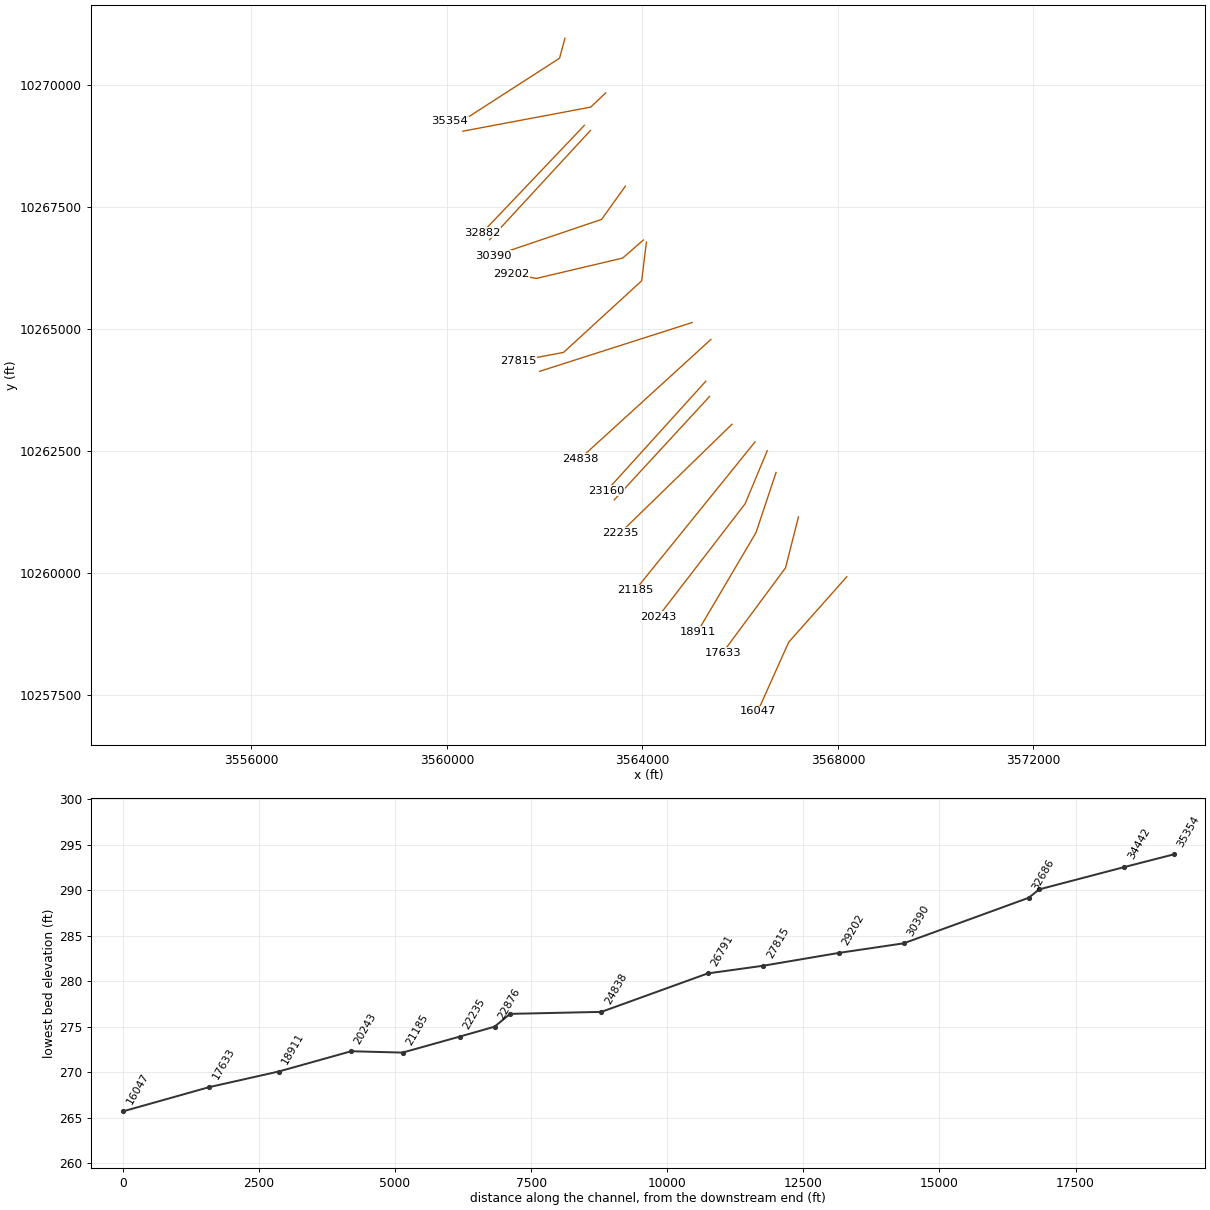
HEC-RAS study MATHIS CREEK.prj: MATHIS CREEK Base Level Engineering

--- MATHIS CREEK.g01 (geometry) --- (continued)

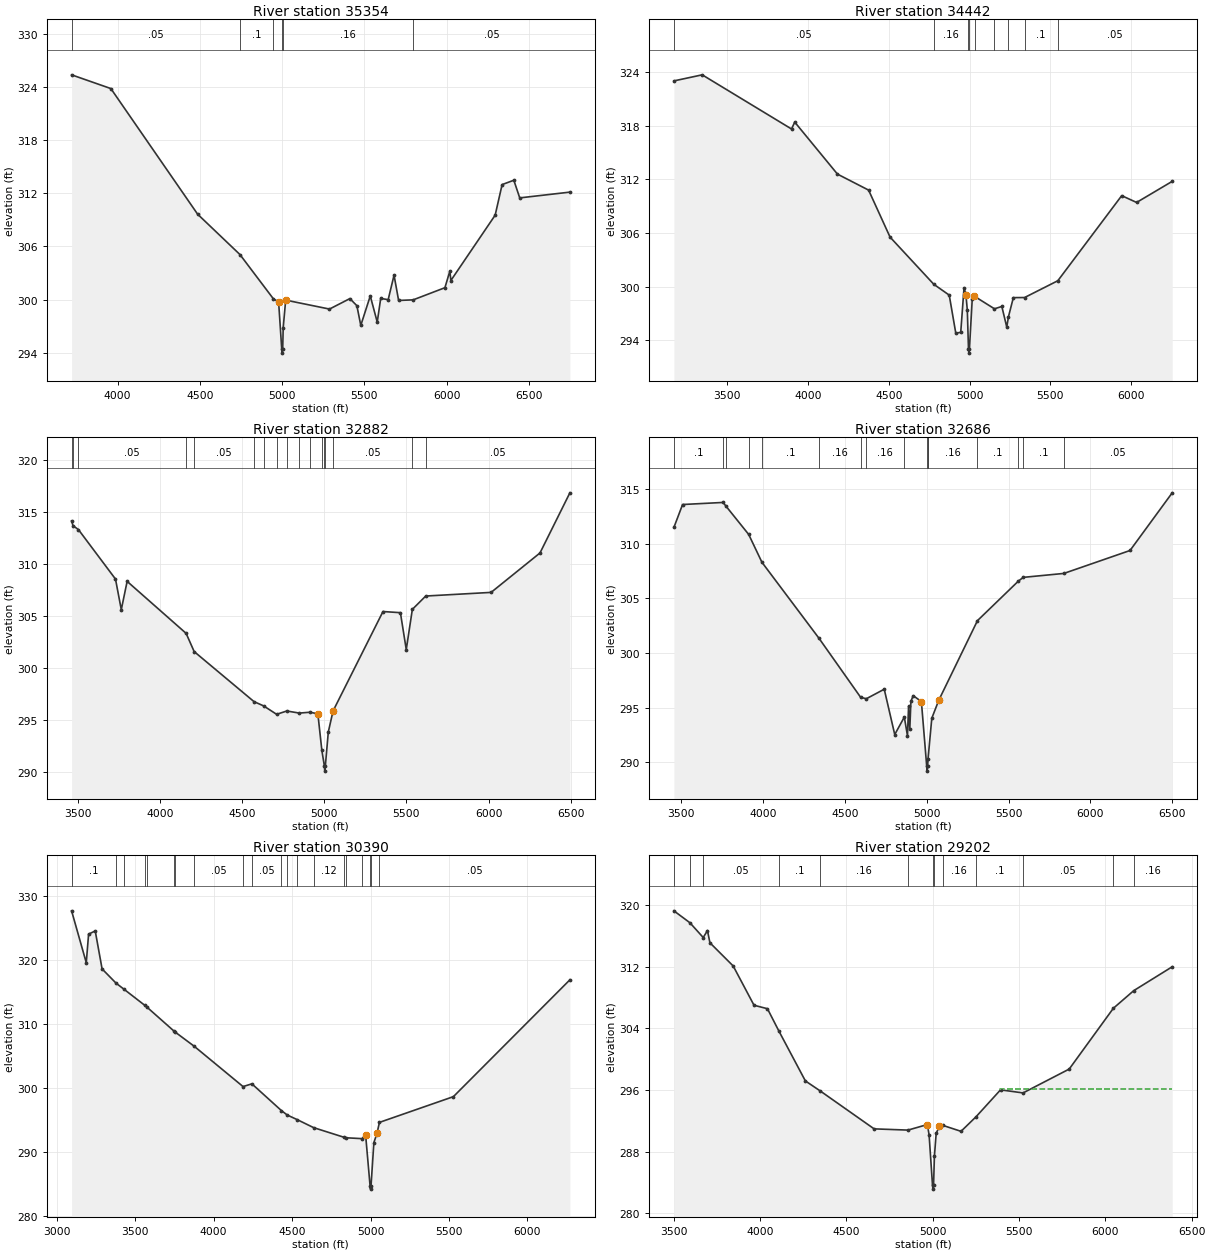
Type RM Length L Ch R = 1 ,35354   ,912,912,912
BEGIN DESCRIPTION:
MATHIS CREEK 44.0
END DESCRIPTION:
XS GIS Cut Line= 4
      3562414.37     10270952.16      3562303.25     10270542.39
      3560449.08     10269347.95      3560060.18     10269257.67
#Sta/Elev= 30
  3719.9  325.35  3958.7   323.8  4486.2  309.63  4743.4  305.08  4947.3  300.07
  4978.5  299.76  4997.4  294.46  5000.2  293.96  5003.4  294.46  5006.4  296.82
  5021.5  299.94  5287.8  298.93  5411.7  300.11  5454.3  299.31  5478.1  297.09
  5535.8  300.41  5578.1  297.46  5599.2  300.13  5644.6  299.99  5680.3  302.75
  5708.1   299.9  5796.7  299.97  5989.6  301.34  6019.7  303.22  6025.7  302.15
    6295  309.52  6337.3  312.97  6408.5  313.46  6444.4  311.47  6749.3  312.12
#Mann= 6 ,-1 , 0
  3719.9     .05       0  4743.4      .1       0  4947.3     .16       0
  4997.4     .07       0  5003.4     .16       0  5796.7     .05       0
Bank Sta=4978.5,5021.5
XS Rating Curve= 0 ,0
Exp/Cntr=0.3,0.1

Type RM Length L Ch R = 1 ,34442   ,1560,1560,1560
BEGIN DESCRIPTION:
MATHIS CREEK 41.0
END DESCRIPTION:
XS GIS Cut Line= 3
       3563247.7     10269834.06      3562942.14     10269542.39
      3560325.55     10269049.61
#Sta/Elev= 30
  3169.5  323.02  3344.8   323.7  3897.7  317.64  3917.6  318.41  4182.1  312.59
  4374.9   310.8  4507.8  305.54  4778.7  300.26  4874.1  299.05  4914.7  294.79
  4945.3  294.89  4965.7  299.88  4977.4  299.09    4986  297.38  4993.2  293.06
    4996  292.56  4999.2  293.06  5016.6  298.65  5024.7  298.95  5033.9  298.88
    5154  297.52  5199.7  297.78  5230.3  295.47  5240.7  296.63    5271  298.77
  5340.5  298.78  5546.4  300.66  5941.9  310.18  6034.1  309.42  6254.5  311.78
#Mann= 9 ,-1 , 0
  3169.5     .05       0  4778.7     .16       0  4993.2     .07       0
  4999.2     .16       0  5033.9     .05       0    5154     .16       0
  5240.7     .05       0  5340.5      .1       0  5546.4     .05       0
Bank Sta=4977.4,5024.7
XS Rating Curve= 0 ,0
Exp/Cntr=0.3,0.1

Type RM Length L Ch R = 1 ,32882   ,196,196,196
BEGIN DESCRIPTION:
MATHIS CREEK 39.0
END DESCRIPTION:
XS GIS Cut Line= 2
      3562811.98     10269169.31      3560723.53     10266973.06
#Sta/Elev= 30
    3464  314.16  3472.7   313.7  3505.5  313.33  3731.1  308.57  3766.3  305.63
  3801.9  308.35  4160.7  303.35  4209.6   301.6  4573.5  296.79  4632.1  296.38
  4711.1  295.57    4773  295.89  4848.7  295.69  4913.8  295.77  4961.9  295.62
  4986.2   292.1  5001.4  290.61  5004.1  290.11  5007.4  290.61  5025.4  293.87
  5053.7  295.85  5054.6   295.9  5357.9  305.45  5463.9  305.34  5499.5   301.8
  5536.6  305.66    5618  306.94  6015.6  307.29  6312.9  311.08  6494.7  316.86
#Mann= 17 ,-1 , 0
    3464     .05       0  3472.7      .1       0  3505.5     .05       0
  4160.7      .1       0  4209.6     .05       0  4573.5     .16       0
  4632.1     .05       0  4711.1     .16       0    4773     .05       0
  4848.7     .12       0  4913.8     .05       0  4986.2      .1       0
  5001.4     .07       0  5007.4      .1       0  5054.6     .05       0
  5536.6      .1       0    5618     .05       0
Bank Sta=4961.9,5053.7
XS Rating Curve= 0 ,0
Exp/Cntr=0.3,0.1

Type RM Length L Ch R = 1 ,32686   ,2296,2296,2296
BEGIN DESCRIPTION:
MATHIS CREEK 38.0
END DESCRIPTION:
XS GIS Cut Line= 2
      3562935.22     10269063.26      3560872.69     10266827.11
#Sta/Elev= 30
  3456.9  311.49  3509.9  313.59  3757.2  313.78  3773.8  313.46  3913.5  310.85
  3994.4   308.3  4343.3  301.33  4597.3  295.93    4632  295.81    4741  296.68
  4805.1  292.53  4863.6  294.13  4882.8  292.42  4889.6  295.11    4897     293
  4903.8  295.57  4917.9  296.09  4967.8  295.55    5000  289.68  5002.7  289.18
    5006  289.68  5008.4  290.29  5031.3  294.02  5073.9  295.67  5310.2  302.96
    5560  306.58  5589.6  306.92  5837.4  307.28  6241.5  309.38    6499  314.66
#Mann= 16 ,-1 , 0
  3456.9      .1       0  3757.2     .05       0  3773.8      .1       0
  3913.5     .05       0  3994.4      .1       0  4343.3     .16       0
  4597.3     .12       0    4632     .16       0  4863.6     .12       0
    5000     .07       0    5006     .12       0  5008.4     .16       0
  5310.2      .1       0    5560     .05       0  5589.6      .1       0
  5837.4     .05       0
Bank Sta=4967.8,5073.9
XS Rating Curve= 0 ,0
Exp/Cntr=0.3,0.1

Type RM Length L Ch R = 1 ,30390   ,1188,1188,1188
BEGIN DESCRIPTION:
MATHIS CREEK 35.0
END DESCRIPTION:
XS GIS Cut Line= 3
      3563650.45      10267924.3      3563164.36     10267243.78
      3560949.07     10266493.78
#Sta/Elev= 30
  3095.1  327.62  3188.7  319.52  3203.5  323.98  3245.8  324.48  3289.5  318.55
  3378.8  316.32  3426.3  315.43  3559.8   312.9  3575.1  312.59  3748.3  308.83
  3751.4  308.76  3875.7  306.49  4187.7  300.18  4243.9  300.61  4431.7  296.44
  4469.2  295.74  4534.5     295  4637.4  293.77    4833  292.25  4843.2  292.19
  4946.1  292.05  4968.4  292.69  4997.1  284.67  4999.8  284.17  5003.1  284.67
  5021.2  291.43  5041.1  292.88  5056.7  294.59    5528  298.61  6270.2  316.85
#Mann= 20 ,-1 , 0
  3095.1      .1       0  3378.8     .05       0  3426.3      .1       0
  3559.8     .16       0  3575.1      .1       0  3748.3     .16       0
  3751.4      .1       0  3875.7     .05       0  4187.7      .1       0
  4243.9     .05       0  4431.7     .16       0  4469.2      .1       0
  4534.5     .16       0  4637.4     .12       0    4833     .16       0
  4843.2     .12       0  4946.1     .16       0  4997.1     .07       0
  5003.1     .16       0  5056.7     .05       0
Bank Sta=4968.4,5041.1
XS Rating Curve= 0 ,0
Exp/Cntr=0.3,0.1

Type RM Length L Ch R = 1 ,29202   ,1387,1387,1387
BEGIN DESCRIPTION:
MATHIS CREEK 33.0
END DESCRIPTION:
XS GIS Cut Line= 4
      3564018.52     10266820.16      3563594.92     10266452.12
      3561831.03     10266035.45      3561325.57     10266125.46
#Sta/Elev= 30
  3500.3  319.28  3593.1  317.73  3670.2  315.81  3694.8  316.72    3709  315.13
  3843.9  312.11  3964.5  307.01  4042.3  306.56  4108.3  303.67    4262  297.18
  4347.2  295.89  4660.3  290.95  4856.3  290.79  4968.6  291.51  4978.8  290.17
  4998.6  283.62  5001.4  283.12  5004.6  283.62  5009.7  287.43  5019.9  290.37
  5038.8   291.3  5057.3  291.41  5163.8  290.63  5251.1  292.53  5392.6  296.02
  5523.2  295.62  5790.6  298.72  6046.4  306.62  6164.5  308.91  6387.3  312.01
#Mann= 13 ,-1 , 0
  3500.3     .05       0  3593.1      .1       0  3670.2     .05       0
  4108.3      .1       0  4347.2     .16       0  4856.3     .12       0
  4998.6     .07       0  5004.6     .12       0  5057.3     .16       0
  5251.1      .1       0  5523.2     .05       0  6046.4      .1       0
  6164.5     .16       0
#XS Ineff= 2 , 0
                         5390.34          296.07
Permanent Ineff=
       F       F
Bank Sta=4968.6,5038.8
XS Rating Curve= 0 ,0
Exp/Cntr=0.3,0.1

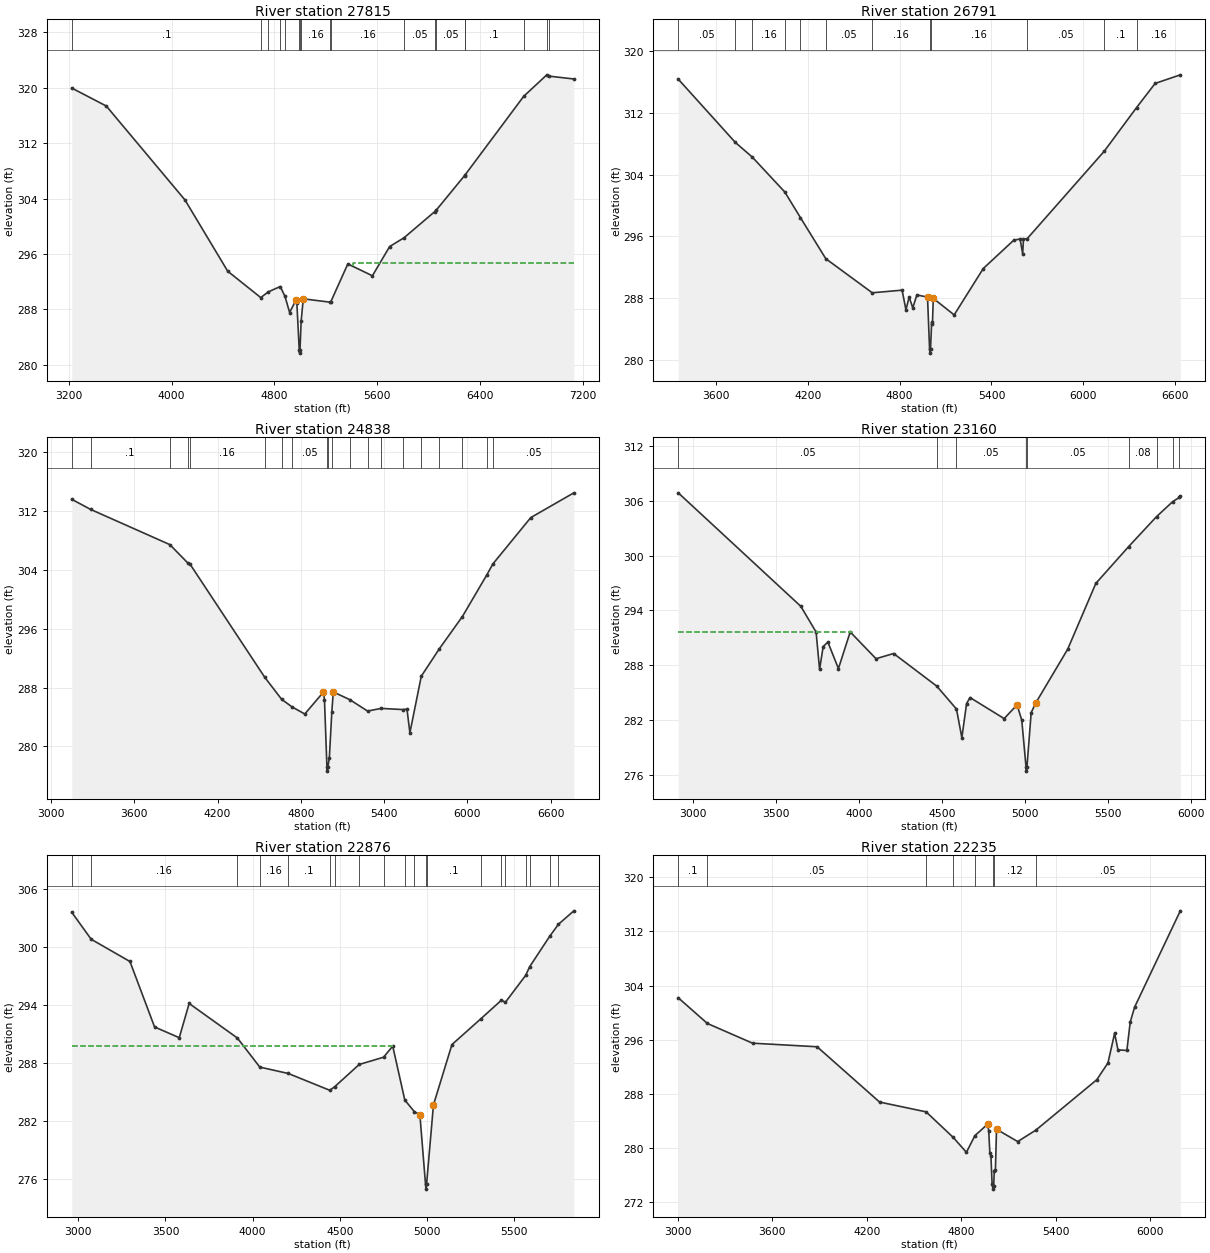
Type RM Length L Ch R = 1 ,27815   ,1024,1024,1024
BEGIN DESCRIPTION:
MATHIS CREEK 30.0
END DESCRIPTION:
XS GIS Cut Line= 4
      3564081.02     10266778.47      3563983.81     10265986.84
       3562385.1     10264520.31      3561463.02     10264347.96
#Sta/Elev= 30
  3223.5  319.92  3492.3  317.33  4104.1  303.79  4436.4  293.52  4693.3  289.72
  4752.9  290.55  4845.1  291.31  4882.2  289.88    4918  287.56  4967.3  289.37
  4974.1  288.96  4992.7  282.21  4995.4  281.71  4998.7  282.21  5007.6  286.33
  5024.1  289.54  5235.1  289.05  5238.4  289.12  5370.6  294.57  5561.7  292.86
  5696.2  297.08  5807.8  298.34  6046.1   302.1  6059.9  302.36  6278.6   307.3
  6280.2  307.34  6738.5  318.73  6918.4  321.83  6936.2  321.64  7128.6  321.23
#Mann= 18 ,-1 , 0
  3223.5      .1       0  4693.3     .16       0  4752.9     .12       0
  4845.1     .16       0  4882.2     .12       0  4992.7     .07       0
  4998.7     .12       0  5007.6     .16       0  5235.1     .05       0
  5238.4     .16       0  5807.8     .05       0  6046.1     .16       0
  6059.9     .05       0  6278.6     .16       0  6280.2      .1       0
  6738.5     .16       0  6918.4      .1       0  6936.2     .16       0
#XS Ineff= 2 , 0
                         5411.93          294.77
Permanent Ineff=
       F       F
Bank Sta=4967.3,5024.1
XS Rating Curve= 0 ,0
Exp/Cntr=0.3,0.1

Type RM Length L Ch R = 1 ,26791   ,1953,1953,1953
BEGIN DESCRIPTION:
MATHIS CREEK 29.0
END DESCRIPTION:
XS GIS Cut Line= 2
      3565018.55     10265132.68      3561895.27     10264133.23
#Sta/Elev= 30
  3354.3  316.41  3727.7  308.19  3838.3  306.29  4050.2  301.77  4152.5  298.44
  4318.2  293.11  4621.4  288.69  4816.5  289.03  4841.5  286.48  4862.5  288.14
  4886.1  286.74    4913  288.41  4982.5  288.13    4996  281.36  4998.7  280.86
    5002  281.36  5009.5  284.88  5014.7   284.7    5020  287.97  5156.5  285.82
  5346.7  291.84    5545   295.5    5587  295.68    5604  293.75  5609.2  295.68
  5632.9   295.7    6136  307.04  6347.8  312.72  6468.9  315.85  6633.6  316.97
#Mann= 12 ,-1 , 0
  3354.3     .05       0  3727.7      .1       0  3838.3     .16       0
  4050.2      .1       0  4152.5     .16       0  4318.2     .05       0
  4621.4     .16       0    4996     .07       0    5002     .16       0
  5632.9     .05       0    6136      .1       0  6347.8     .16       0
Bank Sta=4982.5,5020
XS Rating Curve= 0 ,0
Exp/Cntr=0.3,0.1

Type RM Length L Ch R = 1 ,24838   ,1678,1678,1678
BEGIN DESCRIPTION:
MATHIS CREEK 26.0
END DESCRIPTION:
XS GIS Cut Line= 2
      3565400.46     10264785.44      3562726.97     10262348.05
#Sta/Elev= 30
  3149.6   313.6  3285.9  312.22    3856  307.44  3988.4  304.89  4001.4  304.79
  4540.2  289.39  4661.8   286.4  4736.2  285.37  4828.6   284.4    4963  287.38
  4970.5  286.35  4988.4  277.13  4991.2  276.63  4994.4  277.13  5005.6  278.44
  5023.2  284.62    5034   287.4  5152.1  286.36  5281.1   284.8    5379  285.16
  5539.1     285    5565  285.07    5586  281.84  5668.1  289.54  5797.1  293.24
  5964.4  297.66    6141  303.34    6184  304.81  6456.9  311.11  6767.4  314.48
#Mann= 20 ,-1 , 0
  3149.6     .05       0  3285.9      .1       0    3856     .16       0
  3988.4      .1       0  4001.4     .16       0  4540.2     .05       0
  4661.8     .16       0  4736.2     .05       0  4988.4    .035       0
  4994.4     .05       0  5023.2     .16       0  5152.1      .1       0
  5281.1     .05       0    5379     .16       0  5539.1      .1       0
  5668.1     .16       0  5797.1      .1       0  5964.4     .05       0
    6141      .1       0    6184     .05       0
Bank Sta=4963,5034
XS Rating Curve= 0 ,0
Exp/Cntr=0.3,0.1

Type RM Length L Ch R = 1 ,23160   ,284,284,284
BEGIN DESCRIPTION:
Mapping XS 6b88cc16
END DESCRIPTION:
XS GIS Cut Line= 2
      3565295.92     10263930.61      3563266.34     10261688.46
#Sta/Elev= 30
  2908.9  306.86  3647.4  294.44  3739.3  291.63  3760.3  287.53  3781.9  290.04
  3810.3  290.53  3873.8  287.63  3944.8  291.64  4100.2  288.71  4206.3  289.28
  4466.2  285.71    4585   283.2  4617.3  280.06  4645.7   283.8  4666.6  284.46
  4872.1  282.16  4949.8  283.66  4978.2  281.99  5003.6  276.91  5006.3  276.41
  5009.6  276.91    5035  282.82  5063.4   283.9  5254.5  289.74  5424.3  296.95
  5621.5  300.97  5790.2  304.26  5887.5   305.9  5927.6  306.36  5933.2   306.5
#Mann= 9 ,-1 , 0
  2908.9     .05       0  4466.2     .16       0    4585     .05       0
  5003.6     .04       0  5009.6     .05       0  5621.5     .08       0
  5790.2     .05       0  5887.5     .08       0  5927.6     .05       0
#XS Ineff= 2 , 0
         3953.69  291.65
Permanent Ineff=
       F       F
Bank Sta=4949.8,5063.4
XS Rating Curve= 0 ,0
Exp/Cntr=0.3,0.1

Type RM Length L Ch R = 1 ,22876   ,641,641,641
BEGIN DESCRIPTION:
MATHIS CREEK 25.0
END DESCRIPTION:
XS GIS Cut Line= 2
      3565374.45     10263620.67      3563423.09     10261502.64
#Sta/Elev= 30
  2962.5  303.63  3073.8  300.84  3296.2  298.54  3437.4  291.77  3579.1  290.66
  3635.8   294.2  3912.3  290.63  4041.1  287.62  4204.4  286.96  4442.5  285.22
  4471.3   285.6  4611.1  287.89  4750.8  288.64  4803.5  289.79  4872.8  284.21
  4927.1  283.02  4959.4  282.68  4991.6   275.5  4994.3     275  4997.6   275.5
  5037.1  283.71  5143.2  289.95  5309.8  292.63  5427.2  294.54  5449.6  294.32
  5565.8   297.1  5589.3  298.01  5704.4  301.16  5754.1  302.39  5842.4  303.78
#Mann= 20 ,-1 , 0
  2962.5      .1       0  3073.8     .16       0  3912.3     .05       0
  4041.1     .16       0  4204.4      .1       0  4442.5     .16       0
  4471.3      .1       0  4611.1      .1       0  4750.8      .1       0
  4872.8     .12       0  4927.1      .1       0  4991.6     .07       0
  4997.6      .1       0  5309.8      .1       0  5427.2     .05       0
  5449.6      .1       0  5565.8     .16       0  5589.3     .08       0
  5704.4     .16       0  5754.1      .1       0
#XS Ineff= 2 , 0
         4802.84  289.79
Permanent Ineff=
       F       F
Bank Sta=4959.4,5037.1
XS Rating Curve= 0 ,0
Exp/Cntr=0.3,0.1

Type RM Length L Ch R = 1 ,22235   ,1050,1050,1050
BEGIN DESCRIPTION:
MATHIS CREEK 23.0
END DESCRIPTION:
XS GIS Cut Line= 2
        3565831.     10263049.31      3563546.71     10260827.51
#Sta/Elev= 30
  3003.9  302.19  3189.1  298.39  3475.4  295.48  3885.4  294.95  4281.5  286.78
  4577.1  285.33  4748.8  281.56    4833  279.35  4886.6  281.81  4967.5  283.51
  4974.5  282.51  4981.6  279.29  4988.6   278.8  4995.8  274.72  4999.8  274.41
  5002.5  273.91  5005.8  274.41  5009.9  276.57  5016.9  276.68  5024.1  282.76
  5158.4  280.94  5273.7  282.63  5660.5  290.08  5731.2  292.56  5773.6  296.94
  5794.8   294.5  5851.3   294.4  5872.7  298.62  5900.9  300.83  6190.5  315.04
#Mann= 8 ,-1 , 0
  3003.9      .1       0  3189.1     .05       0  4577.1      .1       0
  4748.8     .16       0  4886.6     .12       0  4999.8     .07       0
  5005.8     .12       0  5273.7     .05       0
Bank Sta=4967.5,5024.1
XS Rating Curve= 0 ,0
Exp/Cntr=0.3,0.1

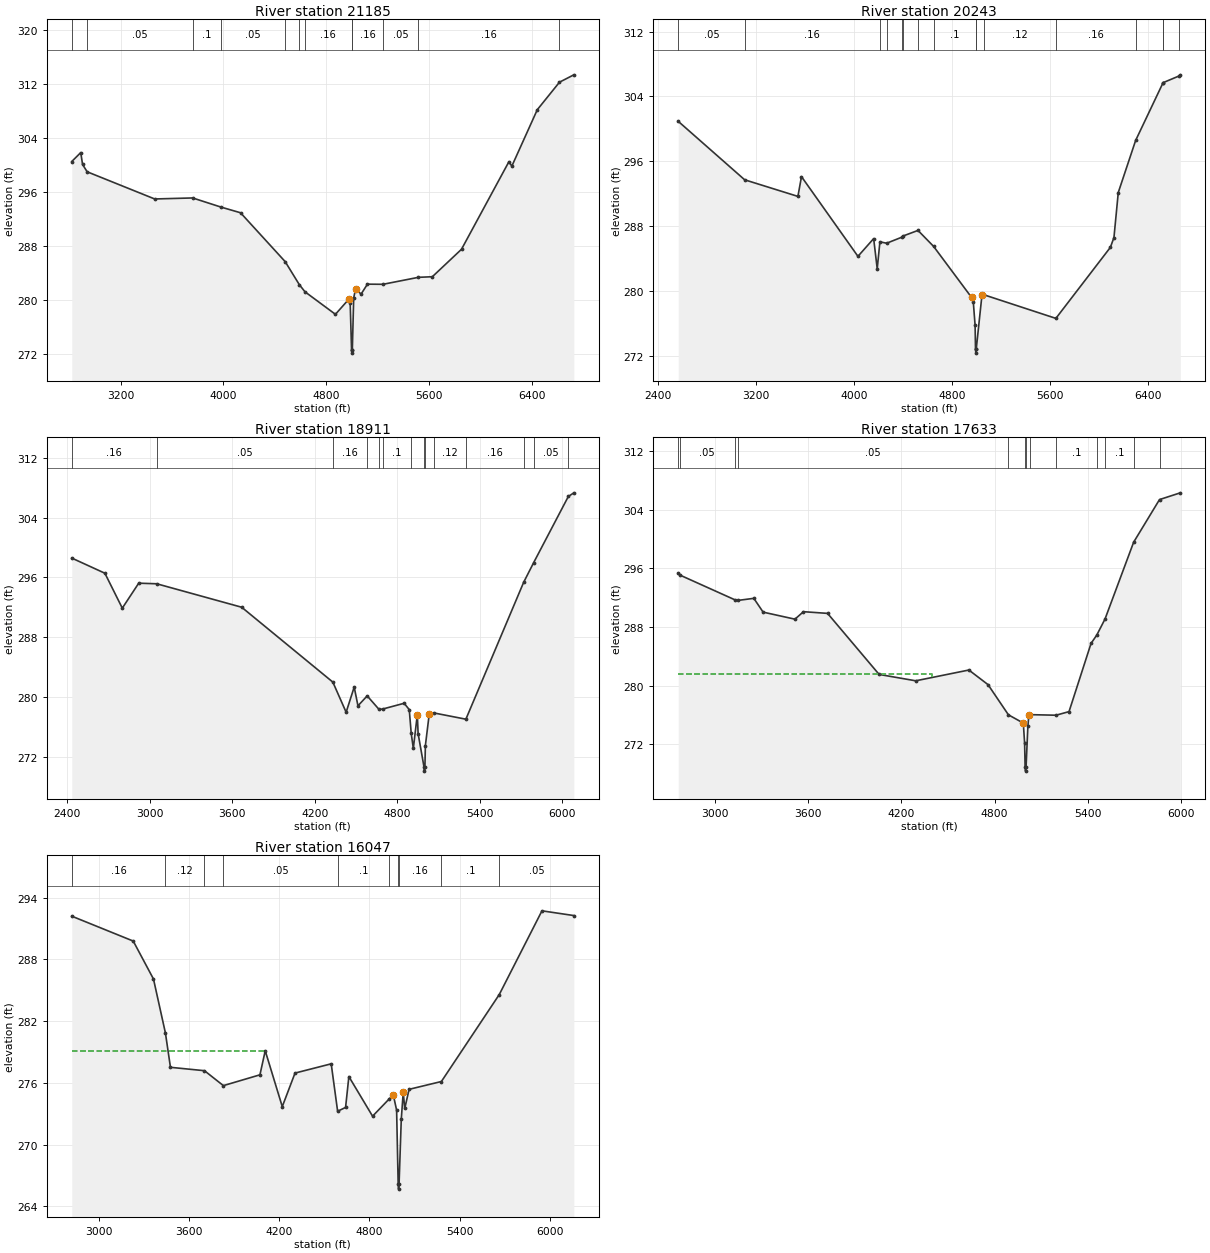
Type RM Length L Ch R = 1 ,21185   ,942,942,942
BEGIN DESCRIPTION:
MATHIS CREEK 22.0
END DESCRIPTION:
XS GIS Cut Line= 2
      3566303.24     10262688.22      3563846.04     10259647.95
#Sta/Elev= 30
  2819.2  300.49  2889.1  301.81  2903.4  300.05  2938.9  298.97  3464.7  294.95
  3760.2   295.1  3982.6  293.74  4133.1  292.91  4480.9  285.68  4591.1  282.27
    4635  281.22    4872  277.89    4979  280.18  4986.9  279.55  4997.6  272.65
  5000.4  272.15  5003.6  272.65  5014.2  280.29  5028.6  281.65  5071.7  280.88
  5121.3  282.35  5242.5  282.33  5517.9  283.36  5626.6  283.45  5853.6  287.51
    6223  300.47  6245.4   299.8  6443.7  308.15  6616.4  312.22  6728.3  313.31
#Mann= 12 ,-1 , 0
  2819.2      .1       0  2938.9     .05       0  3760.2      .1       0
  3982.6     .05       0  4480.9      .1       0  4591.1     .05       0
    4635     .16       0  4997.6     .07       0  5003.6     .16       0
  5242.5     .05       0  5517.9     .16       0  6616.4     .05       0
Bank Sta=4979,5028.6
XS Rating Curve= 0 ,0
Exp/Cntr=0.3,0.1

Type RM Length L Ch R = 1 ,20243   ,1332,1332,1332
BEGIN DESCRIPTION:
MATHIS CREEK 21.0
END DESCRIPTION:
XS GIS Cut Line= 3
      3566553.23     10262507.63      3566101.86     10261424.34
       3564317.8     10259105.75
#Sta/Elev= 30
  2564.8  300.92  3107.1   293.7  3541.8  291.65  3571.1  294.09    4032  284.25
  4160.3  286.44  4189.3  282.72  4211.4  286.04  4266.6  285.87  4394.5  286.64
  4398.5  286.75  4522.3  287.45  4650.1  285.47  4959.5  279.18    4974  278.59
  4988.5  275.72  4991.8   272.8  4994.6   272.3  4997.8   272.8  5044.7  279.49
  5057.1  279.52  5647.9  276.59    6093  285.36  6122.1  286.57  6157.4  292.13
  6299.2  298.56  6522.6  305.67  6524.6   305.7  6653.8  306.52  6663.9  306.66
#Mann= 16 ,-1 , 0
  2564.8     .05       0  3107.1     .16       0  4211.4     .12       0
  4266.6      .1       0  4394.5     .16       0  4398.5      .1       0
  4522.3     .16       0  4650.1      .1       0  4991.8     .07       0
  4997.8      .1       0  5057.1     .12       0  5647.9     .16       0
  6299.2      .1       0  6522.6     .05       0  6524.6      .1       0
  6653.8     .05       0
Bank Sta=4959.5,5044.7
XS Rating Curve= 0 ,0
Exp/Cntr=0.3,0.1

Type RM Length L Ch R = 1 ,18911   ,1278,1278,1278
BEGIN DESCRIPTION:
MATHIS CREEK 20.0
END DESCRIPTION:
XS GIS Cut Line= 3
      3566733.81     10262063.24      3566324.08     10260834.06
      3565129.73     10258806.44
#Sta/Elev= 30
  2434.6  298.58  2675.3  296.55  2801.8  291.88  2921.2  295.22  3051.9  295.14
  3669.6     292  4332.1  281.98  4428.6  277.95  4487.2  281.32  4514.5  278.81
  4581.6  280.14  4668.1  278.32  4696.8  278.39  4850.2  279.15  4887.3   278.3
  4901.6  275.12  4916.9  273.11  4945.9  277.64  4951.7  275.09  4995.1  270.57
  4997.9  270.07  5001.1  270.57  5004.5  273.49  5032.9  277.76  5067.9  277.85
  5298.9  277.02  5718.6  295.33  5790.9  297.95  6043.4  306.82  6083.5  307.31
#Mann= 14 ,-1 , 0
  2434.6     .16       0  3051.9     .05       0  4332.1     .16       0
  4581.6      .1       0  4668.1     .16       0  4696.8      .1       0
  4901.6     .16       0  4995.1     .07       0  5001.1     .16       0
  5067.9     .12       0  5298.9     .16       0  5718.6      .1       0
  5790.9     .05       0  6043.4      .1       0
Bank Sta=4945.9,5032.9
XS Rating Curve= 0 ,0
Exp/Cntr=0.3,0.1

Type RM Length L Ch R = 1 ,17633   ,1586,1586,1586
BEGIN DESCRIPTION:
MATHIS CREEK 18.0
END DESCRIPTION:
XS GIS Cut Line= 3
      3567192.14     10261153.52      3566928.25     10260111.84
      3565643.86     10258376.17
#Sta/Elev= 30
  2762.6  295.34  2772.5  295.08  3125.3  291.72  3148.3  291.62  3249.4   291.9
  3309.3  290.02  3514.3  289.06  3569.2  290.08  3724.4  289.85  4056.4  281.53
  4292.3  280.66  4634.5  282.13  4757.8  280.14  4889.5  276.02  4985.2   274.9
  4993.6  272.15  4996.8  268.85  4999.6  268.35  5002.8  268.85  5014.5  274.44
  5020.7  275.95  5025.6  276.05  5195.8  275.97  5279.6  276.46  5421.5  285.76
  5458.6   286.9  5511.6  289.09  5695.8  299.55  5862.4  305.36  5996.4  306.28
#Mann= 13 ,-1 , 0
  2762.6     .16       0  2772.5     .05       0  3125.3      .1       0
  3148.3     .05       0  4889.5     .16       0  4996.8     .07       0
  5002.8     .16       0  5025.6     .12       0  5195.8      .1       0
  5458.6     .16       0  5511.6      .1       0  5695.8     .16       0
  5862.4      .1       0
#XS Ineff= 2 , 0
         4397.16  281.65
Permanent Ineff=
       F       F
Bank Sta=4985.2,5020.7
XS Rating Curve= 0 ,0
Exp/Cntr=0.3,0.1

Type RM Length L Ch R = 1 ,16047   ,802,802,802
BEGIN DESCRIPTION:
MATHIS CREEK 16.0
END DESCRIPTION:
XS GIS Cut Line= 3
      3568181.46     10259929.33      3566992.18     10258588.78
      3566359.31     10257175.46
#Sta/Elev= 30
  2819.9  292.21  3228.9  289.79  3363.6   286.1  3443.1  280.85  3476.5  277.52
  3702.9  277.19  3828.6  275.74  4071.9  276.79  4107.1  279.13  4220.5   273.7
  4305.3  276.96  4546.1  277.86  4588.8  273.25  4641.7  273.62  4663.6  276.62
  4821.3  272.77  4930.9  274.43  4959.4  274.83  4981.3  273.35  4991.6  266.18
  4994.3  265.68  4997.6  266.18  5012.3  272.47  5025.2  275.08  5035.5  273.52
  5064.2  275.38  5279.2  276.14  5664.2  284.59  5948.4  292.73  6160.5  292.27
#Mann= 10 ,-1 , 0
  2819.9     .16       0  3443.1     .12       0  3702.9      .1       0
  3828.6     .05       0  4588.8      .1       0  4930.9     .16       0
  4991.6     .07       0  4997.6     .16       0  5279.2      .1       0
  5664.2     .05       0
#XS Ineff= 2 , 0
         4109.09  279.12
Permanent Ineff=
       F       F
Bank Sta=4959.4,5025.2
XS Rating Curve= 0 ,0
Exp/Cntr=0.3,0.1