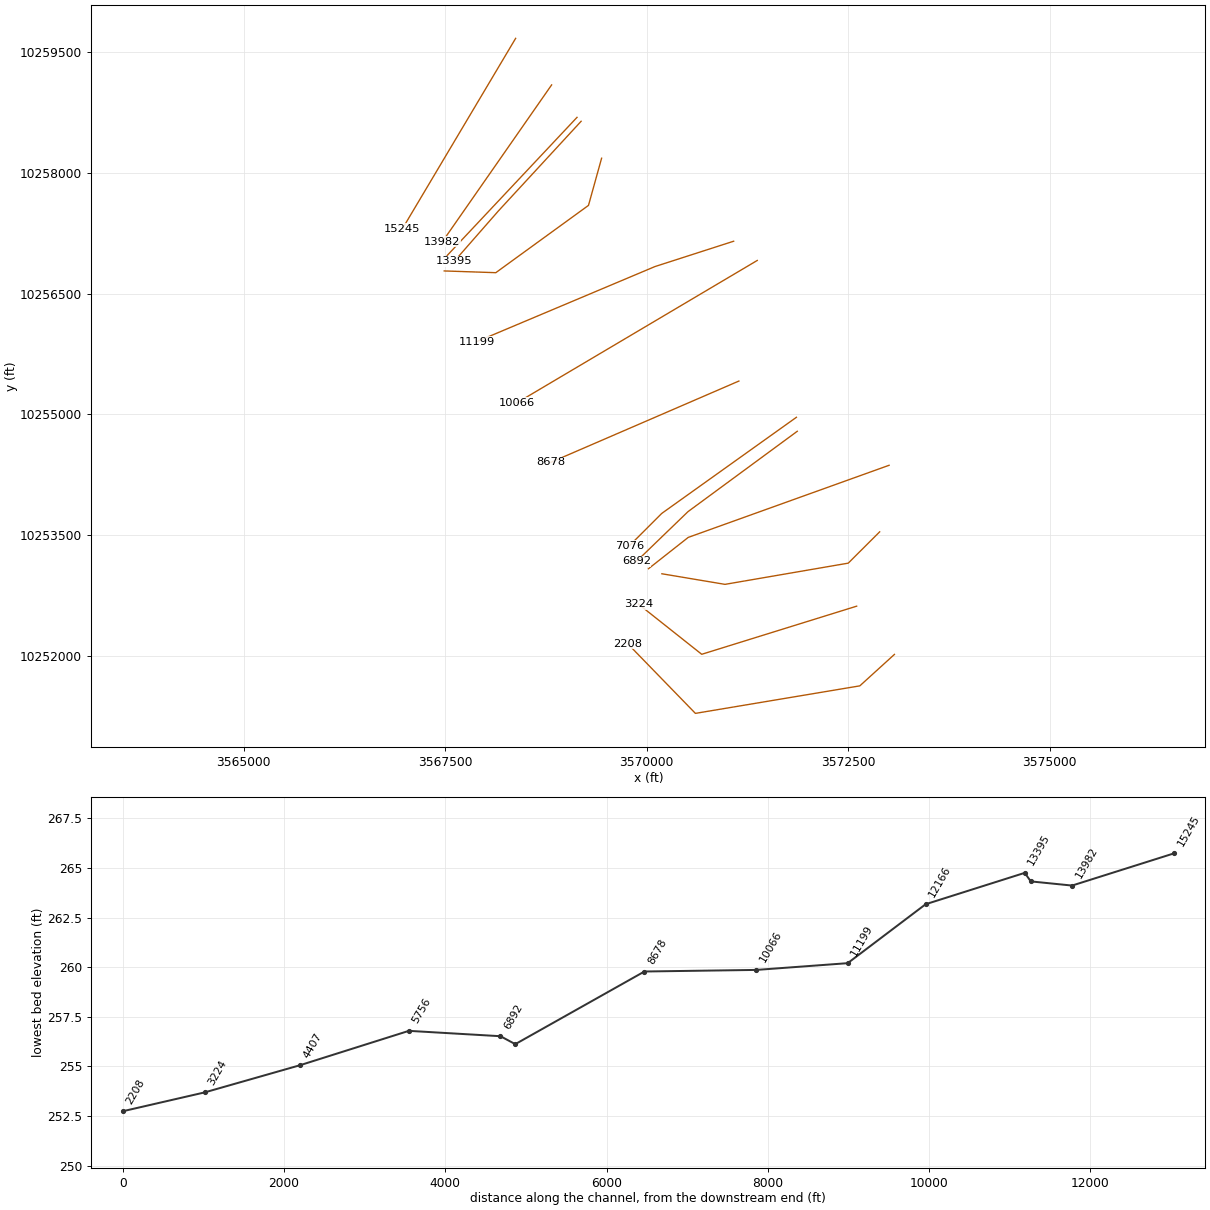
HEC-RAS study MATHIS CREEK.prj: MATHIS CREEK Base Level Engineering

--- MATHIS CREEK.g01 (geometry) --- (continued)

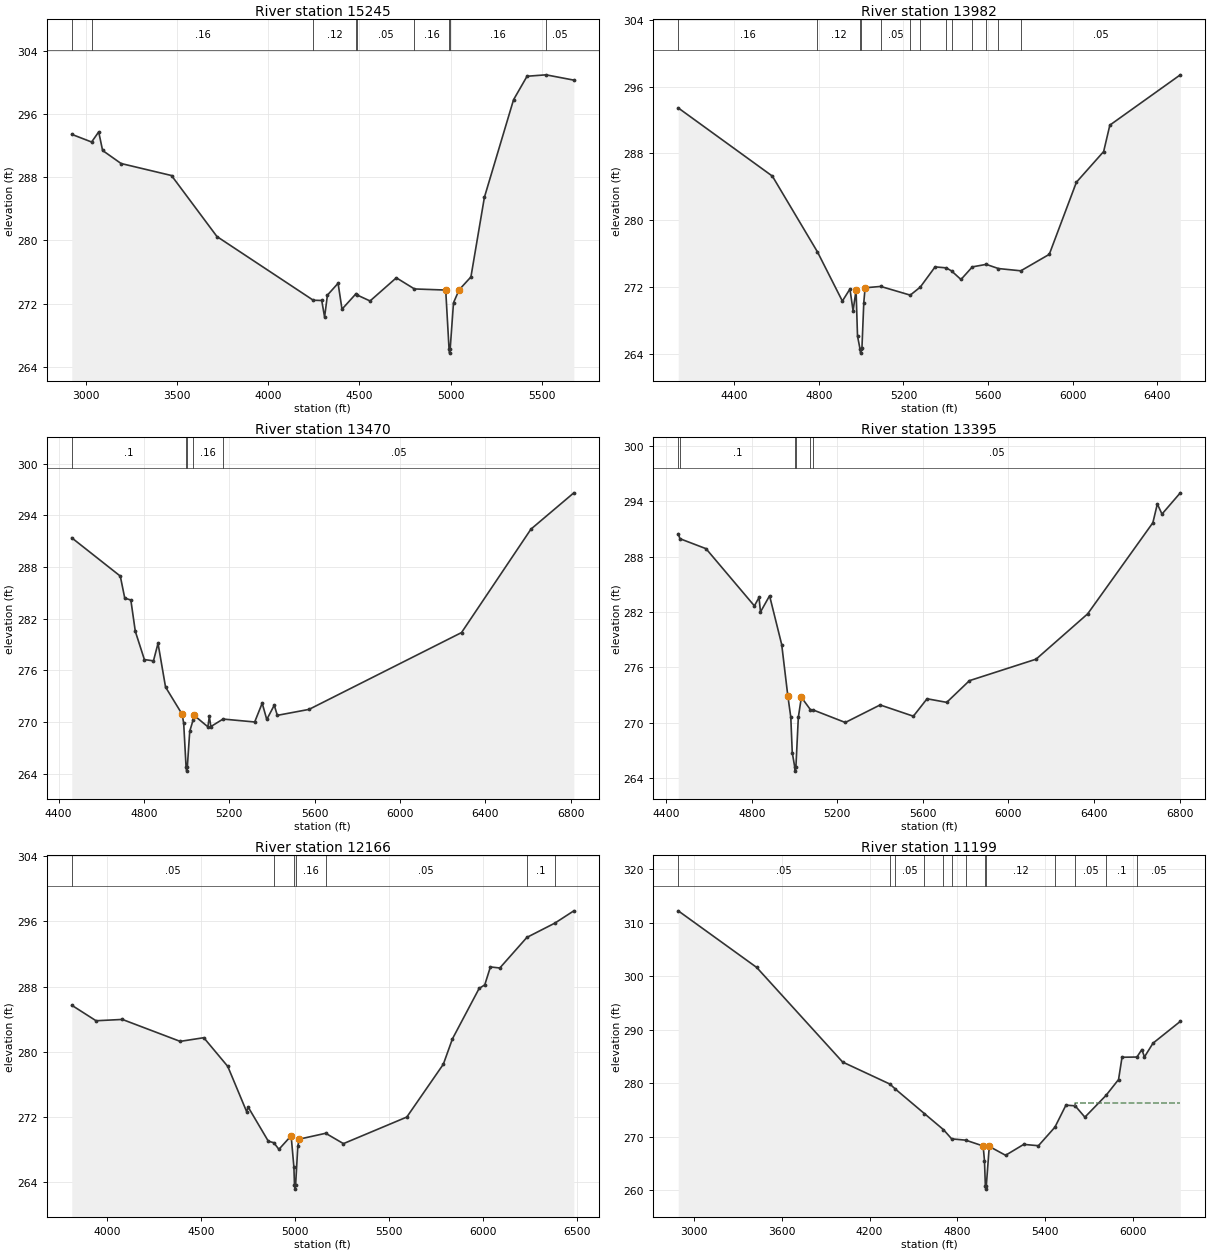
Type RM Length L Ch R = 1 ,15245   ,1263,1263,1263
BEGIN DESCRIPTION:
MATHIS CREEK 15.0
END DESCRIPTION:
XS GIS Cut Line= 2
      3568375.07     10259669.32      3566968.26      10257302.1
#Sta/Elev= 30
  2922.8  293.41  3031.6  292.44  3070.5  293.72  3091.9  291.37  3193.2  289.72
  3469.8   288.2  3719.1  280.48  4247.5  272.42  4293.8  272.39  4309.4  270.29
    4325  273.07  4383.4  274.57  4404.9  271.29  4482.7  273.27  4485.3  273.11
  4558.8  272.33  4702.9  275.26  4802.3  273.85  4973.7  273.71  4992.1  266.23
  4994.8  265.73  4998.1  266.23  5016.5  272.11  5047.7  273.75    5112  275.37
    5186  285.45  5345.8  297.79  5419.8  300.76  5523.9  300.94  5676.5  300.27
#Mann= 9 ,-1 , 0
  2922.8     .05       0  3031.6     .16       0  4247.5     .12       0
  4482.7      .1       0  4485.3     .05       0  4802.3     .16       0
  4992.1     .07       0  4998.1     .16       0  5523.9     .05       0
Bank Sta=4973.7,5047.7
XS Rating Curve= 0 ,0
Exp/Cntr=0.3,0.1

Type RM Length L Ch R = 1 ,13982   ,512,512,512
BEGIN DESCRIPTION:
Mapping XS f2dd5968
END DESCRIPTION:
XS GIS Cut Line= 2
      3568821.51     10259091.08      3567466.25     10257144.38
#Sta/Elev= 30
    4136  293.45  4580.7  285.29  4793.8  276.22  4911.4  270.34  4947.2  271.78
    4962  269.18  4976.1  271.65    4983  266.15  4994.8  264.61  4997.6  264.11
  5000.8  264.61  5003.9  264.71  5012.6  270.13  5018.8  271.93  5092.6  272.09
  5232.1  271.05  5279.5  272.01  5349.5  274.43  5402.5  274.31  5427.5  273.94
  5471.7  272.92  5525.6  274.43  5591.1  274.73  5648.7  274.23  5754.6  273.96
  5888.9  275.93  6017.1  284.56  6145.8  288.23  6175.1  291.39    6508  297.41
#Mann= 13 ,-1 , 0
    4136     .16       0  4793.8     .12       0  4994.8     .07       0
  5000.8     .12       0  5092.6     .05       0  5232.1     .12       0
  5279.5     .05       0  5402.5     .08       0  5427.5     .05       0
  5525.6     .08       0  5591.1     .05       0  5648.7     .08       0
  5754.6     .05       0
Bank Sta=4976.1,5018.8
XS Rating Curve= 0 ,0
Exp/Cntr=0.3,0.1

Type RM Length L Ch R = 1 ,13470   ,75,75,75
BEGIN DESCRIPTION:
MATHIS CREEK 14.0
END DESCRIPTION:
XS GIS Cut Line= 2
      3569136.58     10258688.22      3567526.26     10256973.79
#Sta/Elev= 30
  4462.1  291.38  4689.4  286.94  4710.4  284.38  4738.8  284.17  4759.8  280.53
  4802.3  277.26  4844.8  277.11  4866.2  279.14  4901.4  274.07  4979.1  270.92
  4986.4  269.87  4997.5  264.82  5000.3  264.32  5003.5  264.82  5014.7  268.94
  5030.8  270.27  5035.7  270.78  5099.7  269.46  5106.5  270.66  5113.8  269.49
  5170.8  270.36    5319  270.02  5354.2   272.2  5375.6  270.31  5410.8  271.97
    5425  270.79  5573.5  271.48    6288  280.39  6613.3  292.39  6814.2   296.6
#Mann= 5 ,-1 , 0
  4462.1      .1       0  4997.5     .07       0  5003.5      .1       0
  5030.8     .16       0  5170.8     .05       0
Bank Sta=4979.1,5035.7
XS Rating Curve= 0 ,0
Exp/Cntr=0.3,0.1

Type RM Length L Ch R = 1 ,13395   ,1229,1229,1229
BEGIN DESCRIPTION:
MATHIS CREEK 13.0
END DESCRIPTION:
XS GIS Cut Line= 3
      3569187.51      10258639.4      3568161.48     10257526.56
      3567612.85     10256899.81
#Sta/Elev= 30
  4456.6  290.46  4464.5  289.93  4586.4  288.85  4812.6  282.65  4834.2  283.57
    4841  281.99  4883.5  283.75  4940.2  278.46  4968.6  272.94  4982.7  270.59
  4989.5  266.76  5000.7  265.25  5003.5  264.75  5006.7  265.25  5017.9  270.58
  5032.1  272.75  5074.4  271.41  5086.9  271.38  5237.4  270.02  5400.1  271.92
  5555.5   270.7  5619.6  272.59  5711.4   272.2  5817.5  274.55  6129.2  276.88
  6370.2  281.79  6674.9  291.66  6695.8  293.69  6717.6   292.6  6803.2   294.9
#Mann= 6 ,-1 , 0
  4456.6     .05       0  4464.5      .1       0  5000.7     .07       0
  5006.7      .1       0  5074.4     .16       0  5086.9     .05       0
Bank Sta=4968.6,5032.1
XS Rating Curve= 0 ,0
Exp/Cntr=0.3,0.1

Type RM Length L Ch R = 1 ,12166   ,967,967,967
BEGIN DESCRIPTION:
MATHIS CREEK 12.0
END DESCRIPTION:
XS GIS Cut Line= 4
      3569441.72     10258180.89      3569278.94     10257594.91
      3568128.77     10256759.41      3567488.61     10256781.11
#Sta/Elev= 30
  3810.8  285.72  3939.9  283.82  4079.9  283.98  4387.3  281.29  4512.9  281.74
  4640.5  278.22  4740.9  272.67  4748.8  273.24  4856.1  269.05  4885.4  268.86
  4912.5  268.05  4977.5  269.71  4992.2  265.88  4995.3  263.67  4998.1  263.17
  5001.3  263.67    5013  268.43  5020.7   269.3  5161.3  270.02  5255.7  268.75
  5592.7  272.01    5787  278.49  5835.4   281.6  5977.3  287.78  6007.3  288.22
  6037.3  290.42  6087.4  290.29  6231.3  294.04  6380.7   295.8  6481.1   297.3
#Mann= 7 ,-1 , 0
  3810.8     .05       0  4885.4     .16       0  4995.3     .07       0
  5001.3     .16       0  5161.3     .05       0  6231.3      .1       0
  6380.7     .05       0
Bank Sta=4977.5,5020.7
XS Rating Curve= 0 ,0
Exp/Cntr=0.3,0.1

Type RM Length L Ch R = 1 ,11199   ,1133,1133,1133
BEGIN DESCRIPTION:
MATHIS CREEK 10.0
END DESCRIPTION:
XS GIS Cut Line= 3
      3571080.12     10257150.02       3570103.6     10256835.36
      3567890.02     10255902.19
#Sta/Elev= 30
    2894  312.26  3429.8  301.67  4016.7  283.97  4339.4  279.85  4376.9  278.91
  4574.9  274.33  4705.2  271.32  4761.1   269.6  4856.8  269.36  4975.9  268.27
  4985.1  265.51  4991.2   260.7  4993.9   260.2  4997.2   260.7  5017.7  268.19
  5129.1  266.53  5253.1  268.57  5353.5  268.32    5466  271.79  5541.2  275.91
  5604.3  275.78  5670.7  273.66  5815.1  277.74  5900.5   280.7  5924.2  284.87
    6026  284.91  6059.5  286.31  6077.4  284.93  6135.7   287.5  6322.2  291.58
#Mann= 13 ,-1 , 0
    2894     .05       0  4339.4     .16       0  4376.9     .05       0
  4574.9     .16       0  4705.2     .05       0  4761.1     .16       0
  4856.8     .12       0  4991.2     .07       0  4997.2     .12       0
    5466      .1       0  5604.3     .05       0  5815.1      .1       0
    6026     .05       0
#XS Ineff= 2 , 0
                         5602.27          276.37
Permanent Ineff=
       F       F
Bank Sta=4975.9,5017.7
XS Rating Curve= 0 ,0
Exp/Cntr=0.3,0.1

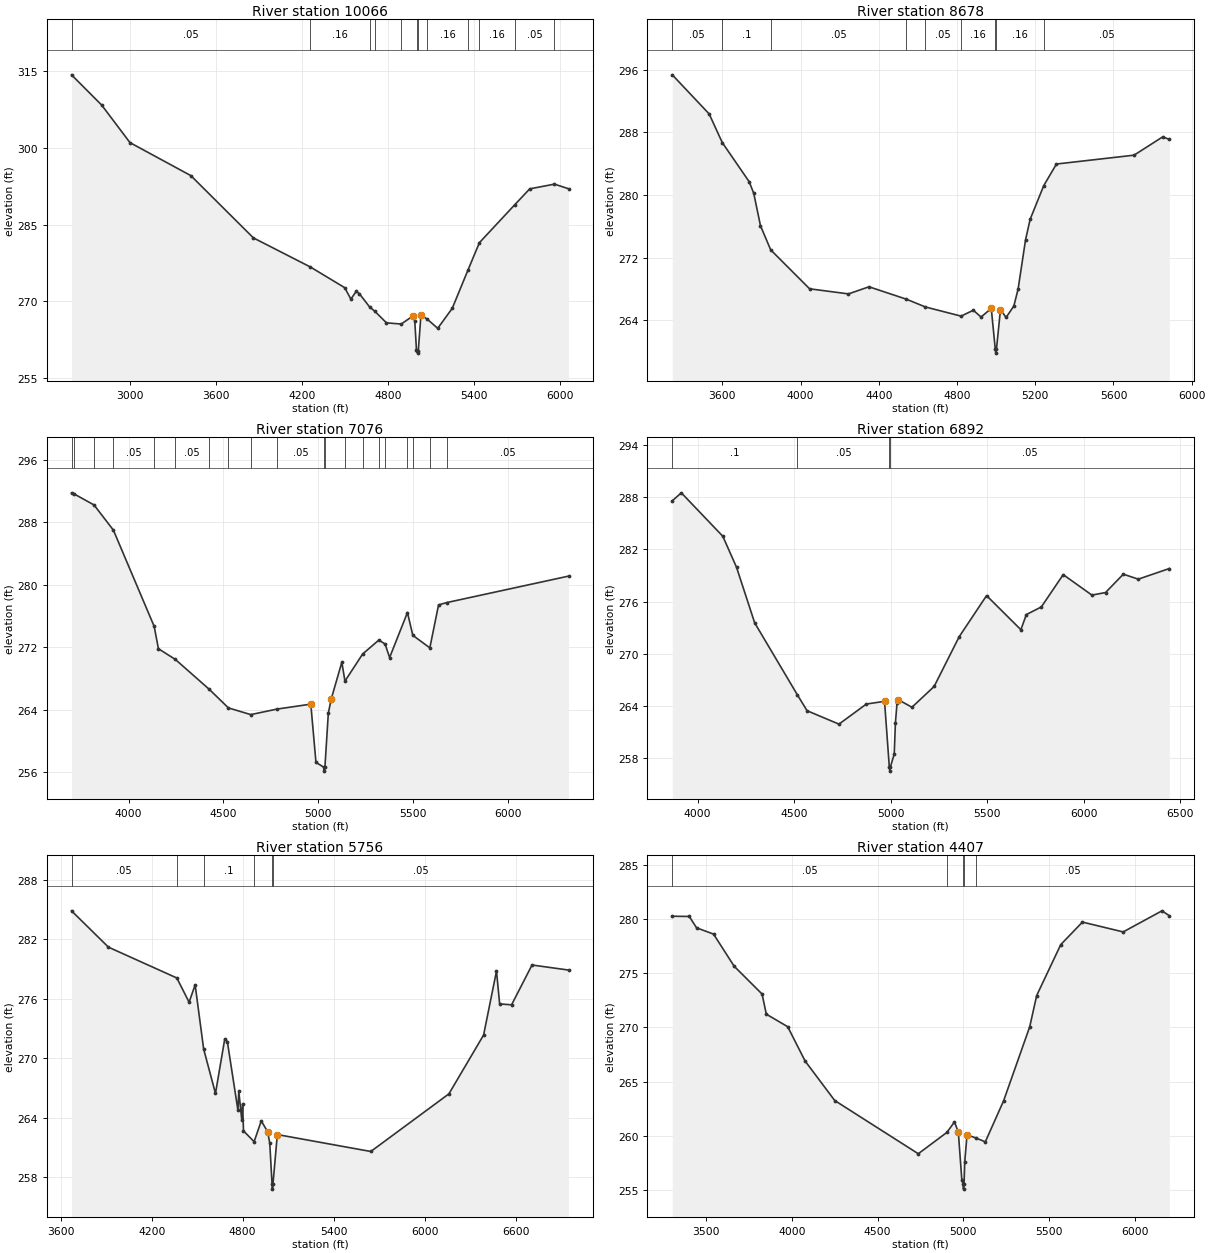
Type RM Length L Ch R = 1 ,10066   ,1388,1388,1388
BEGIN DESCRIPTION:
MATHIS CREEK 9.0
END DESCRIPTION:
XS GIS Cut Line= 2
      3571373.09      10256911.3      3568389.18     10255142.65
#Sta/Elev= 30
  2590.9  314.29  2801.6  308.37  2998.9  301.03  3423.5  294.58  3860.1   282.4
  4258.4   276.7  4497.5  272.66  4540.4  270.43  4577.5  271.92  4598.9  271.52
    4671   268.9  4707.1  268.06  4789.1  265.78  4891.9  265.55    4977  267.19
  4986.7  266.05  4998.4  260.46  5005.2  260.36    5008  259.86  5011.2  260.36
  5029.7  267.33    5075  266.47  5146.6  264.71    5248  268.62  5356.7  276.03
  5437.5  281.46  5685.6  288.92  5788.8  291.99  5961.5  292.91  6059.6  292.01
#Mann= 12 ,-1 , 0
  2590.9     .05       0  4258.4     .16       0    4671     .05       0
  4707.1     .16       0  4891.9     .12       0  5005.2     .07       0
  5011.2     .12       0    5075     .16       0  5356.7     .12       0
  5437.5     .16       0  5685.6     .05       0  5961.5     .16       0
Bank Sta=4977,5029.7
XS Rating Curve= 0 ,0
Exp/Cntr=0.3,0.1

Type RM Length L Ch R = 1 ,8678    ,1602,1602,1602
BEGIN DESCRIPTION:
MATHIS CREEK 8.0
END DESCRIPTION:
XS GIS Cut Line= 2
      3571145.22      10255413.9      3568812.32     10254404.79
#Sta/Elev= 30
  3343.9  295.35  3532.5  290.35  3599.5  286.69  3737.1  281.69  3760.5   280.2
  3794.9  276.06  3847.1  272.98  4046.2     268    4245  267.35  4349.8  268.26
  4541.5  266.67  4638.5  265.68  4820.7  264.51  4883.6  265.26  4922.8  264.39
  4975.2  265.49  4995.7  260.28  4998.4  259.78  5001.7  260.28  5022.2  265.34
  5051.1  264.34  5090.6   265.8  5112.4  267.97  5150.5  274.27    5174  276.89
  5243.8   281.2  5308.5  283.95  5705.4  285.08  5851.8  287.42  5885.7   287.1
#Mann= 9 ,-1 , 0
  3343.9     .05       0  3599.5      .1       0  3847.1     .05       0
  4541.5     .16       0  4638.5     .05       0  4820.7     .16       0
  4995.7     .07       0  5001.7     .16       0  5243.8     .05       0
Bank Sta=4975.2,5022.2
XS Rating Curve= 0 ,0
Exp/Cntr=0.3,0.1

Type RM Length L Ch R = 1 ,7076    ,184,184,184
BEGIN DESCRIPTION:
MATHIS CREEK 7.0
END DESCRIPTION:
XS GIS Cut Line= 3
      3571858.87     10254963.81      3570187.91     10253770.26
      3569786.74     10253369.09
#Sta/Elev= 30
    3699  291.77  3709.8  291.67  3818.1  290.21  3919.8  286.99  4134.9  274.66
  4157.3   271.8  4246.4  270.43  4425.3   266.6  4526.2  264.22  4644.2  263.36
  4783.1  264.07  4960.8   264.7    4988  257.24  5029.2  256.62    5032  256.12
  5035.2  256.62  5053.1  263.52  5067.9  265.31  5124.4  270.07  5140.8  267.65
  5234.3  271.13  5319.7  272.91  5352.4   272.4  5376.3  270.67  5470.4  276.44
  5498.6  273.52  5588.4  271.91  5634.4  277.41  5677.5  277.71  6319.8   281.1
#Mann= 20 ,-1 , 0
    3699     .05       0  3709.8     .05       0  3818.1     .16       0
  3919.8     .05       0  4134.9     .16       0  4246.4     .05       0
  4425.3      .1       0  4526.2     .05       0  4644.2      .1       0
  4783.1     .05       0  5029.2     .03       0  5035.2     .05       0
  5140.8      .1       0  5234.3     .05       0  5319.7      .1       0
  5352.4     .05       0  5470.4      .1       0  5498.6     .05       0
  5588.4      .1       0  5677.5     .05       0
Bank Sta=4960.8,5067.9
XS Rating Curve= 0 ,0
Exp/Cntr=0.3,0.1

Type RM Length L Ch R = 1 ,6892    ,1136,1136,1136
BEGIN DESCRIPTION:
MATHIS CREEK 6.0
END DESCRIPTION:
XS GIS Cut Line= 3
      3571869.79     10254790.24      3570513.43     10253791.96
      3569873.23     10253173.46
#Sta/Elev= 30
  3869.3  287.59  3916.1   288.5  4130.9  283.51  4201.9  279.95    4296  273.56
  4517.6  265.27  4567.5  263.46  4732.6  261.92  4874.5  264.23  4968.6  264.54
  4993.3  257.02  4996.1  256.52  4999.3  257.02  5018.8  258.48    5025  262.08
  5033.4  264.38  5039.6  264.73  5110.6  263.86  5225.5  266.25  5355.1  271.96
  5497.1  276.69  5674.8  272.77  5703.1  274.51  5780.8  275.39    5894   279.1
  6042.5  276.75  6113.2  277.04  6205.3  279.15    6283  278.58  6443.6   279.8
#Mann= 4 ,-1 , 0
  3869.3      .1       0  4517.6     .05       0  4993.3    .035       0
  4999.3     .05       0
Bank Sta=4968.6,5039.6
XS Rating Curve= 0 ,0
Exp/Cntr=0.3,0.1

Type RM Length L Ch R = 1 ,5756    ,1349,1349,1349
BEGIN DESCRIPTION:
MATHIS CREEK 5.0
END DESCRIPTION:
XS GIS Cut Line= 3
       3573009.2     10254368.02      3570516.15     10253472.19
      3570023.08     10253083.29
#Sta/Elev= 30
  3671.8  284.89  3915.4  281.22  4366.2  278.11  4447.2  275.66  4486.9  277.42
    4543  270.94    4621  266.45  4682.4  271.97  4699.4  271.68  4769.3  264.73
  4774.6   266.7  4794.7  263.73    4800  265.41  4805.7  262.67  4875.8  261.58
  4922.9  263.68  4965.1  262.58    4979  261.43    4994  257.29  4996.7  256.79
    5000  257.29  5028.8   262.3  5645.1  260.59  6160.2  266.41  6388.9  272.35
  6473.9  278.81  6494.7  275.49  6573.3   275.4  6708.2  279.42  6948.9  278.91
#Mann= 6 ,-1 , 0
  3671.8     .05       0  4366.2     .07       0    4543      .1       0
  4875.8     .05       0    4994     .03       0    5000     .05       0
Bank Sta=4965.1,5028.8
XS Rating Curve= 0 ,0
Exp/Cntr=0.3,0.1

Type RM Length L Ch R = 1 ,4407    ,1183,1183,1183
BEGIN DESCRIPTION:
MATHIS CREEK 3.0
END DESCRIPTION:
XS GIS Cut Line= 4
       3572892.1     10253541.64      3572502.26     10253152.74
      3570972.58     10252889.36      3570189.78      10253020.8
#Sta/Elev= 30
  3303.3  280.28  3402.3  280.26  3444.7  279.21  3543.7  278.63  3663.9  275.66
  3826.5  273.09  3851.2  271.23  3975.9  270.07  4077.3   266.9  4249.8  263.25
  4736.9  258.33  4903.5   260.3  4947.8  261.27  4970.3  260.33  4990.6  255.93
  4997.7  255.56  5000.5  255.06  5003.7  255.56  5007.7  257.58    5021  260.08
    5074  259.78  5127.5  259.43  5234.1  263.22  5386.3  270.06  5426.9  272.95
  5567.3  277.66  5693.6  279.74    5931  278.83    6157  280.78  6199.9  280.33
#Mann= 5 ,-1 , 0
  3303.3     .05       0  4903.5     .16       0  4997.7     .07       0
  5003.7     .16       0    5074     .05       0
Bank Sta=4970.3,5021
XS Rating Curve= 0 ,0
Exp/Cntr=0.3,0.1

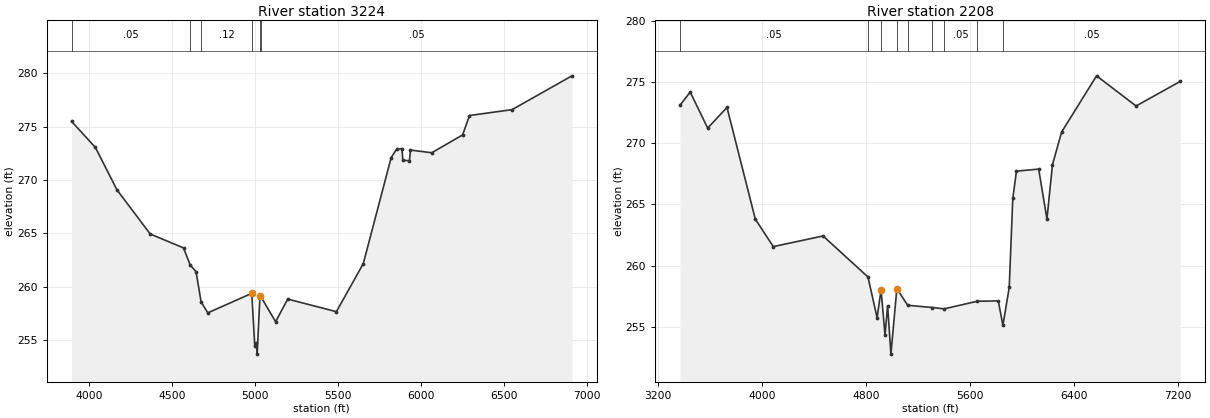
Type RM Length L Ch R = 1 ,3224    ,1016,1016,1016
BEGIN DESCRIPTION:
MATHIS CREEK 2.0
END DESCRIPTION:
XS GIS Cut Line= 3
      3572606.52     10252618.48      3570684.04     10252020.96
      3569898.17     10252644.52
#Sta/Elev= 30
  3892.2  275.51  4035.7  273.07  4165.9  269.09  4366.5  264.95    4567  263.65
  4607.5  262.04  4642.6  261.42  4673.1  258.58  4713.6  257.56  4978.6  259.39
  4996.4  254.44  5005.9  254.71  5010.9  253.69  5027.8  259.16  5035.6  259.01
    5122  256.73  5195.3  258.85  5488.5  257.67  5650.6  262.17  5818.6  272.11
  5851.2  272.89  5883.7  272.96    5889  271.85  5928.8  271.83  5935.2  272.82
  6063.4  272.57  6249.3  274.24  6290.9  276.06  6547.3  276.61  6908.6  279.78
#Mann= 6 ,-1 , 0
  3892.2     .05       0  4607.5     .16       0  4673.1     .12       0
  4978.6     .07       0  5027.8     .12       0  5035.6     .05       0
Bank Sta=4978.6,5027.8
XS Rating Curve= 0 ,0
Exp/Cntr=0.3,0.1

Type RM Length L Ch R = 1 ,2208    ,0,0,0
BEGIN DESCRIPTION:
MATHIS CREEK 1.0
END DESCRIPTION:
XS GIS Cut Line= 4
      3573075.28     10252019.54      3572645.57      10251628.9
      3570605.55     10251287.32      3569767.94     10252149.76
#Sta/Elev= 30
  3368.1  273.13  3446.7  274.21  3581.2  271.26  3729.9  272.95  3947.8   263.8
  4086.4  261.55  4469.4  262.42    4815  259.06  4885.2  255.72  4915.6     258
    4946  254.31  4966.3   256.7  4991.5  252.74  5037.2   258.1    5121  256.74
    5310  256.56  5401.8  256.45  5655.5  257.07    5818   257.1  5853.4  255.09
  5902.2  258.21  5929.5  265.49  5957.8  267.73  6128.8   267.9  6192.4   263.8
  6234.8  268.26  6305.6  270.94  6574.4  275.54  6878.4  273.07  7219.5  275.09
#Mann= 9 ,-1 , 0
  3368.1     .05       0    4815     .16       0  4915.6     .07       0
  5037.2     .16       0    5121     .05       0    5310     .16       0
  5401.8     .05       0  5655.5     .16       0  5853.4     .05       0
Bank Sta=4915.6,5037.2
XS Rating Curve= 0 ,0
Exp/Cntr=0.3,0.1

Chan Stop Cuts=-1
Use User Specified Reach Order=0
Composite Channel Slope=5