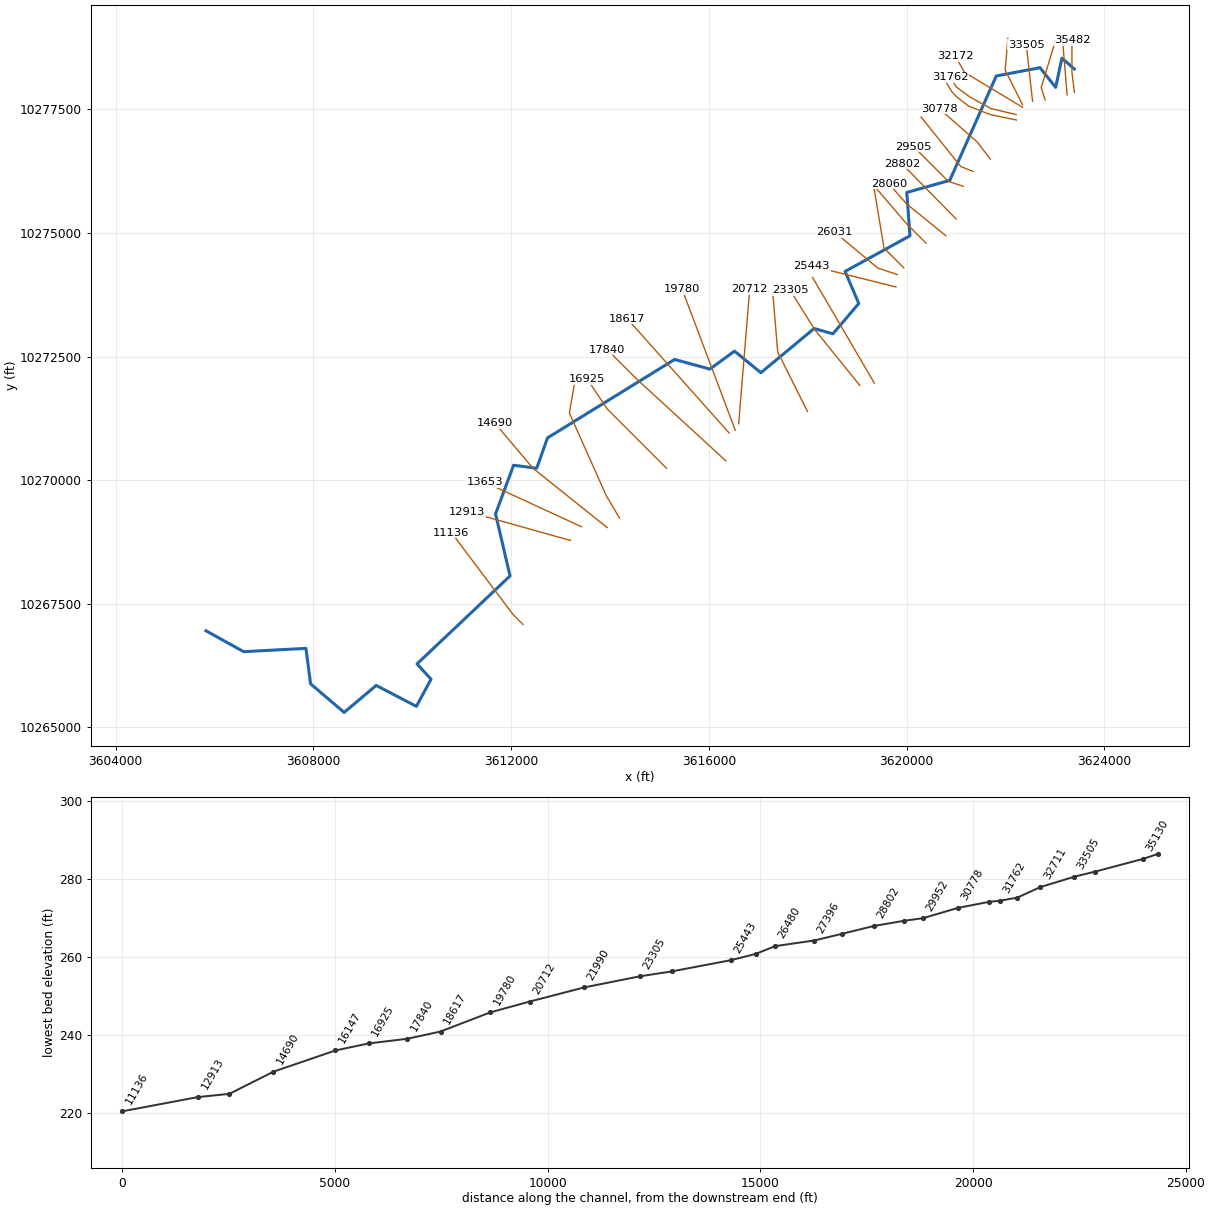
--- MORGAN CREEK.prj (project) ---

Proj Title=MORGAN CREEK Base Level Engineering
Current Plan=p01
Default Exp/Contr=0.3,0.1
English Units
Geom File=g01
Flow File=f01
Plan File=p01
Y Axis Title=Elevation
X Axis Title(PF)=Main Channel Distance
X Axis Title(XS)=Station
BEGIN DESCRIPTION:
MORGAN CREEK
END DESCRIPTION:
DSS Export Rating Curves= 0
DSS Export Rating Curve Sorted= 0
DSS Export Volume Flow Curves= 0
DXF OffsetX= 0
DXF OffsetY= 0
DXF ScaleX= 1
DXF ScaleY= 10

--- MORGAN CREEK.p01 (plan) ---

Plan Title=Multiple Run
Short Identifier=Multiple
Geom File=g01
Flow File=f01
Subcritical Flow
K Sum by GR= 0
Std Step Tol= 0.01
Critical Tol= 0.01
Num of Std Step Trials= 20
Max Error Tol= 0.3
Flow Tol Ratio= 0.001
Split Flow NTrial= 30
Split Flow Tol= 0.02
Split Flow Ratio= 0.02
Log Output Level= 0
Friction Slope Method= 1
Unsteady Friction Slope Method= 2
Unsteady Bridges Friction Slope Method= 1
Parabolic Critical Depth
Global Vel Dist=  1 , 1 , 1
Global Log Level= 0
CheckData=True
Encroach Param= -1, 0, 0, 0
BEGIN DESCRIPTION:
Multiple Run
END DESCRIPTION:

--- MORGAN CREEK.f01 (steady flow) ---

Flow Title=Multiple
Program Version=4.10
Number of Profiles= 7
Profile Names=10-year,25-year,50-year,1pct_min,100-year,1pct_plu,500-year
River Rch & RM=MORGAN CREEK,Reach-1         ,35482
     854    1157    1405    1248    1688    2283    2442
River Rch & RM=MORGAN CREEK,Reach-1         ,26031
     939    1277    1554    1383    1870    2530    2715
River Rch & RM=MORGAN CREEK,Reach-1         ,24052
    1737    2430    3014    2728    3690    4990    5543
River Rch & RM=MORGAN CREEK,Reach-1         ,17840
    1793    2512    3119    2825    3821    5168    5750
River Rch & RM=MORGAN CREEK,Reach-1         ,14690
    2214    3115    3878    3519    4759    6435    7185
Boundary for River Rch & Prof#=MORGAN CREEK,Reach-1         , 1
Up Type= 0
Dn Type= 3
Dn Slope=0.00105
Boundary for River Rch & Prof#=MORGAN CREEK,Reach-1         , 2
Up Type= 0
Dn Type= 3
Dn Slope=0.00105
Boundary for River Rch & Prof#=MORGAN CREEK,Reach-1         , 3
Up Type= 0
Dn Type= 3
Dn Slope=0.00105
Boundary for River Rch & Prof#=MORGAN CREEK,Reach-1         , 4
Up Type= 0
Dn Type= 3
Dn Slope=0.00105
Boundary for River Rch & Prof#=MORGAN CREEK,Reach-1         , 5
Up Type= 0
Dn Type= 3
Dn Slope=0.00105
Boundary for River Rch & Prof#=MORGAN CREEK,Reach-1         , 6
Up Type= 0
Dn Type= 3
Dn Slope=0.00105
Boundary for River Rch & Prof#=MORGAN CREEK,Reach-1         , 7
Up Type= 0
Dn Type= 3
Dn Slope=0.00105
DSS Import GetInterval= 0
DSS Import GetPeak= 0
DSS Import FillOption= 0

--- MORGAN CREEK.g01 (geometry) ---

Geom Title=Existing Conditions
Program Version=4.10

River Reach=MORGAN CREEK    ,Reach-1
Reach XY= 30
      3623392.11     10278311.64      3623139.77     10278531.68
      3623012.38     10277941.22      3622696.37     10278339.19
       3621812.2     10278171.93      3620871.37     10276061.35
      3620002.17     10275816.57       3620066.5     10274940.22
       3618754.3     10274221.03      3619031.25     10273572.18
      3618508.66     10272959.02      3618129.29      10273066.3
      3617051.48     10272172.73      3616516.79     10272609.12
      3616021.44     10272245.63      3615306.84     10272440.64
      3612736.85     10270855.29      3612518.12     10270241.29
      3612050.02     10270301.75      3611685.83      10269316.6
      3611978.51     10268063.55      3610096.89     10266285.08
      3610381.43     10265976.77      3610084.55      10265427.1
      3609272.17     10265850.47       3608623.6     10265304.87
      3607944.54     10265882.65      3607851.39     10266599.36
        3606592.     10266532.62      3605829.34     10266955.52

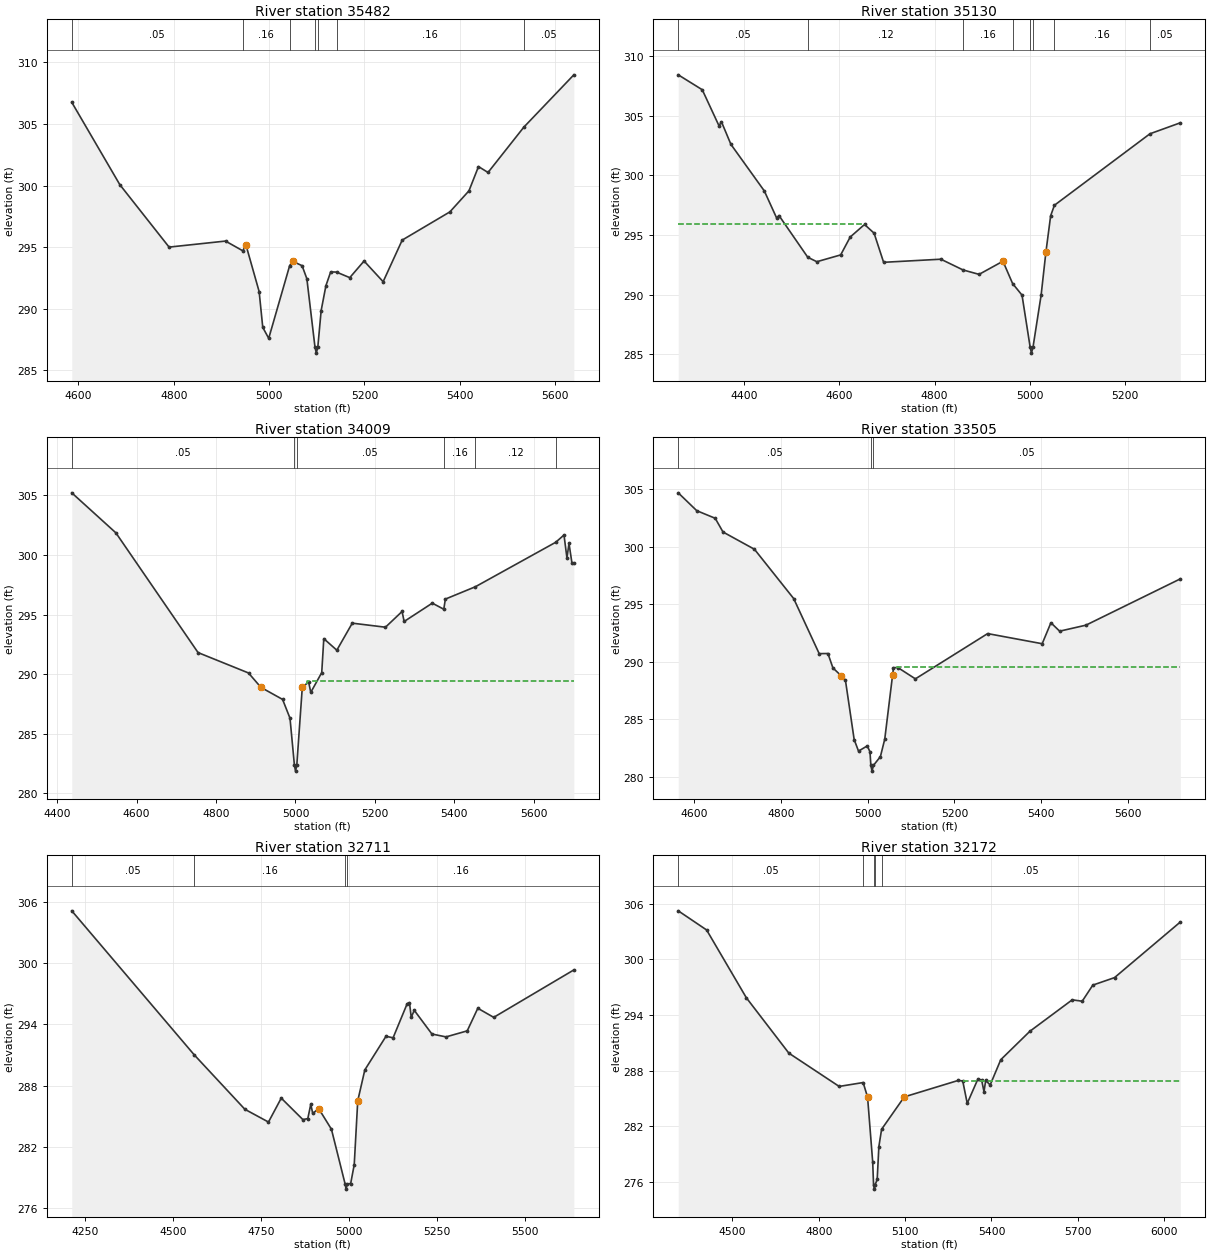
Type RM Length L Ch R = 1 ,35482   ,352,352,352
BEGIN DESCRIPTION:
MORGAN CREEK 62.0
END DESCRIPTION:
XS GIS Cut Line= 3
       3623392.1     10277841.65      3623342.11     10278241.64
      3623342.11     10278891.64
#Sta/Elev= 30
  4586.2  306.76    4687  300.07  4790.3     295  4908.7  295.49  4944.9   294.7
  4951.5  295.18  4979.2  291.39  4986.8  288.48  4999.3  287.59  5043.2  293.49
  5049.3  293.85  5069.3  293.49  5079.3  292.43  5096.3  286.89  5099.1  286.39
  5102.3  286.89  5109.3  289.85  5119.3  291.87  5129.3  292.99  5141.5  292.97
  5169.3  292.52  5199.3  293.87  5239.3  292.19  5279.3  295.57  5379.3  297.86
  5419.3  299.57  5439.3  301.54  5459.3  301.06  5534.4  304.74  5639.3  308.99
#Mann= 7 ,-1 , 0
  4586.2     .05       0  4944.9     .16       0  5043.2     .12       0
  5096.3     .07       0  5102.3     .12       0  5141.5     .16       0
  5534.4     .05       0
Bank Sta=4951.5,5049.3
XS Rating Curve= 0 ,0
Exp/Cntr=0.3,0.1

Type RM Length L Ch R = 1 ,35130   ,1121,1121,1121
BEGIN DESCRIPTION:
MORGAN CREEK 61.0
END DESCRIPTION:
XS GIS Cut Line= 2
      3623244.17     10277791.26      3623157.36     10278843.29
#Sta/Elev= 30
  4261.2  308.42  4311.7  307.17    4347  304.14    4352  304.49    4372  302.59
  4442.2  298.69    4468  296.43    4473  296.63  4533.6  293.13  4552.6  292.76
  4602.7  293.33  4622.8  294.83  4652.9  295.88    4673  295.15    4693  292.71
  4813.4  292.97    4860  292.07  4893.7   291.7  4943.9   292.8  4964.2  290.93
    4984  289.96  5001.1   285.6  5003.8   285.1  5007.1   285.6  5024.2  289.97
  5034.2  293.56  5044.2  296.61  5052.1  297.49    5253  303.48  5316.8   304.4
#Mann= 8 ,-1 , 0
  4261.2     .05       0  4533.6     .12       0    4860     .16       0
  4964.2     .12       0  5001.1     .07       0  5007.1     .12       0
  5052.1     .16       0    5253     .05       0
#XS Ineff= 2 , 0
          4652.3  295.89
Permanent Ineff=
       F       F
Bank Sta=4943.9,5034.2
XS Rating Curve= 0 ,0
Exp/Cntr=0.3,0.1

Type RM Length L Ch R = 1 ,34009   ,504,504,504
BEGIN DESCRIPTION:
MORGAN CREEK 60.0
END DESCRIPTION:
XS GIS Cut Line= 3
      3622799.74     10277687.03      3622719.86     10277937.08
      3623011.52     10278895.39
#Sta/Elev= 30
  4436.8  305.22  4547.9  301.86  4754.8  291.81  4881.8   290.1  4913.1  288.89
  4967.6  287.88  4986.3   286.3  4997.4  282.36  5000.2  281.86  5003.4  282.36
 5017.29  288.92  5033.3  289.33  5038.6  288.47  5066.2  290.13  5071.4  292.98
  5104.2  292.01  5143.1  294.28  5226.7  293.94  5268.5  295.26  5273.7  294.42
  5344.6  295.96  5373.5  295.45  5377.5   296.3  5453.3  297.34  5655.4  301.07
  5676.2  301.68  5683.6  299.76  5688.8  300.97  5696.4  299.29    5701  299.29
#Mann= 6 ,-1 , 0
  4436.8     .05       0  4997.4     .03       0  5003.4     .05       0
  5373.5     .16       0  5453.3     .12       0  5655.4     .05       0
#XS Ineff= 2 , 0
                         5028.03          289.45
Permanent Ineff=
       F       F
Bank Sta=4913.1,5017.29
XS Rating Curve= 0 ,0
Exp/Cntr=0.3,0.1

Type RM Length L Ch R = 1 ,33505   ,794,794,794
BEGIN DESCRIPTION:
MORGAN CREEK 59.0
END DESCRIPTION:
XS GIS Cut Line= 2
      3622546.25     10277659.27      3622417.89     10278807.61
#Sta/Elev= 30
  4564.2  304.67  4606.8  303.12  4649.3  302.46  4667.2  301.27  4739.6  299.77
  4829.9  295.49  4888.6  290.71  4908.7  290.72  4920.2  289.47  4938.9   288.8
    4949   288.4  4969.1  283.25  4979.1  282.25  4999.3   282.7  5005.5  282.18
  5007.5  281.01  5010.2  280.51  5013.5  281.01  5029.5  281.77  5039.5  283.29
 5057.42  288.82  5059.6  289.49  5069.7   289.5    5110  288.52  5276.3  292.45
  5401.8  291.57  5421.9  293.39    5442  292.66  5502.4  293.18  5719.7   297.2
#Mann= 3 ,-1 , 0
  4564.2     .05       0  5007.5     .03       0  5013.5     .05       0
#XS Ineff= 2 , 0
                         5067.77          289.54
Permanent Ineff=
       F       F
Bank Sta=4938.9,5057.42
XS Rating Curve= 0 ,0
Exp/Cntr=0.3,0.1

Type RM Length L Ch R = 1 ,32711   ,539,539,539
BEGIN DESCRIPTION:
MORGAN CREEK 58.0
END DESCRIPTION:
XS GIS Cut Line= 3
       3622342.1     10277591.66      3621992.11     10278291.64
      3622046.25     10278933.56
#Sta/Elev= 30
  4211.2  305.09  4558.8  291.02  4703.1  285.68  4770.2  284.43  4806.5  286.77
    4868  284.67    4882  284.77  4890.4  286.17    4896  285.27  4912.8  285.75
  4949.1  283.73    4988  278.37  4990.8  277.87    4994  278.37  5003.8  278.42
  5013.9  280.26  5023.9  286.51    5044  289.53  5104.2  292.82  5124.3  292.67
  5164.4  296.01  5170.9  296.11  5175.9  294.67  5184.5  295.36  5234.7  293.04
  5274.8  292.76    5335  293.35  5365.1  295.56  5410.3  294.67    5638  299.31
#Mann= 4 ,-1 , 0
  4211.2     .05       0  4558.8     .16       0    4988     .07       0
    4994     .16       0
Bank Sta=4912.8,5023.9
XS Rating Curve= 0 ,0
Exp/Cntr=0.3,0.1

Type RM Length L Ch R = 1 ,32172   ,410,410,410
BEGIN DESCRIPTION:
MORGAN CREEK 57.0
END DESCRIPTION:
XS GIS Cut Line= 3
      3622344.82     10277537.79      3621167.78      10278246.1
      3620987.22     10278569.02
#Sta/Elev= 30
  4312.2  305.26  4410.8  303.19  4548.8  295.86  4696.3  289.88  4871.1  286.28
  4954.4   286.7 4969.76  285.12  4987.6  278.09  4990.5  275.68  4993.2  275.18
  4996.5  275.68  5003.2  276.24    5009  279.78  5018.5  281.65  5097.3  285.15
  5284.8  286.93  5300.3  286.87  5315.9  284.45  5352.8  287.07  5365.8  286.98
  5374.1  285.71    5380  286.93  5395.5  286.44  5432.4  289.17  5533.4  292.24
  5680.5  295.64  5715.2  295.49    5752  297.23  5827.4  298.04  6055.9  304.05
#Mann= 5 ,-1 , 0
  4312.2     .05       0  4954.4     .12       0  4990.5     .07       0
  4996.5     .12       0  5018.5     .05       0
#XS Ineff= 2 , 0
                         5299.49          286.91
Permanent Ineff=
       F       F
Bank Sta=4969.76,5097.3
XS Rating Curve= 0 ,0
Exp/Cntr=0.3,0.1

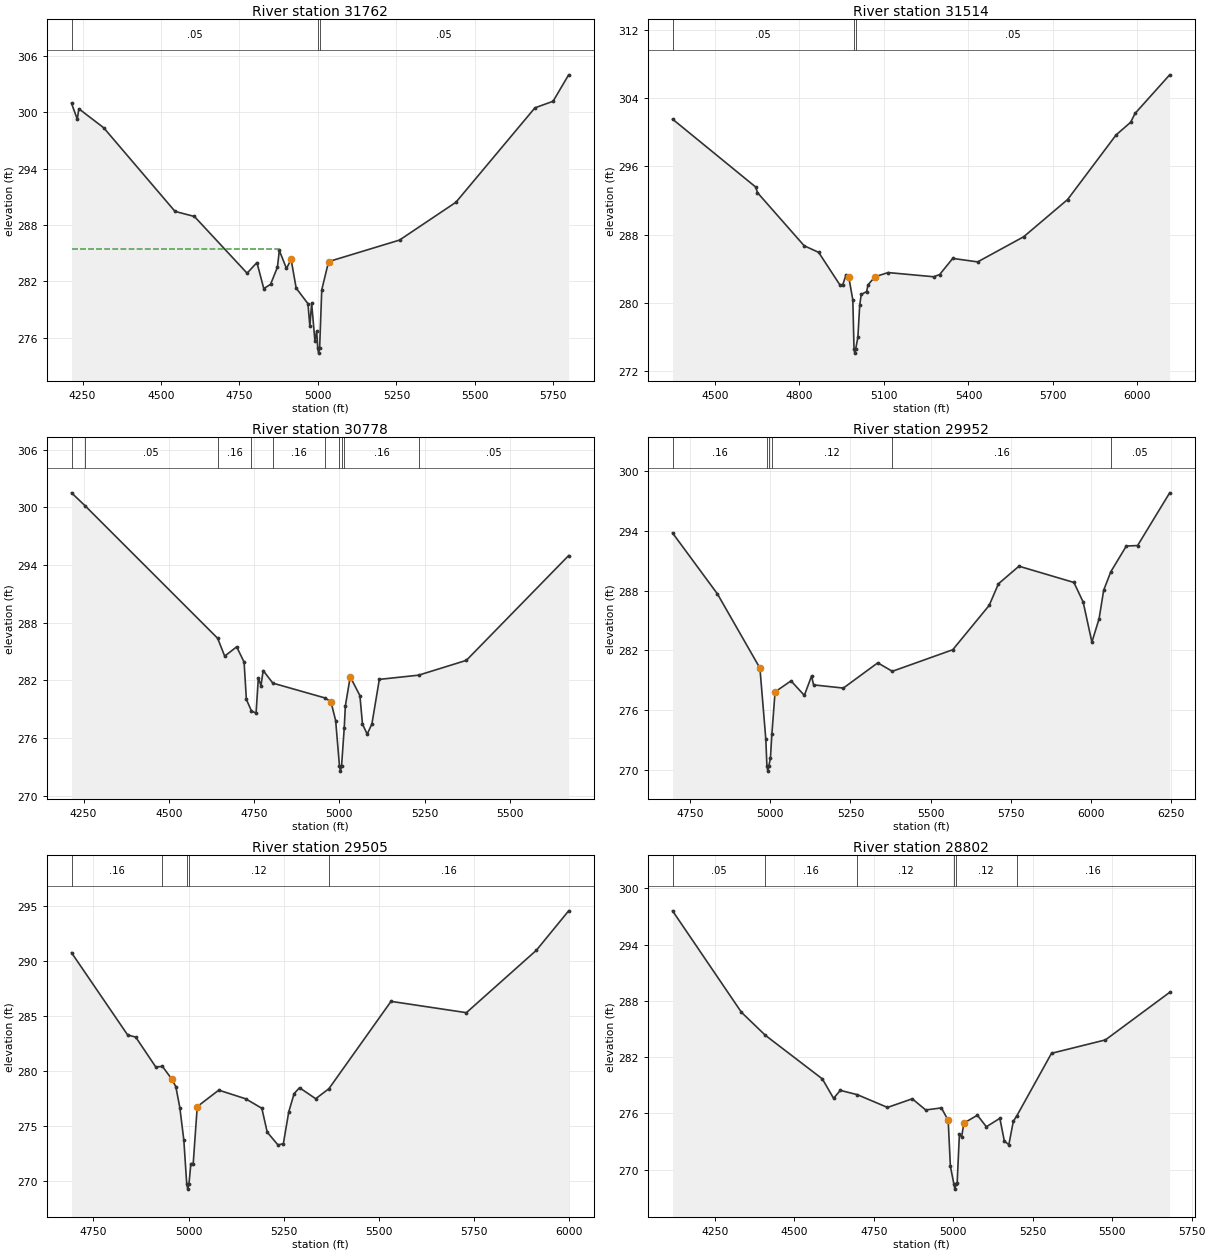
Type RM Length L Ch R = 1 ,31762   ,248,248,248
BEGIN DESCRIPTION:
MORGAN CREEK 56.0
END DESCRIPTION:
XS GIS Cut Line= 5
      3622212.93     10277391.93       3621702.5     10277513.46
      3621278.89      10277746.1      3621004.58     10277947.49
      3620880.27     10278147.77
#Sta/Elev= 30
  4214.8  300.94  4233.1  299.26  4238.2  300.36  4317.4  298.34  4544.6  289.45
  4606.3  288.91  4774.2  282.88  4805.6  284.01  4827.4  281.24  4849.1   281.7
  4870.9  283.52  4876.9   285.3  4899.7  283.38  4914.5  284.34  4930.6  281.29
  4968.1  279.64  4974.2  277.26  4979.9  279.69  4990.3  275.68    4996  276.71
  4999.3  274.88  5002.1  274.38  5005.3  274.88  5012.1  281.11  5033.9  284.11
  5259.9   286.4  5439.6  290.42  5691.3  300.46  5749.2  301.16  5798.8  303.97
#Mann= 3 ,-1 , 0
  4214.8     .05       0  4999.3     .03       0  5005.3     .05       0
#XS Ineff= 2 , 0
         4875.84  285.42
Permanent Ineff=
       F       F
Bank Sta=4914.5,5033.9
XS Rating Curve= 0 ,0
Exp/Cntr=0.3,0.1

Type RM Length L Ch R = 1 ,31514   ,736,736,736
BEGIN DESCRIPTION:
MORGAN CREEK 55.0
END DESCRIPTION:
XS GIS Cut Line= 6
      3622219.84     10277280.83      3621688.61     10277391.94
      3621245.53      10277566.3        3621015.      10277746.1
      3620910.83     10277857.21      3620754.57     10278114.18
#Sta/Elev= 30
  4349.4  301.53  4644.7  293.57    4651  292.91  4816.8  286.69  4868.1  285.92
  4942.9  282.14  4953.7  282.11  4965.1  283.26  4975.2  283.01  4989.5  280.34
  4993.7  274.61  4996.4  274.11  4999.7  274.61  5007.4  275.96  5013.9  279.71
  5019.3  280.98  5038.3  281.32  5043.7  282.12  5068.1  283.06  5114.9  283.55
  5276.1  283.06  5297.6  283.31  5344.3  285.21  5432.6   284.8  5596.3  287.75
  5752.1  292.11  5924.3  299.68  5975.9  301.16  5991.4  302.19  6114.5  306.72
#Mann= 3 ,-1 , 0
  4349.4     .05       0  4993.7     .03       0  4999.7     .05       0
Bank Sta=4975.2,5068.1
XS Rating Curve= 0 ,0
Exp/Cntr=0.3,0.1

Type RM Length L Ch R = 1 ,30778   ,826,826,826
BEGIN DESCRIPTION:
MORGAN CREEK 54.0
END DESCRIPTION:
XS GIS Cut Line= 3
      3621692.13     10276491.61      3621426.44       10276837.
      3620657.96     10277511.41
#Sta/Elev= 30
  4214.6  301.52  4253.9  300.19  4643.2  286.38  4663.9  284.52    4699  285.49
  4720.8   283.9  4727.5  280.01  4742.4  278.82  4755.9  278.58  4762.6  282.26
  4770.2  281.44  4776.8  283.02  4805.1  281.71  4957.8  280.17  4975.4  279.78
  4989.4  277.81  5000.6  273.05  5003.4  272.55  5006.6  273.05  5014.5  277.03
  5017.8  279.33  5032.1  282.37  5060.5  280.41  5068.1  277.44  5081.9   276.4
  5095.7  277.47  5117.5   282.1  5232.8  282.54  5372.7  284.08  5672.8  294.99
#Mann= 10 ,-1 , 0
  4214.6     .16       0  4253.9     .05       0  4643.2     .16       0
  4742.4     .12       0  4805.1     .16       0  4957.8     .12       0
  5000.6     .07       0  5006.6     .12       0  5014.5     .16       0
  5232.8     .05       0
Bank Sta=4975.4,5032.1
XS Rating Curve= 0 ,0
Exp/Cntr=0.3,0.1

Type RM Length L Ch R = 1 ,29952   ,447,447,447
BEGIN DESCRIPTION:
MORGAN CREEK 52.0
END DESCRIPTION:
XS GIS Cut Line= 3
      3621342.06     10276241.66      3621092.11     10276341.64
      3620292.13     10277341.61
#Sta/Elev= 30
  4695.5  293.77  4835.5  287.66  4967.9  280.23  4986.3   273.1  4989.7  270.41
  4992.5  269.91  4995.7  270.41  5000.7  271.25  5005.2  273.63  5015.1  277.85
  5064.8  278.95  5106.4   277.5  5128.8  279.43  5135.2  278.55    5228  278.23
  5335.3  280.76  5380.6  279.91    5569  282.07  5682.7  286.52  5711.5  288.68
  5775.5  290.44  5946.8  288.81  5975.6  286.85  6002.8  282.84  6025.2  285.17
  6039.6  288.04  6061.9  289.89  6110.1  292.46  6145.3  292.51  6245.3  297.79
#Mann= 6 ,-1 , 0
  4695.5     .16       0  4989.7     .07       0  4995.7     .16       0
  5005.2     .12       0  5380.6     .16       0  6061.9     .05       0
Bank Sta=4967.9,5015.1
XS Rating Curve= 0 ,0
Exp/Cntr=0.3,0.1

Type RM Length L Ch R = 1 ,29505   ,703,703,703
BEGIN DESCRIPTION:
MORGAN CREEK 51.0
END DESCRIPTION:
XS GIS Cut Line= 3
      3621142.07     10275941.65      3620842.11     10276041.64
      3620142.13     10276741.61
#Sta/Elev= 30
  4692.4  290.76  4839.9  283.27    4861  283.08  4913.7  280.36  4931.3  280.41
  4955.9  279.25  4966.4  278.57    4977  276.65  4987.5  273.69    4995  269.74
  4997.8  269.24    5001  269.74    5006  271.56  5012.1  271.56  5022.7  276.75
  5079.3  278.25    5150  277.46  5192.4   276.6  5206.6  274.42  5234.9  273.26
    5249  273.38  5263.1  276.27  5277.3  277.94  5291.4  278.47  5333.9  277.47
  5368.6  278.38  5531.8  286.33  5729.8   285.3  5913.7  290.98  5998.5  294.57
#Mann= 5 ,-1 , 0
  4692.4     .16       0  4931.3     .12       0    4995     .07       0
    5001     .12       0  5368.6     .16       0
Bank Sta=4955.9,5022.7
XS Rating Curve= 0 ,0
Exp/Cntr=0.3,0.1

Type RM Length L Ch R = 1 ,28802   ,742,742,742
BEGIN DESCRIPTION:
MORGAN CREEK 49.0
END DESCRIPTION:
XS GIS Cut Line= 2
      3620998.51     10275281.33      3619902.62     10276398.03
#Sta/Elev= 30
  4116.2  297.59  4333.1  286.77  4408.3  284.32  4587.7  279.67    4623   277.6
  4644.2  278.45  4697.7  277.99  4792.7  276.63  4870.6  277.55    4913  276.36
  4962.4  276.58  4983.7  275.25  4990.7  270.34  5001.9  268.42  5004.6  267.92
  5007.9  268.42    5012  268.62    5019  273.76  5026.1   273.5  5033.1  274.96
  5075.6   275.8  5103.9  274.57  5146.3  275.47  5160.4  273.06  5174.6  272.65
  5188.7  275.15  5199.6  275.73  5308.9   282.4  5478.6  283.83  5680.8   288.9
#Mann= 6 ,-1 , 0
  4116.2     .05       0  4408.3     .16       0  4697.7     .12       0
  5001.9     .07       0  5007.9     .12       0  5199.6     .16       0
Bank Sta=4983.7,5033.1
XS Rating Curve= 0 ,0
Exp/Cntr=0.3,0.1

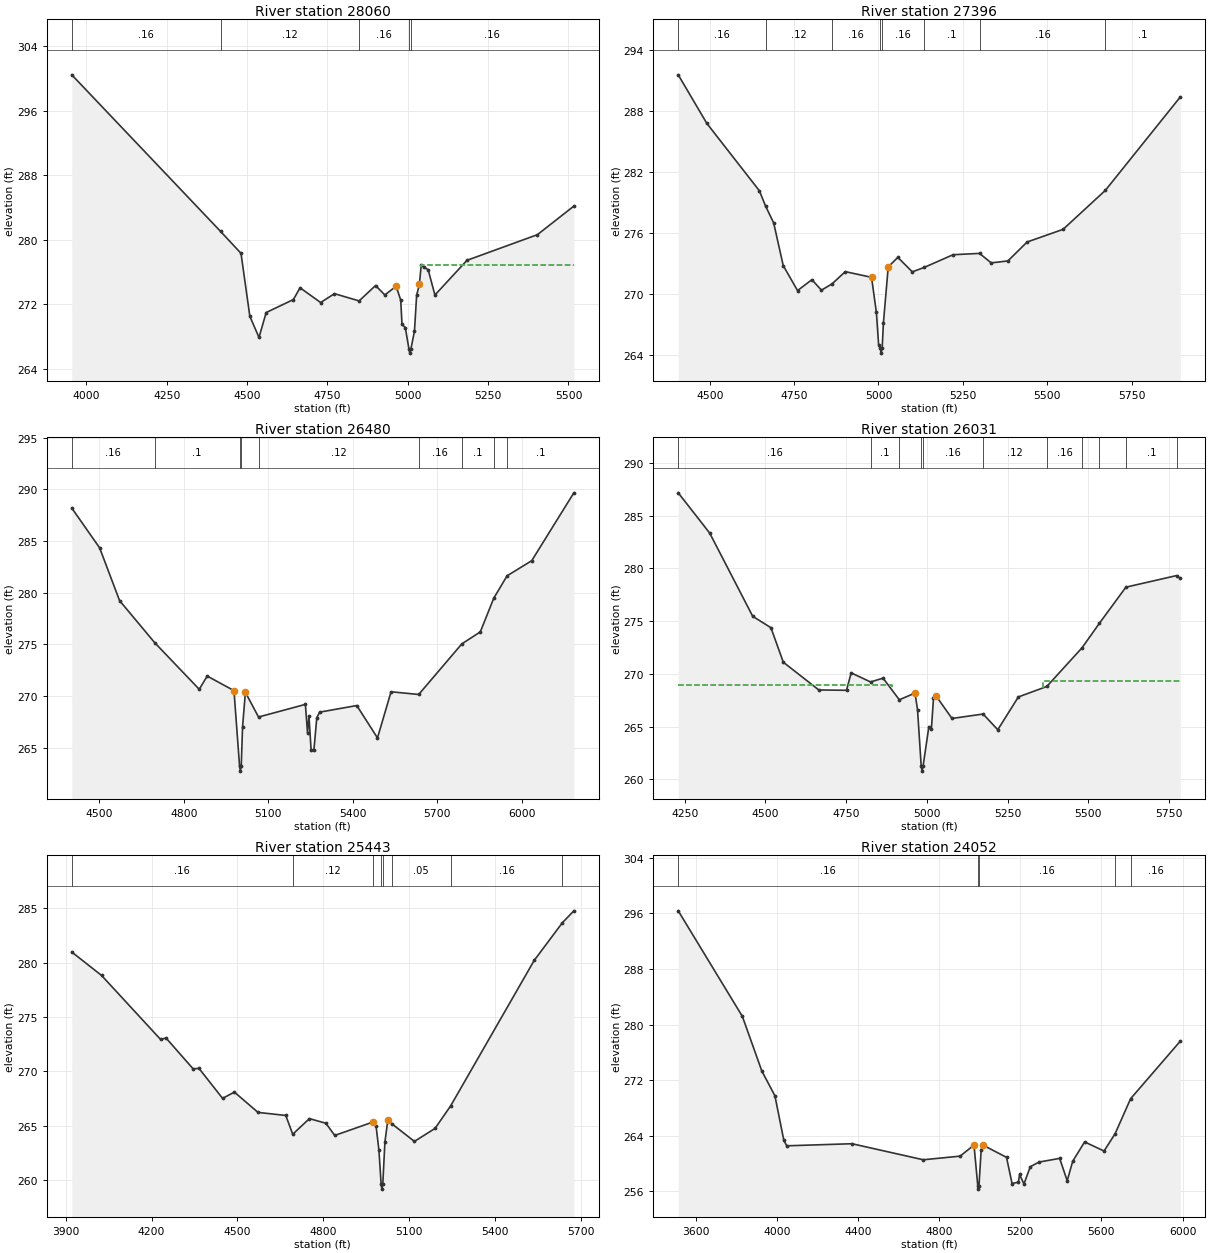
Type RM Length L Ch R = 1 ,28060   ,664,664,664
BEGIN DESCRIPTION:
MORGAN CREEK 48.0
END DESCRIPTION:
XS GIS Cut Line= 3
      3620792.14     10274941.61      3619992.11     10275591.64
      3619642.13     10275991.62
#Sta/Elev= 30
  3954.5  300.43  4417.4  281.03  4481.1  278.31  4508.6  270.51  4537.1  267.88
  4559.4  270.97  4644.1  272.58  4664.9  274.04  4728.9  272.21    4772  273.31
  4848.5  272.41  4899.8  274.32  4928.6  273.15  4963.8  274.23  4978.1  272.51
  4982.1  269.49  4992.4  269.11  5003.7  266.44  5006.4  265.94  5009.7  266.44
  5020.9  268.68  5027.6  273.11 5036.16  274.46  5041.8  276.81  5049.4  276.65
  5063.6  276.26  5084.5  273.14  5184.2  277.44  5403.4  280.62  5516.8  284.16
#Mann= 5 ,-1 , 0
  3954.5     .16       0  4417.4     .12       0  4848.5     .16       0
  5003.7     .07       0  5009.7     .16       0
#XS Ineff= 2 , 0
                         5041.27          276.86
Permanent Ineff=
       F       F
Bank Sta=4963.8,5036.16
XS Rating Curve= 0 ,0
Exp/Cntr=0.3,0.1

Type RM Length L Ch R = 1 ,27396   ,916,916,916
BEGIN DESCRIPTION:
MORGAN CREEK 47.0
END DESCRIPTION:
XS GIS Cut Line= 3
       3620392.1     10274791.65      3619992.11     10275191.64
      3619392.12     10275891.62
#Sta/Elev= 30
  4406.7  291.52  4491.5  286.75  4647.1  280.14  4665.3  278.65  4689.5  276.98
  4717.8  272.79  4760.2  270.34  4802.7  271.41    4831  270.38  4862.4     271
  4901.7   272.2  4979.5  271.64  4993.8  268.19  5000.4  265.04    5005   264.7
  5007.8   264.2    5011   264.7  5014.6  267.16  5028.9  272.67  5057.4   273.6
  5100.2  272.18  5135.3  272.61    5221  273.86  5299.4  273.99    5334  273.06
  5383.4  273.25  5440.5  275.11  5546.9  276.35    5672  280.17  5894.3  289.35
#Mann= 8 ,-1 , 0
  4406.7     .16       0  4665.3     .12       0  4862.4     .16       0
    5005     .07       0    5011     .16       0  5135.3      .1       0
  5299.4     .16       0    5672      .1       0
Bank Sta=4979.5,5028.9
XS Rating Curve= 0 ,0
Exp/Cntr=0.3,0.1

Type RM Length L Ch R = 1 ,26480   ,449,449,449
BEGIN DESCRIPTION:
MORGAN CREEK 45.0
END DESCRIPTION:
XS GIS Cut Line= 3
      3619942.07     10274291.68      3619542.11     10274691.64
       3619342.1     10275891.65
#Sta/Elev= 30
  4402.5  288.19  4501.4  284.34  4572.2  279.24  4697.1  275.17    4855  270.67
  4883.3  271.95  4978.3  270.54  4998.1  263.26  5000.8  262.76  5004.1  263.26
  5008.7  267.03  5018.8  270.38  5065.4  267.99  5231.7  269.21  5239.3  266.47
  5244.4  268.12    5252  264.82  5262.1  264.81  5272.3  267.93  5282.4  268.46
  5414.2   269.1  5487.7  265.97  5535.9  270.43    5634  270.17  5787.1  275.06
  5852.7  276.22  5900.5  279.48  5947.8  281.64  6035.2   283.1  6184.7  289.66
#Mann= 9 ,-1 , 0
  4402.5     .16       0  4697.1      .1       0  4998.1     .07       0
  5004.1      .1       0  5065.4     .12       0    5634     .16       0
  5787.1      .1       0  5900.5     .16       0  5947.8      .1       0
Bank Sta=4978.3,5018.8
XS Rating Curve= 0 ,0
Exp/Cntr=0.3,0.1

Type RM Length L Ch R = 1 ,26031   ,588,588,588
BEGIN DESCRIPTION:
MORGAN CREEK 44.0
END DESCRIPTION:
XS GIS Cut Line= 3
      3619811.04     10274156.33      3619415.16     10274288.29
      3618540.61     10275017.08
#Sta/Elev= 30
  4229.7  287.16  4327.1  283.35  4460.5  275.46  4516.9  274.38  4555.3  271.11
  4665.3  268.48  4751.2  268.45  4765.5   270.1  4825.7  269.24  4864.4   269.6
  4914.8  267.55  4963.4  268.19  4971.2   266.6  4982.5  261.29  4985.2  260.79
  4988.5  261.29  5006.3  265.01  5014.1  264.78  5020.6  267.69  5028.4  267.92
  5077.9  265.78  5174.4   266.2  5219.8  264.71  5283.6  267.82  5371.7  268.81
    5481  272.48  5534.7   274.8  5616.8  278.22    5774  279.32  5785.4  279.05
#Mann= 11 ,-1 , 0
  4229.7     .16       0  4825.7      .1       0  4914.8     .16       0
  4982.5     .07       0  4988.5     .16       0  5174.4     .12       0
  5371.7     .16       0    5481      .1       0  5534.7     .16       0
  5616.8      .1       0    5774     .05       0
#XS Ineff= 2 , 0
         4893.12  268.97 5359.75          269.35
Permanent Ineff=
       F       F
Bank Sta=4963.4,5028.4
XS Rating Curve= 0 ,0
Exp/Cntr=0.3,0.1

Type RM Length L Ch R = 1 ,25443   ,1391,1391,1391
BEGIN DESCRIPTION:
MORGAN CREEK 42.0
END DESCRIPTION:
XS GIS Cut Line= 2
      3619783.22     10273906.35      3618081.86     10274329.95
#Sta/Elev= 30
  3921.4  280.99  4025.6  278.83  4231.7  272.94  4250.5  273.08  4345.1  270.24
  4365.7  270.28  4448.1  267.52  4489.3   268.1  4571.8  266.23  4668.7  265.95
    4693  264.22  4751.3  265.66  4808.8  265.23  4839.7  264.11  4972.7  265.34
  4973.7  265.33    4984  264.98    4994  262.76  5001.6  259.67  5004.4  259.17
  5007.6  259.67  5014.9  263.51  5025.2  265.53  5038.9  265.19  5117.9  263.56
  5190.1  264.76  5244.5  266.83  5536.1  280.21  5634.8  283.69  5674.7  284.78
#Mann= 8 ,-1 , 0
  3921.4     .16       0    4693     .12       0  4972.7     .16       0
  5001.6     .07       0  5007.6     .16       0  5038.9     .05       0
  5244.5     .16       0  5634.8     .05       0
Bank Sta=4973.7,5025.2
XS Rating Curve= 0 ,0
Exp/Cntr=0.3,0.1

Type RM Length L Ch R = 1 ,24052   ,747,747,747
BEGIN DESCRIPTION:
MORGAN CREEK 40.0
END DESCRIPTION:
XS GIS Cut Line= 2
      3619345.73     10271961.88      3618096.42     10274099.59
#Sta/Elev= 30
  3513.1  296.38  3829.4  281.17  3925.3  273.31  3989.8  269.74    4034   263.3
  4048.4  262.53  4369.9  262.83  4721.3  260.52  4903.1  261.04  4971.7  262.64
  4990.2  256.79  4992.9  256.29  4996.2  256.79    5007  261.93  5014.7  262.65
    5132  260.87  5159.3   257.1  5190.7   257.3  5196.5   258.4    5218  257.03
  5249.4  259.52  5292.4  260.19  5394.1  260.72  5431.3   257.5  5458.7  260.32
  5517.2  263.09  5613.1  261.78  5667.3  264.26  5744.1  269.32  5989.1  277.61
#Mann= 5 ,-1 , 0
  3513.1     .16       0  4990.2     .07       0  4996.2     .16       0
  5667.3      .1       0  5744.1     .16       0
Bank Sta=4971.7,5014.7
XS Rating Curve= 0 ,0
Exp/Cntr=0.3,0.1

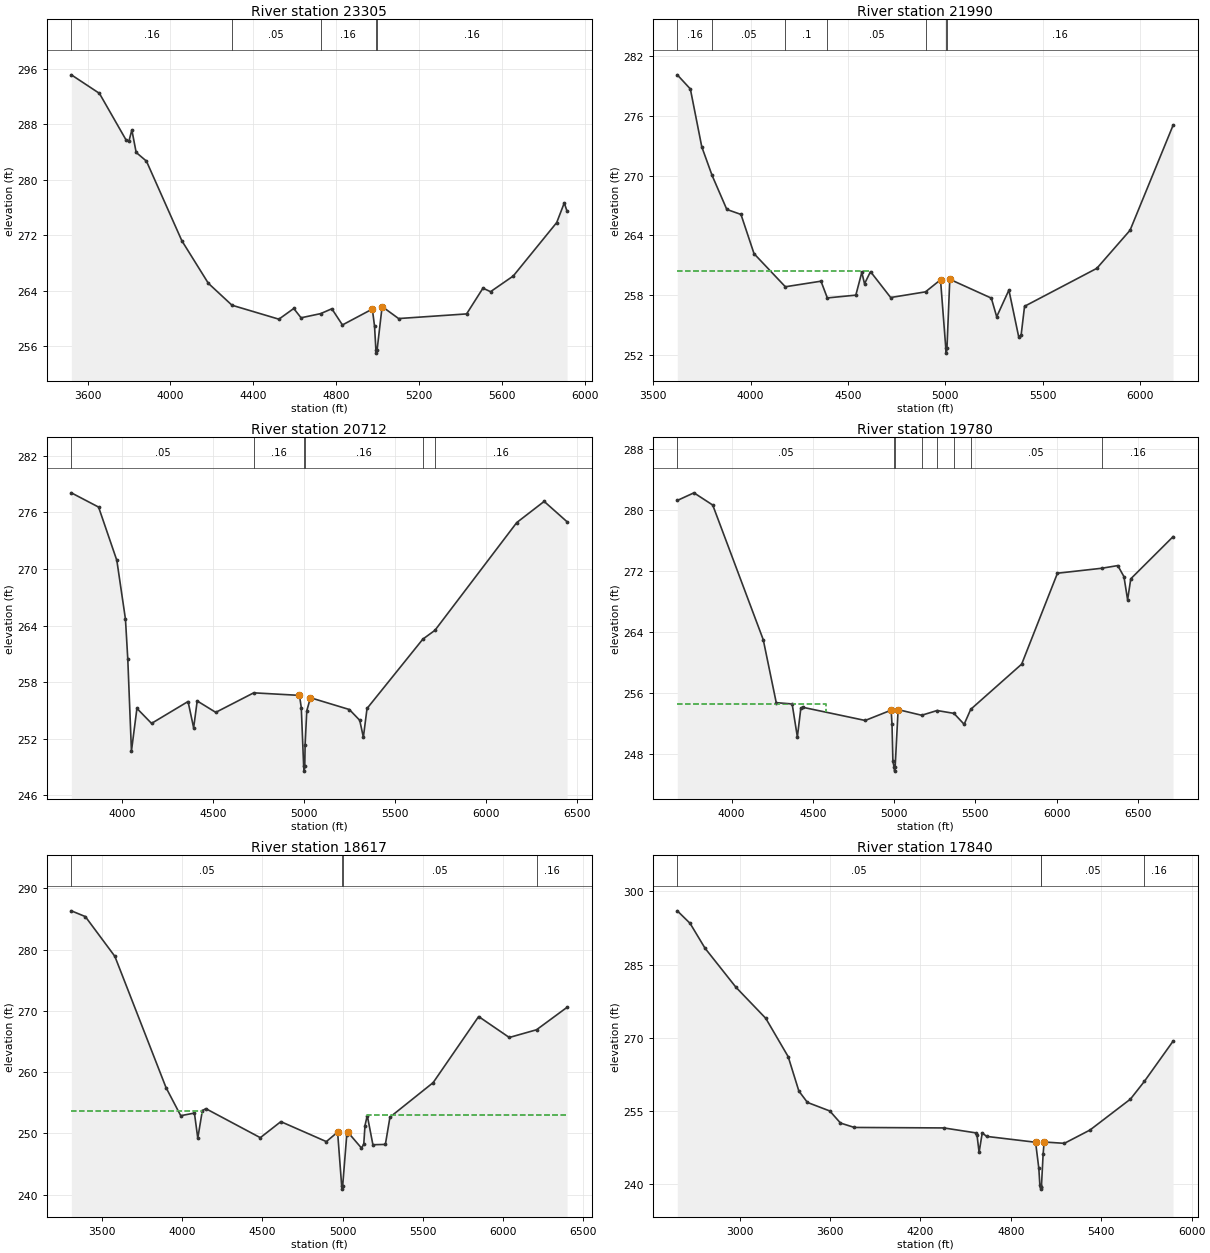
Type RM Length L Ch R = 1 ,23305   ,1315,1315,1315
BEGIN DESCRIPTION:
MORGAN CREEK 38.0
END DESCRIPTION:
XS GIS Cut Line= 3
      3619054.04      10271913.3      3618142.11     10273041.64
       3617642.1     10273841.65
#Sta/Elev= 30
  3521.5  295.13  3657.1  292.46    3785  285.79  3799.4  285.56  3813.8  287.18
  3834.6  283.95  3884.2   282.7  4055.2  271.23  4183.2   265.1  4297.4  261.94
  4523.8  259.93  4595.7  261.47  4630.9  260.13  4725.4  260.73  4779.6  261.43
  4830.7   259.1  4975.2  261.39  4985.8  258.92  4992.3  255.54    4995  255.04
  4998.3  255.54  5022.4  261.75    5102  260.02  5430.4  260.69  5509.4   264.4
    5546  263.89  5655.7  266.15  5865.6  273.85  5902.1  276.68  5915.7  275.46
#Mann= 5 ,-1 , 0
  3521.5     .16       0  4297.4     .05       0  4725.4     .16       0
  4992.3     .07       0  4998.3     .16       0
Bank Sta=4975.2,5022.4
XS Rating Curve= 0 ,0
Exp/Cntr=0.3,0.1

Type RM Length L Ch R = 1 ,21990   ,1278,1278,1278
BEGIN DESCRIPTION:
MORGAN CREEK 35.0
END DESCRIPTION:
XS GIS Cut Line= 3
       3617992.1     10271391.65      3617392.11     10272591.64
       3617292.1     10273791.65
#Sta/Elev= 30
  3623.8  280.11  3690.9  278.69  3749.6  272.88  3802.6  270.01  3878.1   266.6
  3950.8   266.1  4017.9  262.16  4178.7  258.84  4361.7   259.4  4394.2  257.72
  4540.6     258  4571.3  260.29  4585.3  259.14    4616  260.36  4719.5  257.76
  4898.4  258.33  4975.5  259.54  5002.6  252.68  5005.3  252.18  5008.6  252.68
  5023.1  259.59  5236.4   257.7    5264  255.83  5326.7  258.51  5376.8  253.83
  5389.4  253.98    5407  256.88  5778.2  260.69  5948.8  264.51  6169.6  275.04
#Mann= 7 ,-1 , 0
  3623.8     .16       0  3802.6     .05       0  4178.7      .1       0
  4394.2     .05       0  4898.4     .16       0  5002.6     .07       0
  5008.6     .16       0
#XS Ineff= 2 , 0
         4615.41  260.38
Permanent Ineff=
       F       F
Bank Sta=4975.5,5023.1
XS Rating Curve= 0 ,0
Exp/Cntr=0.3,0.1

Type RM Length L Ch R = 1 ,20712   ,932,932,932
BEGIN DESCRIPTION:
MORGAN CREEK 33.0
END DESCRIPTION:
XS GIS Cut Line= 2
      3616602.66     10271142.46      3616824.84     10273857.18
#Sta/Elev= 30
  3720.7  278.07  3870.4  276.56  3970.7  270.91  4018.1  264.68  4030.9  260.44
    4051   250.7  4081.1  255.22  4161.4  253.63    4362  255.95  4392.7  253.16
  4412.2  256.01  4514.2   254.8  4722.8  256.87  4974.1   256.6  4984.1   255.3
  4997.2  249.07  4999.9  248.57  5003.2  249.07  5005.2  251.38  5014.2  254.95
  5034.3  256.35  5248.2   255.1  5305.2  253.96  5325.2  252.16  5345.3  255.21
  5651.9  262.56  5718.6   263.5    6168  274.92  6318.5  277.16  6444.5     275
#Mann= 6 ,-1 , 0
  3720.7     .05       0  4722.8     .16       0  4997.2     .07       0
  5003.2     .16       0  5651.9      .1       0  5718.6     .16       0
Bank Sta=4974.1,5034.3
XS Rating Curve= 0 ,0
Exp/Cntr=0.3,0.1

Type RM Length L Ch R = 1 ,19780   ,1163,1163,1163
BEGIN DESCRIPTION:
MORGAN CREEK 31.0
END DESCRIPTION:
XS GIS Cut Line= 2
      3616533.22      10271010.5      3615456.97      10273864.3
#Sta/Elev= 30
  3665.8   281.2  3768.3   282.2  3883.8   280.6  4194.6  262.98  4274.6  254.74
  4372.4  254.57  4404.5  250.25  4425.8     254  4436.5  254.14  4821.7  252.41
  4981.5  253.76  4986.8   251.9  4992.3  247.05    5000  246.28  5002.7  245.78
    5006  246.28  5024.3  253.83  5169.2  253.09  5264.2  253.71  5367.7  253.34
  5430.5  251.91  5471.1  253.87  5784.4  259.78  6004.6  271.68  6277.6  272.33
  6375.8  272.68  6413.7  271.23  6436.2   268.2  6455.7  270.95  6715.8  276.46
#Mann= 8 ,-1 , 0
  3665.8     .05       0    5000     .04       0    5006     .05       0
  5169.2     .16       0  5264.2     .05       0  5367.7     .16       0
  5471.1     .05       0  6277.6     .16       0
#XS Ineff= 2 , 0
         4582.43  254.51
Permanent Ineff=
       F       F
Bank Sta=4981.5,5024.3
XS Rating Curve= 0 ,0
Exp/Cntr=0.3,0.1

Type RM Length L Ch R = 1 ,18617   ,777,777,777
BEGIN DESCRIPTION:
MORGAN CREEK 29.0
END DESCRIPTION:
XS GIS Cut Line= 2
      3616408.24     10270954.93      3614352.64     10273260.53
#Sta/Elev= 30
  3309.4  286.34  3396.7   285.4  3580.6  278.91  3899.2  257.49  3991.1  252.89
  4076.4  253.32  4097.3  249.22  4125.7  253.72  4147.5  254.04  4486.9   249.3
  4614.8  251.92  4898.3  248.66  4968.5  250.21  4993.9   241.4  4996.7   240.9
  4999.9   241.4  5025.4  249.74  5032.9  250.18  5117.3   247.6  5131.5  248.25
  5139.1  251.28  5153.3  252.92  5188.4  248.15  5266.1   248.2  5294.6  252.65
  5563.8  258.29  5847.2  269.08  6038.1  265.66  6207.9  266.92  6398.3  270.59
#Mann= 4 ,-1 , 0
  3309.4     .05       0  4993.9     .03       0  4999.9     .05       0
  6207.9     .16       0
#XS Ineff= 2 , 0
         4122.23   253.7 5152.93          253.02
Permanent Ineff=
       F       F
Bank Sta=4968.5,5032.9
XS Rating Curve= 0 ,0
Exp/Cntr=0.3,0.1

Type RM Length L Ch R = 1 ,17840   ,915,915,915
BEGIN DESCRIPTION:
MORGAN CREEK 27.0
END DESCRIPTION:
XS GIS Cut Line= 3
      3616342.14     10270391.61      3614542.11     10272041.64
       3613942.1     10272641.65
#Sta/Elev= 30
  2586.2  295.99    2671  293.43  2770.3  288.34  2975.6  280.35  3173.6  273.99
  3322.2  266.15  3393.1  259.12  3449.8  256.79  3598.4  255.04  3669.3  252.57
  3761.2  251.67  4355.6  251.57  4567.8  250.56  4575.2  250.16  4589.3  246.57
  4610.3  250.58  4638.7  249.84  4964.2  248.64  4985.8  243.28  4992.6  239.84
    4997  239.55  4999.8  239.05    5003  239.55  5014.2   246.2    5021  248.69
  5155.3  248.42  5325.1  251.14  5593.8  257.47  5686.1  261.09  5876.6  269.32
#Mann= 4 ,-1 , 0
  2586.2     .05       0    4997     .03       0    5003     .05       0
  5686.1     .16       0
Bank Sta=4964.2,5021
XS Rating Curve= 0 ,0
Exp/Cntr=0.3,0.1

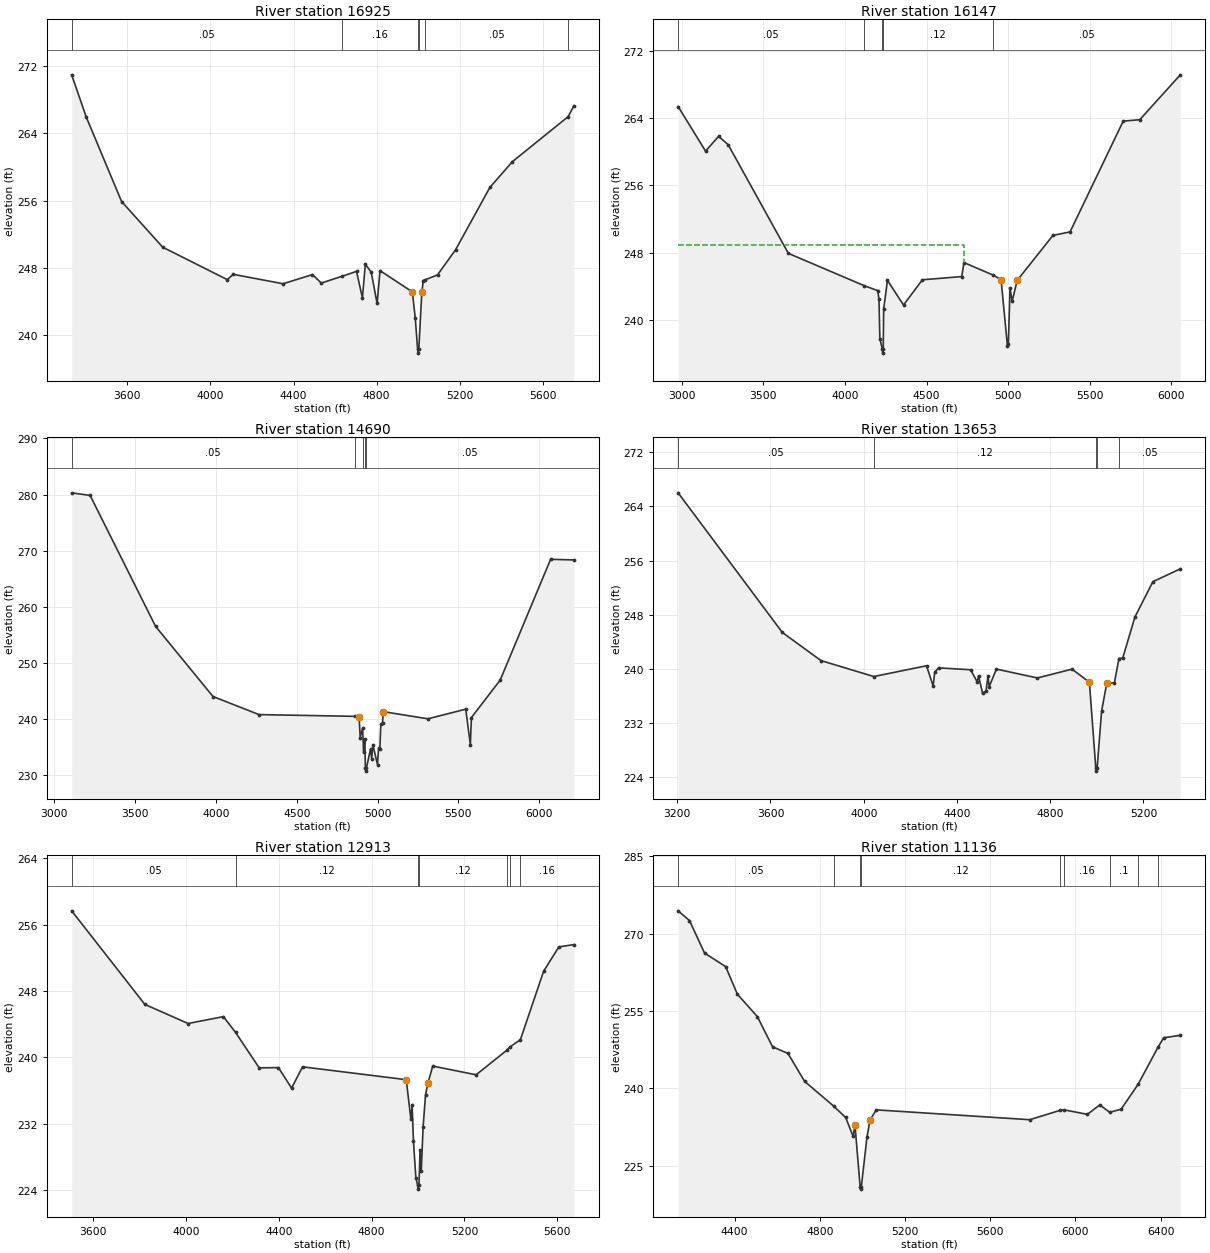
Type RM Length L Ch R = 1 ,16925   ,778,778,778
BEGIN DESCRIPTION:
MORGAN CREEK 25.0
END DESCRIPTION:
XS GIS Cut Line= 3
      3615142.11     10270241.63      3613942.11     10271441.64
      3613542.09     10272041.66
#Sta/Elev= 30
  3331.6  270.97  3402.3  265.92    3572  255.89    3770  250.45  4081.1  246.59
  4109.4  247.22  4349.8   246.1  4491.3  247.19  4533.7  246.18  4631.4  246.97
  4703.4  247.57  4731.7  244.41  4745.8  248.42  4774.1  247.48  4802.4  243.75
  4816.5  247.66  4972.1  245.13  4986.2  242.03  4997.4  238.34  5000.1  237.84
  5003.4  238.34 5017.62  245.06  5025.1  246.47  5034.7  246.58  5093.3  247.15
  5180.4  250.15  5345.7  257.57  5453.8  260.63  5722.2  265.99  5749.8  267.28
#Mann= 6 ,-1 , 0
  3331.6     .05       0  4631.4     .16       0  4997.4     .07       0
  5003.4     .16       0  5034.7     .05       0  5722.2      .1       0
Bank Sta=4972.1,5017.62
XS Rating Curve= 0 ,0
Exp/Cntr=0.3,0.1

Type RM Length L Ch R = 1 ,16147   ,1457,1457,1457
BEGIN DESCRIPTION:
MORGAN CREEK 23.0
END DESCRIPTION:
XS GIS Cut Line= 4
      3614192.95     10269232.71       3613922.1     10269691.07
      3613179.05     10271357.73      3613299.74     10272066.43
#Sta/Elev= 30
    2978   265.4    3146  260.09  3225.9  261.85  3284.5  260.86  3653.4  247.92
  4118.8  244.07  4200.8  243.49  4208.3  242.48  4213.8  237.79  4228.5  236.55
  4231.3  236.05  4234.5  236.55    4237  241.26  4260.2  244.71  4358.6  241.78
  4474.5  244.78  4715.4  245.16  4728.9  246.83  4909.7  245.32  4956.3  244.78
  4995.4  236.89  5000.9  237.14    5011  243.78  5024.1  242.21  5054.8   244.7
  5273.8  250.06  5378.9  250.48  5704.4  263.66  5805.8  263.83  6054.1  269.17
#Mann= 5 ,-1 , 0
    2978     .05       0  4118.8     .12       0  4228.5     .03       0
  4234.5     .12       0  4909.7     .05       0
#XS Ineff= 2 , 0
       0 4729.55  248.87               0
Permanent Ineff=
       F       F
Bank Sta=4956.3,5054.8
XS Rating Curve= 0 ,0
Exp/Cntr=0.3,0.1

Type RM Length L Ch R = 1 ,14690   ,1037,1037,1037
BEGIN DESCRIPTION:
MORGAN CREEK 20.0
END DESCRIPTION:
XS GIS Cut Line= 3
      3613942.08     10269041.66      3612442.11     10270241.64
       3611675.9     10271148.35
#Sta/Elev= 30
  3106.8   280.3  3221.2  279.83  3626.2  256.46  3981.6  243.94  4266.5  240.71
  4859.7   240.4    4886  240.36  4892.4   236.6  4907.6  238.32  4913.3  234.07
  4921.3  236.33  4924.7  231.12  4927.4  230.62  4930.7  231.12  4956.5  234.57
  4963.7  232.87  4970.9  235.36  4999.7  231.79  5006.1  234.67  5014.1  234.61
  5020.5  238.97    5031   239.2  5034.9  241.24  5311.8  239.96  5545.8  241.68
  5574.4  235.37  5580.9  240.18    5759  246.87    6071  268.43  6214.8  268.32
#Mann= 5 ,-1 , 0
  3106.8     .05       0  4859.7     .12       0  4907.6     .05       0
  4924.7     .03       0  4930.7     .05       0
Bank Sta=4886,5034.9
XS Rating Curve= 0 ,0
Exp/Cntr=0.3,0.1

Type RM Length L Ch R = 1 ,13653   ,740,740,740
BEGIN DESCRIPTION:
MORGAN CREEK 18.0
END DESCRIPTION:
XS GIS Cut Line= 2
      3613422.11     10269059.12      3611465.41     10269961.15
#Sta/Elev= 30
  3203.7  266.01  3650.6  245.41  3816.8  241.25  4043.4   238.9  4269.5  240.49
  4297.9  237.49  4304.8  239.55  4320.9  240.18  4458.6   239.9  4487.1  238.09
  4492.6  239.01    4510  236.41  4525.1   236.8    4533  238.97  4538.5  237.41
  4569.1     240  4745.1  238.69  4893.8  239.99  4968.2  238.06  4995.6  225.44
  4998.3  224.94  5001.6  225.44  5020.6  233.81  5042.6  237.88  5075.6  237.98
  5095.1  241.56  5111.4  241.64  5163.7   247.7  5240.8   252.9  5358.3  254.79
#Mann= 5 ,-1 , 0
  3203.7     .05       0  4043.4     .12       0  4995.6     .07       0
  5001.6     .12       0  5095.1     .05       0
Bank Sta=4968.2,5042.6
XS Rating Curve= 0 ,0
Exp/Cntr=0.3,0.1

Type RM Length L Ch R = 1 ,12913   ,1777,1777,1777
BEGIN DESCRIPTION:
MORGAN CREEK 16.0
END DESCRIPTION:
XS GIS Cut Line= 2
      3613199.92     10268781.34      3611116.83      10269364.6
#Sta/Elev= 30
    3508  257.65  3823.4  246.37  4009.6  244.07  4161.7   244.9    4214     243
  4315.7  238.73  4398.8  238.75  4455.4  236.28  4502.6  238.85  4949.2   237.3
  4969.4  232.52  4974.6   234.3  4980.3   229.9  4990.7  225.51  4998.1  224.61
  5000.9  224.11  5004.1  224.61  5008.7  228.85  5013.9  226.26  5021.9  231.59
  5032.3  235.46  5042.6  236.88  5063.4  238.94  5250.3  237.89  5382.1  240.84
  5394.6  241.21  5441.1  242.13  5541.1  250.37  5606.6   253.3  5671.2  253.58
#Mann= 7 ,-1 , 0
    3508     .05       0    4214     .12       0  4998.1     .07       0
  5004.1     .12       0  5382.1     .16       0  5394.6     .05       0
  5441.1     .16       0
Bank Sta=4949.2,5042.6
XS Rating Curve= 0 ,0
Exp/Cntr=0.3,0.1

Type RM Length L Ch R = 1 ,11136   ,883,883,883
BEGIN DESCRIPTION:
MORGAN CREEK 13.0
END DESCRIPTION:
XS GIS Cut Line= 3
      3612239.31     10267083.32      3612039.33     10267283.31
      3610792.12     10268941.62
#Sta/Elev= 30
  4134.6  274.43    4188  272.54  4258.7  266.24  4357.7  263.62  4412.7  258.27
  4506.7  253.91    4578  248.07  4650.4  246.78  4728.1  241.38  4865.1  236.56
  4921.2  234.36  4956.6  230.68  4964.9  232.96    4989  220.97  4991.7  220.47
    4995  220.97  5021.1  230.51  5035.7  233.85  5064.8  235.84  5785.4  233.93
  5928.3  235.75  5947.1  235.84  6056.1  234.97  6114.4   236.8  6160.7  235.37
  6214.4  235.96  6293.8  240.76  6387.7  247.98  6414.3  249.82  6492.4  250.29
#Mann= 9 ,-1 , 0
  4134.6     .05       0  4865.1     .12       0    4989     .07       0
    4995     .12       0  5928.3      .1       0  5947.1     .16       0
  6160.7      .1       0  6293.8     .05       0  6387.7     .16       0
Bank Sta=4964.9,5035.7
XS Rating Curve= 0 ,0
Exp/Cntr=0.3,0.1