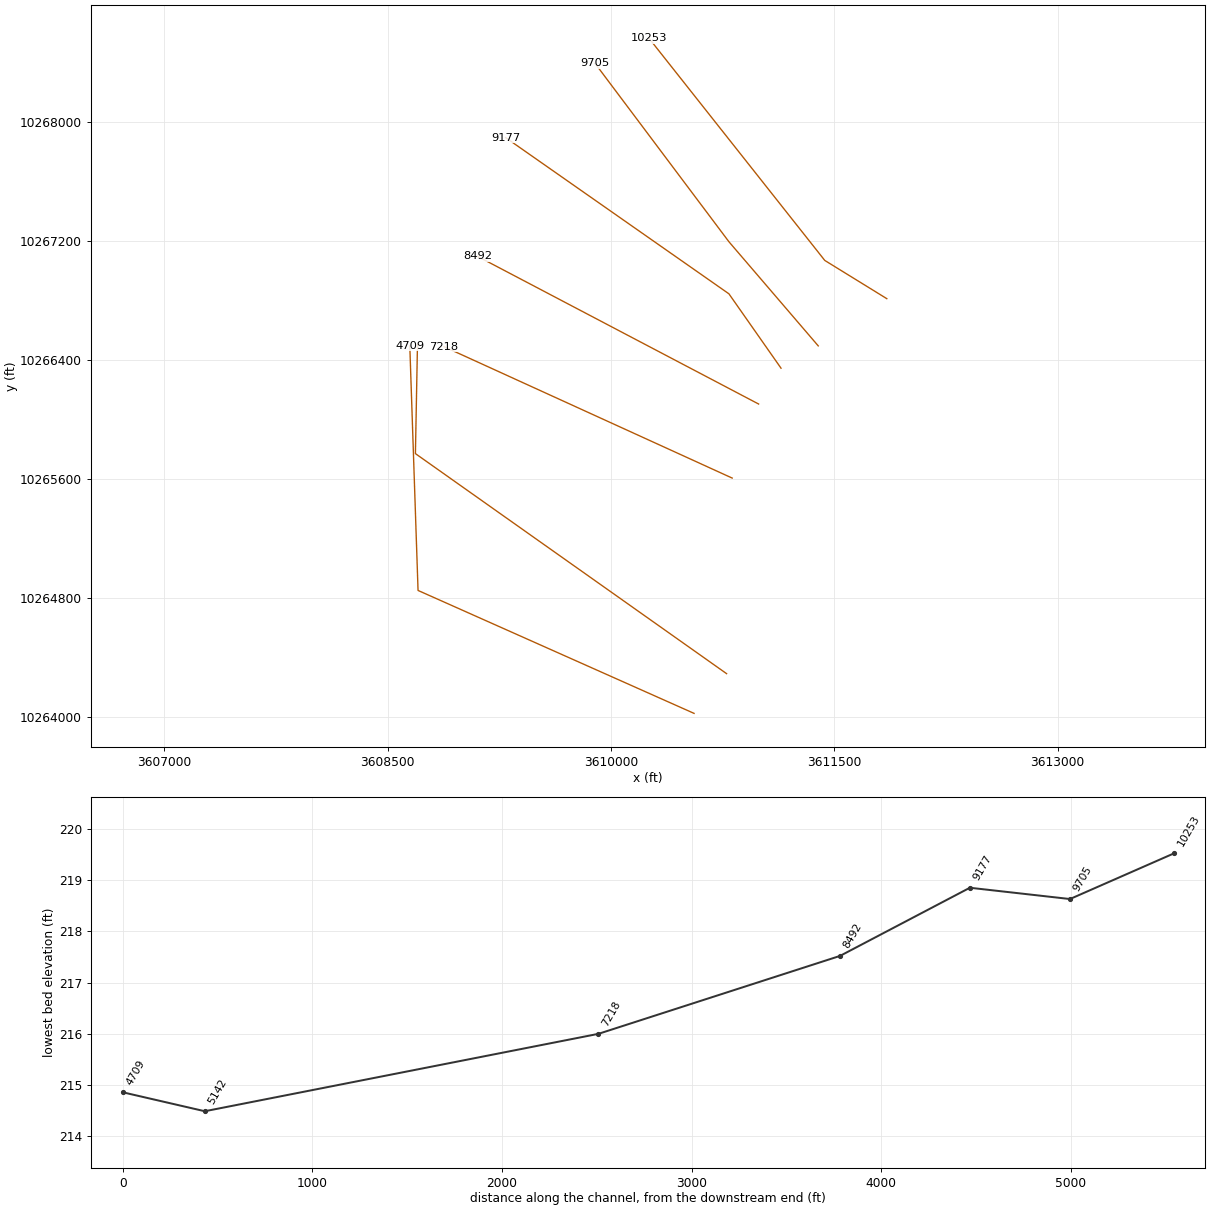
HEC-RAS study MORGAN CREEK.prj: MORGAN CREEK Base Level Engineering

--- MORGAN CREEK.g01 (geometry) --- (continued)

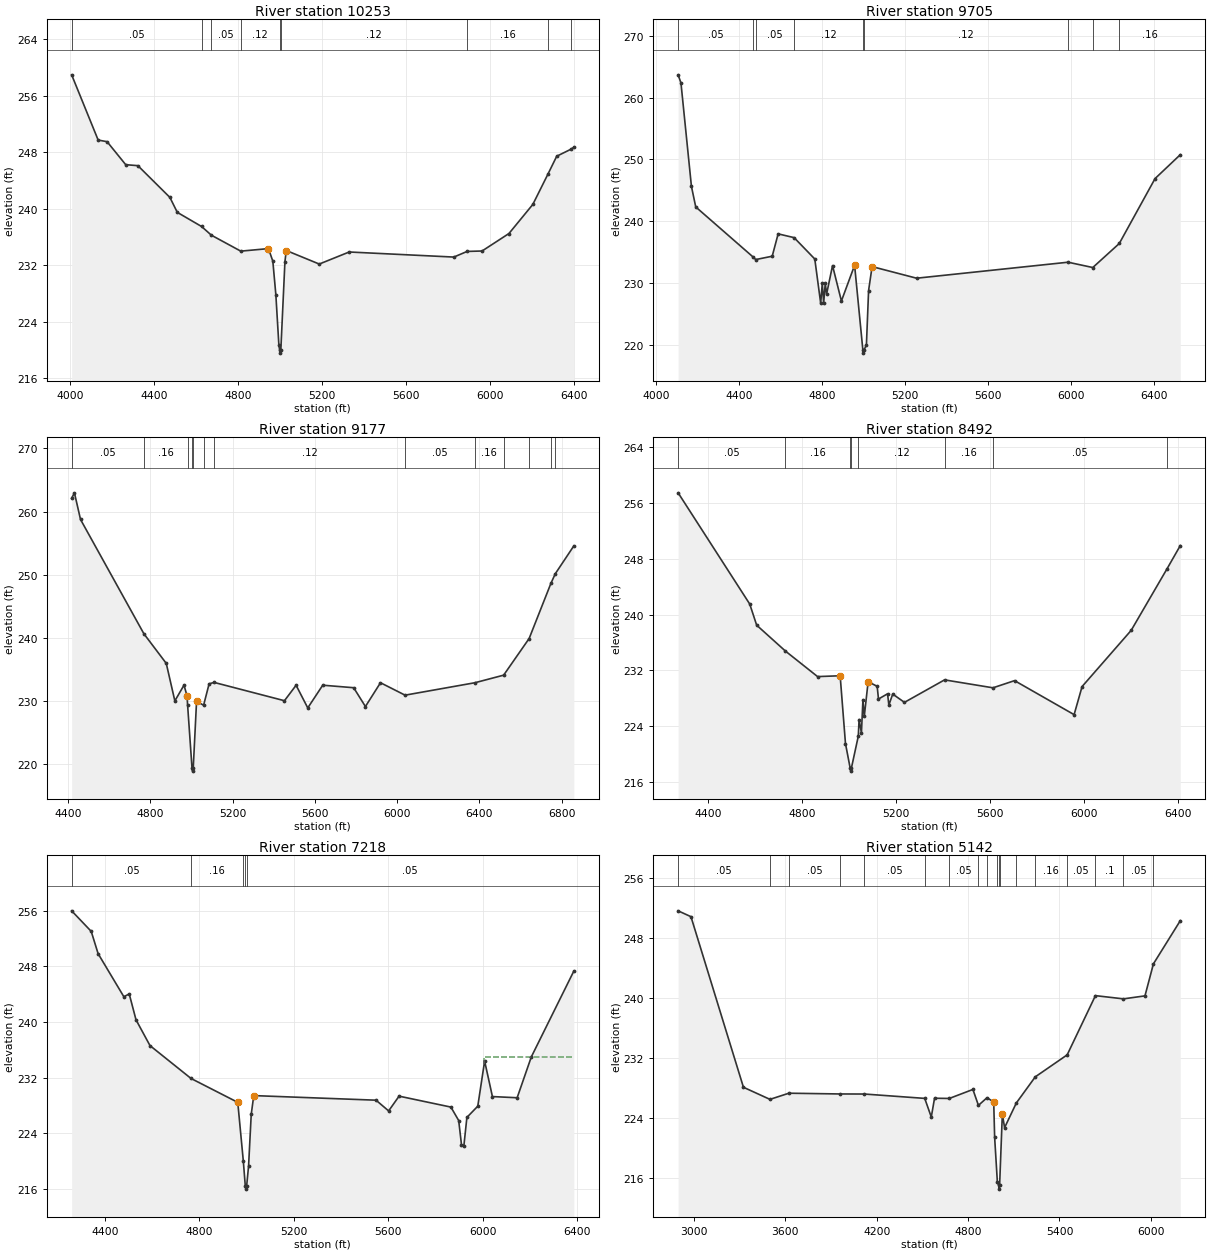
Type RM Length L Ch R = 1 ,10253   ,548,548,548
BEGIN DESCRIPTION:
MORGAN CREEK 11.0
END DESCRIPTION:
XS GIS Cut Line= 3
      3611852.64     10266809.13      3611435.99     10267066.07
      3610255.44     10268559.12
#Sta/Elev= 30
  4005.9  258.98  4132.2  249.73  4174.8   249.5  4263.5  246.24  4321.5   246.1
    4474   241.6  4509.3  239.48  4624.7  237.48  4671.8  236.24  4811.8  233.98
  4943.7  234.34  4964.5  232.56  4978.9  227.81  4993.4  220.62  4996.7  220.02
  4999.5  219.52  5002.7  220.02  5022.2   232.5  5028.6  234.07  5185.7  232.15
  5328.4  233.86  5826.9  233.14  5890.3  233.94  5961.5     234  6089.7  236.48
  6203.5  240.61  6275.2  244.89  6317.3  247.44    6385  248.43  6398.8  248.71
#Mann= 9 ,-1 , 0
  4005.9     .05       0  4624.7     .12       0  4671.8     .05       0
  4811.8     .12       0  4996.7     .07       0  5002.7     .12       0
  5890.3     .16       0  6275.2     .05       0    6385     .16       0
Bank Sta=4943.7,5028.6
XS Rating Curve= 0 ,0
Exp/Cntr=0.3,0.1

Type RM Length L Ch R = 1 ,9705    ,528,528,528
BEGIN DESCRIPTION:
MORGAN CREEK 10.0
END DESCRIPTION:
XS GIS Cut Line= 3
       3611392.1     10266491.65      3610792.11     10267191.64
      3609892.13     10268391.61
#Sta/Elev= 30
  4106.3  263.69    4120  262.38  4170.5  245.63  4191.3   242.3  4465.6  234.26
  4480.6  233.78  4560.1  234.32  4588.7  237.94  4665.7  237.33  4765.4  233.87
  4793.9  226.71  4801.6  229.96  4808.2  226.71  4815.9  229.92  4822.4   228.2
    4851   232.8  4893.8  227.07  4957.4  232.85  4997.3  219.13    5000  218.63
  5003.3  219.13  5014.5  220.02  5024.9  228.76  5041.8  232.64  5256.4  230.76
  5986.8  233.35  6106.1  232.49  6233.9  236.38  6406.4  246.89  6528.2  250.76
#Mann= 9 ,-1 , 0
  4106.3     .05       0  4465.6     .16       0  4480.6     .05       0
  4665.7     .12       0  4997.3     .07       0  5003.3     .12       0
  5986.8     .16       0  6106.1     .05       0  6233.9     .16       0
Bank Sta=4957.4,5041.8
XS Rating Curve= 0 ,0
Exp/Cntr=0.3,0.1

Type RM Length L Ch R = 1 ,9177    ,685,685,685
BEGIN DESCRIPTION:
MORGAN CREEK 9.0
END DESCRIPTION:
XS GIS Cut Line= 3
      3611142.08     10266341.67      3610792.11     10266841.64
      3609292.08     10267891.66
#Sta/Elev= 30
  4417.9   262.1  4431.4  262.96    4461  258.74  4769.1  240.62  4877.8  235.93
  4919.6  229.98  4964.1  232.48  4978.9  230.77  4981.4  229.41    5003  219.35
  5005.7  218.85    5009  219.35  5025.1   229.9  5059.4   229.3  5086.2  232.69
  5110.6  232.91  5452.4  230.01    5509  232.46  5565.7  228.87  5638.5  232.47
  5788.9  232.07    5846  229.09  5919.3  232.86  6038.8  230.89  6378.2  232.86
  6517.9  234.06  6641.9  239.87  6747.5  248.59  6769.1  250.14  6859.2  254.55
#Mann= 13 ,-1 , 0
  4417.9     .05       0  4769.1     .16       0  4981.4     .12       0
    5003     .07       0    5009     .12       0  5059.4     .16       0
  5110.6     .12       0  6038.8     .05       0  6378.2     .16       0
  6517.9     .05       0  6641.9     .16       0  6747.5     .05       0
  6769.1     .16       0
Bank Sta=4978.9,5025.1
XS Rating Curve= 0 ,0
Exp/Cntr=0.3,0.1

Type RM Length L Ch R = 1 ,8492    ,1274,1274,1274
BEGIN DESCRIPTION:
MORGAN CREEK 7.0
END DESCRIPTION:
XS GIS Cut Line= 2
      3610991.58     10266100.77      3609102.63     10267093.86
#Sta/Elev= 30
  4274.1  257.47  4578.5   241.5  4607.9  238.47  4730.3  234.75  4866.8  231.09
  4962.7  231.21  4985.3  221.48  5004.9  218.02  5007.6  217.52  5010.9  218.02
  5039.8  222.54  5043.1  224.93  5053.1  223.01  5059.5  227.78  5065.2  225.38
  5081.6  230.36    5120  229.69  5125.6  227.87  5164.1  228.62  5169.7  227.01
  5186.1  228.58  5235.9  227.39  5406.4  230.62  5612.1  229.48  5703.8  230.51
  5956.9  225.63  5990.8  229.66  6199.5  237.73  6352.4   246.6  6408.2   249.9
#Mann= 8 ,-1 , 0
  4274.1     .05       0  4730.3     .16       0  5004.9     .07       0
  5010.9     .16       0  5039.8     .12       0  5406.4     .16       0
  5612.1     .05       0  6352.4     .16       0
Bank Sta=4962.7,5081.6
XS Rating Curve= 0 ,0
Exp/Cntr=0.3,0.1

Type RM Length L Ch R = 1 ,7218    ,2076,2076,2076
BEGIN DESCRIPTION:
MORGAN CREEK 6.0
END DESCRIPTION:
XS GIS Cut Line= 2
      3610814.05     10265602.95      3608878.24     10266486.22
#Sta/Elev= 30
  4259.1  255.96    4342  253.01  4371.2  249.81  4480.2  243.63  4503.1  244.02
  4531.8  240.31    4591  236.61  4764.9  231.89  4962.9  228.46  4986.5  220.02
  4994.7   216.5  4997.4     216  5000.7   216.5  5008.7   219.3    5020  226.74
  5030.7  229.43  5548.8  228.77  5602.2  227.23  5646.4  229.35    5866  227.78
    5899  225.85  5910.8   222.4    5921  222.23  5933.8   226.3  5979.9  227.91
  6008.9  234.39  6041.9  229.29  6146.7  229.12  6206.8  234.99  6386.9  247.31
#Mann= 5 ,-1 , 0
  4259.1     .05       0  4764.9     .16       0  4986.5     .05       0
  4994.7    .035       0  5000.7     .05       0
#XS Ineff= 1 ,-1
 6006.82 6377.77  234.91
Permanent Ineff=
       F
Bank Sta=4962.9,5030.7
XS Rating Curve= 0 ,0
Exp/Cntr=0.3,0.1

Type RM Length L Ch R = 1 ,5142    ,433,433,433
BEGIN DESCRIPTION:
MORGAN CREEK 1.0
END DESCRIPTION:
XS GIS Cut Line= 3
      3610776.31     10264288.26      3608685.99     10265767.46
      3608699.88     10266503.57
#Sta/Elev= 30
  2896.3  251.57  2980.6  250.79  3325.2  228.06  3499.3  226.45  3623.7  227.27
  3957.5  227.17  4119.7  227.16  4515.3  226.58  4558.4   224.1  4579.8   226.6
  4676.6  226.57  4831.7  227.77  4867.9  225.65  4924.3  226.67  4968.3   226.1
  4974.4  221.38  4992.3  215.42    5001  214.99  5003.7  214.49    5007  214.99
  5024.9   224.5  5039.7  222.68  5116.8  225.97  5241.2  229.45  5450.6  232.38
  5636.1  240.27  5820.2  239.84  5961.3  240.24  6016.9  244.51  6193.3  250.26
#Mann= 18 ,-1 , 0
  2896.3     .05       0  3499.3     .16       0  3623.7     .05       0
  3957.5     .12       0  4119.7     .05       0  4515.3     .16       0
  4676.6     .05       0  4867.9     .16       0  4924.3     .05       0
  4992.3     .16       0    5001     .07       0    5007     .16       0
  5116.8     .05       0  5241.2     .16       0  5450.6     .05       0
  5636.1      .1       0  5820.2     .05       0  6016.9     .16       0
Bank Sta=4968.3,5024.9
XS Rating Curve= 0 ,0
Exp/Cntr=0.3,0.1

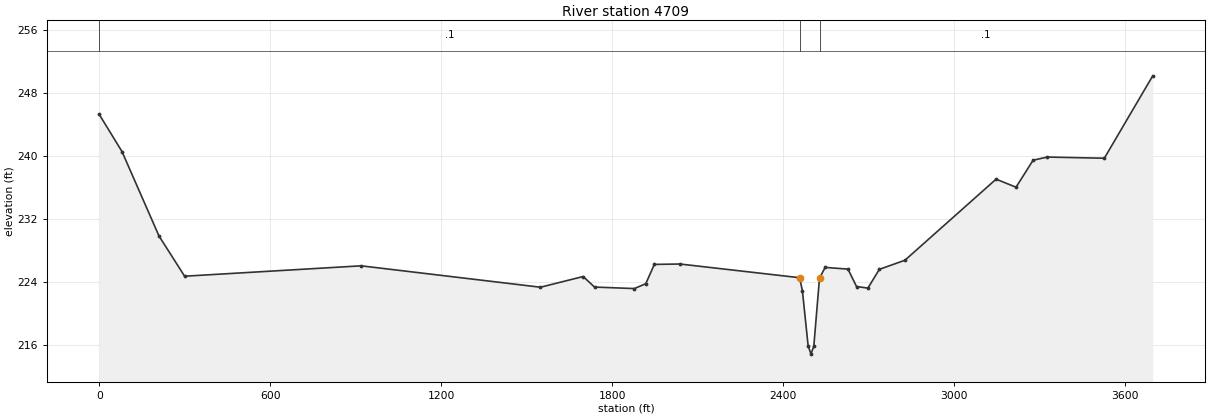
Type RM Length L Ch R = 1 ,4709    ,0,0,0
XS GIS Cut Line= 3
     3610557.881    10264021.214     3608703.715    10264847.603
     3608648.159    10266493.436
#Sta/Elev= 30
       0  245.32   79.93   240.6  209.82  229.87  299.74  224.76  919.19  226.08
 1548.64  223.36 1698.51  224.72 1738.47  223.38 1878.35  223.19 1918.32  223.81
 1948.29  226.26 2038.21  226.31 2458.05  224.57 2468.05  222.91 2488.04  215.95
 2498.04  214.86 2508.03  215.86 2528.03  224.53 2548.02  225.88 2627.99  225.66
 2657.98  223.45 2697.97  223.25 2737.95  225.63 2827.92  226.79 3147.81  237.09
 3217.78  236.07 3277.76   239.5 3327.74   239.9 3527.67  239.75 3697.61  250.22
#Mann= 3 , 0 , 0
       0      .1       0 2458.05     .05       0 2528.03      .1       0
Bank Sta=2458.05,2528.03
XS Rating Curve= 0 ,0
Exp/Cntr=0.3,0.1

Chan Stop Cuts=-1
Use User Specified Reach Order=0
Composite Channel Slope=5