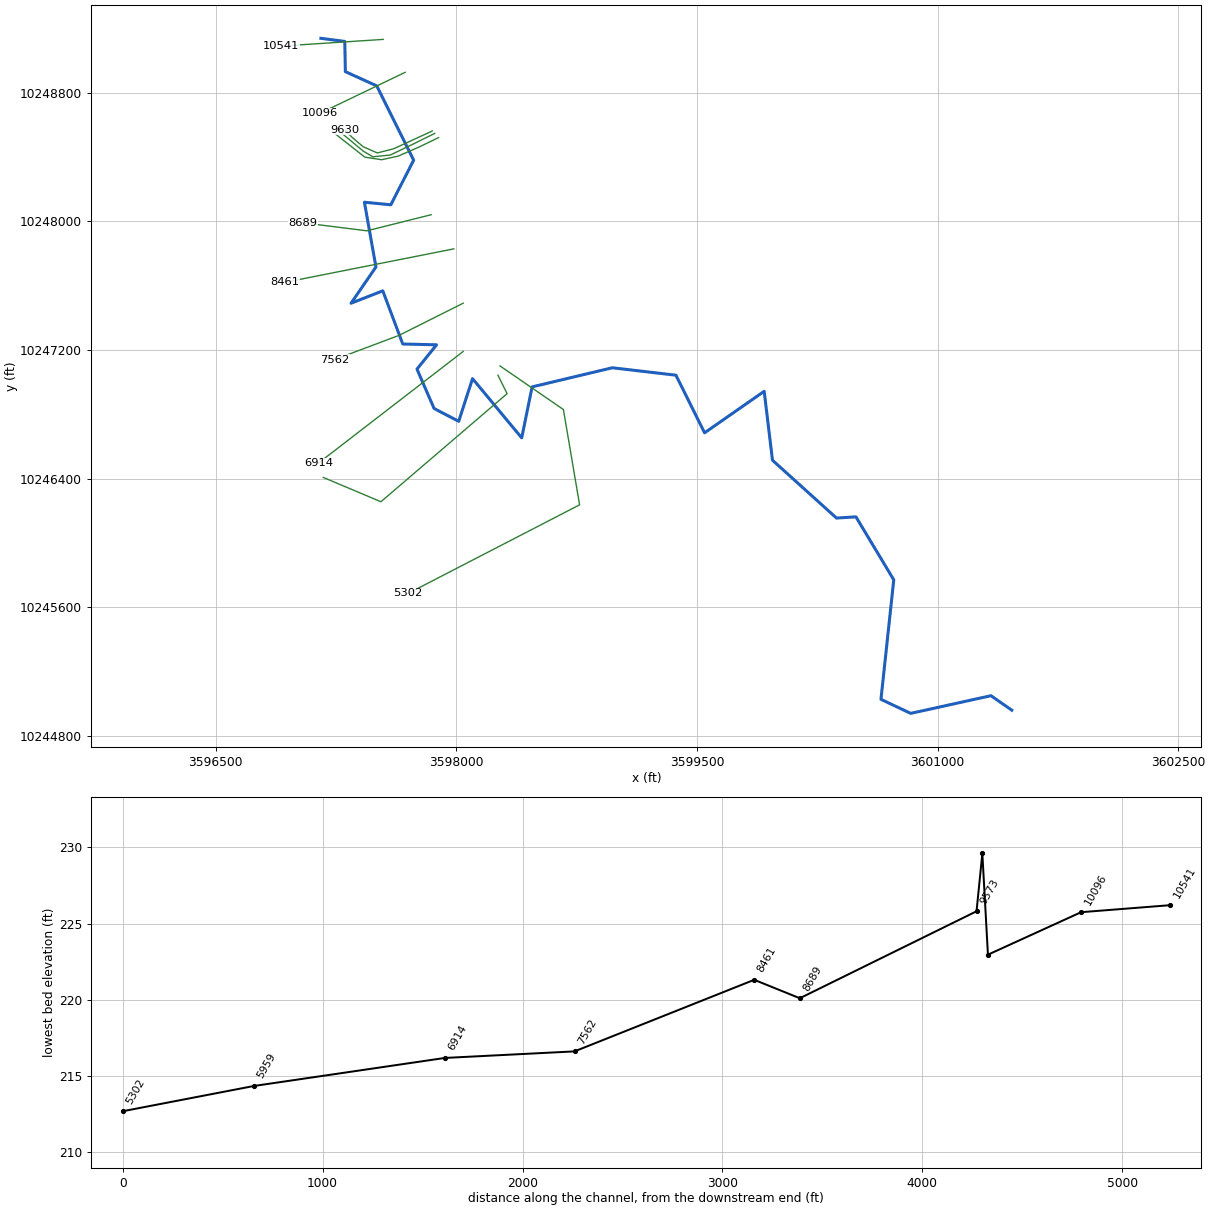
--- NAVASOTARIVERTRIB.prj (project) ---

Proj Title=NAVASOTA RIVER TRIBUTARY 18 4 2
Current Plan=p01
Default Exp/Contr=0.3,0.1
English Units
Geom File=g01
Flow File=f01
Plan File=p01
Y Axis Title=Elevation
X Axis Title(PF)=Main Channel Distance
X Axis Title(XS)=Station
BEGIN DESCRIPTION:
UNT0478 IN WICK
END DESCRIPTION:
DSS Export Rating Curves= 0
DSS Export Rating Curve Sorted= 0
DSS Export Volume Flow Curves= 0
DXF Filename=UNT0478 IN WICK.
DXF OffsetX= 0
DXF OffsetY= 0
DXF ScaleX= 1
DXF ScaleY= 10

--- NAVASOTARIVERTRIB.p01 (plan) ---

Plan Title=Multiple Run
Short Identifier=Multiple
Geom File=g01
Flow File=f01
Subcritical Flow
K Sum by GR= 0
Std Step Tol= 0.01
Critical Tol= 0.01
Num of Std Step Trials= 20
Max Error Tol= 0.3
Flow Tol Ratio= 0.001
Split Flow NTrial= 30
Split Flow Tol= 0.02
Split Flow Ratio= 0.02
Log Output Level= 0
Friction Slope Method= 1
Unsteady Friction Slope Method= 2
Unsteady Bridges Friction Slope Method= 1
Parabolic Critical Depth
Global Vel Dist=  1 , 1 , 1
Global Log Level= 0
CheckData=True
Encroach Param= -1, 0, 0, 0
BEGIN DESCRIPTION:
Multiple Run
END DESCRIPTION:

--- NAVASOTARIVERTRIB.f01 (steady flow) ---

Flow Title=Multiple
Program Version=4.10
Number of Profiles= 7
Profile Names=10-year,25-year,50-year,1pct_min,100-year,1pct_plu,500-year
River Rch & RM=UNT0478 IN WICK,Reach-1         ,10541
     647     866    1042     918    1241    1679    1765
River Rch & RM=NAVRIVTRIB1842,Reach-1         ,10541
     647     866    1042     918    1241    1679    1765
Boundary for River Rch & Prof#=NAVRIVTRIB1842,Reach-1         , 1
Up Type= 0
Dn Type= 3
Dn Slope=0.005
Boundary for River Rch & Prof#=NAVRIVTRIB1842,Reach-1         , 2
Up Type= 0
Dn Type= 3
Dn Slope=0.005
Boundary for River Rch & Prof#=NAVRIVTRIB1842,Reach-1         , 3
Up Type= 0
Dn Type= 3
Dn Slope=0.005
Boundary for River Rch & Prof#=NAVRIVTRIB1842,Reach-1         , 4
Up Type= 0
Dn Type= 3
Dn Slope=0.005
Boundary for River Rch & Prof#=NAVRIVTRIB1842,Reach-1         , 5
Up Type= 0
Dn Type= 3
Dn Slope=0.005
Boundary for River Rch & Prof#=NAVRIVTRIB1842,Reach-1         , 6
Up Type= 0
Dn Type= 3
Dn Slope=0.005
Boundary for River Rch & Prof#=NAVRIVTRIB1842,Reach-1         , 7
Up Type= 0
Dn Type= 3
Dn Slope=0.005
DSS Import GetInterval= 0
DSS Import GetPeak= 0
DSS Import FillOption= 0

--- NAVASOTARIVERTRIB.g01 (geometry) ---

Geom Title=Existing Conditions
Program Version=4.10

River Reach=NAVRIVTRIB1842  ,Reach-1
Reach XY= 30
      3597155.33     10249138.19      3597304.08     10249119.02
      3597307.56     10248931.09       3597503.3     10248842.54
      3597733.34     10248380.74      3597590.98      10248103.4
      3597426.42      10248119.3      3597498.26     10247716.63
      3597343.18     10247491.54      3597540.97      10247568.6
      3597665.37     10247238.03       3597876.1       10247233.
      3597754.05      10247081.9       3597860.7     10246837.12
      3598014.15      10246757.4      3598100.36      10247022.8
      3598406.91     10246654.31      3598471.83     10246971.42
      3598971.82     10247090.26      3599368.38     10247044.08
      3599546.95     10246685.84      3599918.48     10246943.96
       3599970.2     10246515.48       3600369.3       10246156.
      3600490.43     10246163.55      3600726.26     10245771.73
      3600646.48     10245029.03      3600831.94     10244941.81
      3601332.12     10245051.68      3601462.11     10244961.64

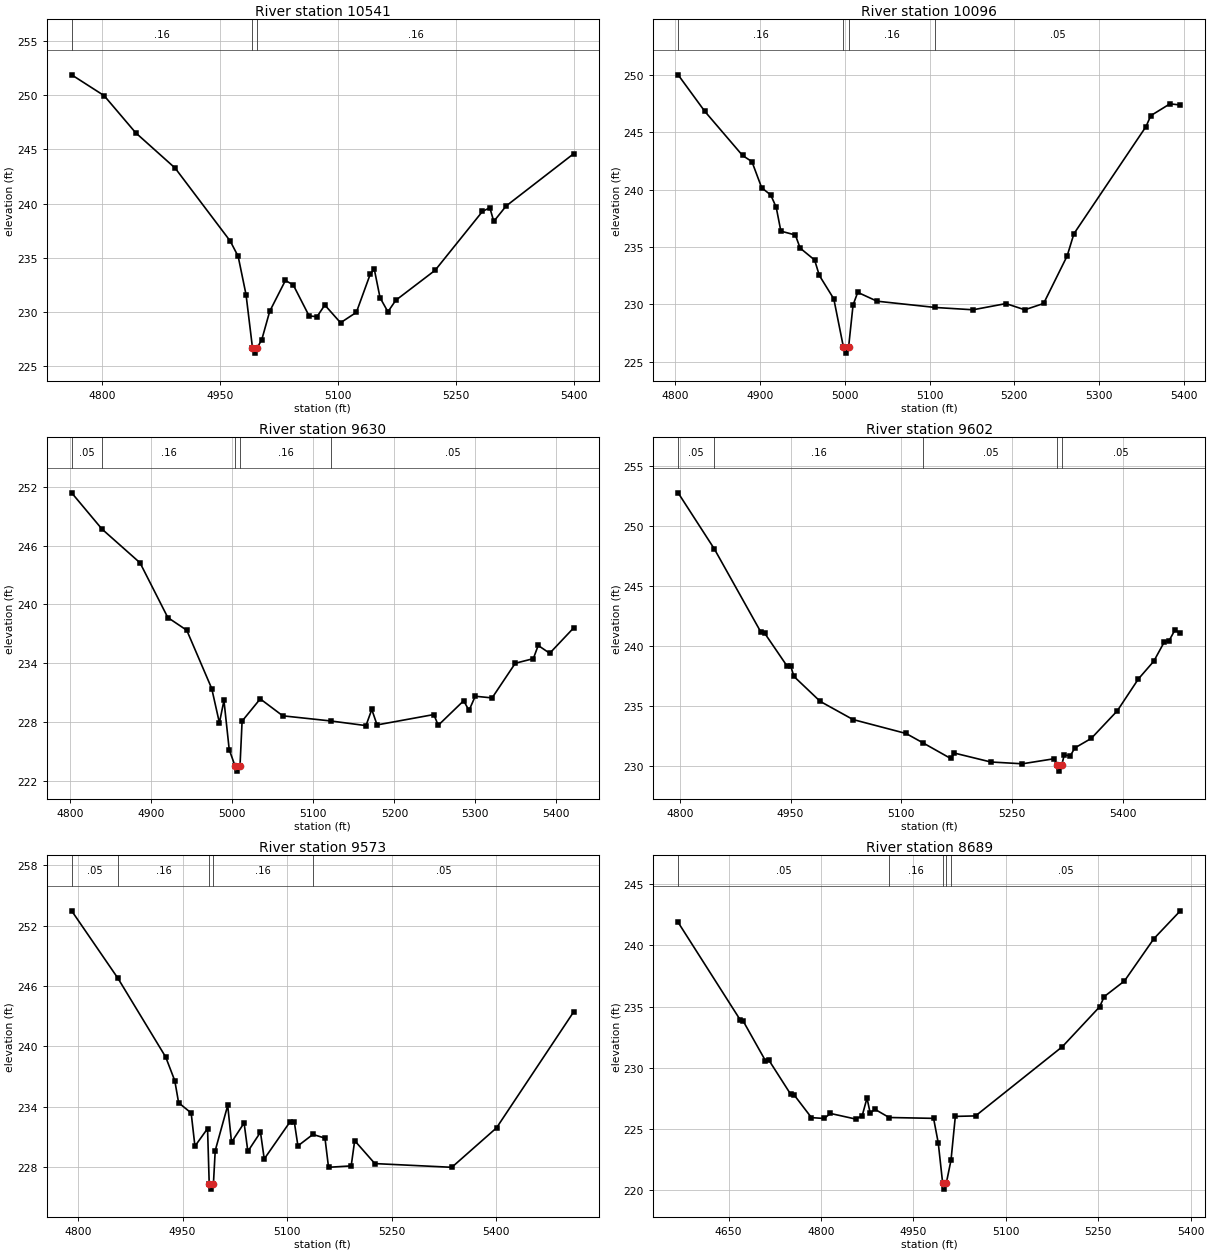
Type RM Length L Ch R = 1 ,10541   ,445,445,445
BEGIN DESCRIPTION:
UNT0478 IN WICK 10.0
END DESCRIPTION:
XS GIS Cut Line= 2
      3597543.33     10249131.57      3596906.18     10249089.96
#Sta/Elev= 30
  4761.6  251.86  4802.9  249.94    4843  246.52  4893.1  243.27  4963.2  236.54
  4973.3  235.13  4983.3  231.61  4991.5  226.71  4994.3  226.21  4997.5  226.71
  5003.3  227.44  5013.4  230.06  5033.4  232.91  5043.4  232.49  5063.5  229.64
  5073.5  229.57  5083.5  230.64  5103.5  229.01  5123.6  229.97  5141.4  233.52
  5146.4  233.94  5153.7  231.32  5163.7  230.02  5173.7  231.08  5223.8  233.85
  5283.9  239.27  5293.3  239.61  5298.3  238.35    5314  239.77  5400.1   244.6
#Mann= 3 ,-1 , 0
  4761.6     .16       0  4991.5     .07       0  4997.5     .16       0
Bank Sta=4991.5,4997.5
XS Rating Curve= 0 ,0
Exp/Cntr=0.3,0.1

Type RM Length L Ch R = 1 ,10096   ,466,466,466
BEGIN DESCRIPTION:
UNT0478 IN WICK 9.0
END DESCRIPTION:
XS GIS Cut Line= 2
      3597680.53     10248927.01      3597146.85     10248671.02
#Sta/Elev= 30
  4803.7  250.02  4835.2  246.83  4879.6  242.99  4890.7  242.45  4902.2  240.17
  4912.9  239.54  4919.3  238.47  4924.8  236.39  4941.9  236.05  4947.5  234.91
  4964.6  233.87  4970.1  232.53  4987.2  230.48  4998.6  226.25  5001.3  225.75
  5004.6  226.25  5009.9  229.95  5015.4  231.05  5038.1  230.28    5107  229.73
  5151.3  229.53  5190.1  230.07  5212.3  229.53  5234.5  230.08  5262.2  234.22
  5270.2  236.16  5355.2  245.51  5360.8  246.46  5383.4  247.49  5395.6  247.39
#Mann= 4 ,-1 , 0
  4803.7     .16       0  4998.6     .07       0  5004.6     .16       0
    5107     .05       0
Bank Sta=4998.6,5004.6
XS Rating Curve= 0 ,0
Exp/Cntr=0.3,0.1

Type RM Length L Ch R = 1 ,9630    ,28,28,28
BEGIN DESCRIPTION:
Mapping XS 39202f1b
END DESCRIPTION:
XS GIS Cut Line= 6
      3597849.79     10248562.42      3597608.89     10248451.73
      3597506.89     10248425.69      3597417.92     10248464.76
      3597344.13     10248527.69      3597307.27     10248568.89
#Sta/Elev= 30
  4801.6  251.39    4839  247.69    4886  244.24  4920.3  238.65  4943.7  237.35
  4974.5   231.4    4984  227.89  4989.6  230.18  4996.1  225.16  5003.4  223.46
  5006.2  222.96  5009.4  223.46    5012  228.07  5034.4  230.34  5062.2  228.61
  5121.9  228.08  5164.9  227.61  5172.1  229.26  5178.6  227.68  5248.7  228.74
  5254.1  227.64  5285.5  230.15  5292.1  229.16  5299.8  230.61  5320.6  230.44
  5349.2  233.98  5371.5  234.45  5377.5   235.8  5391.7     235  5421.5  237.61
#Mann= 5 ,-1 , 0
  4801.6     .05       0    4839     .16       0  5003.4     .07       0
  5009.4     .16       0  5121.9     .05       0
Bank Sta=5003.4,5009.4
XS Rating Curve= 0 ,0
Exp/Cntr=0.3,0.1

Type RM Length L Ch R = 1 ,9602    ,29,29,29
BEGIN DESCRIPTION:
Mapping XS 9f3fe412
END DESCRIPTION:
XS GIS Cut Line= 6
      3597864.99     10248547.23      3597728.25     10248479.95
      3597587.19     10248412.67      3597478.68     10248401.82
      3597420.09     10248436.54      3597270.32     10248560.26
#Sta/Elev= 30
  4797.7  252.75  4846.8  248.08  4909.5   241.2  4915.1  241.06  4945.2  238.35
  4950.1  238.35  4954.6  237.48  4990.1  235.41  5034.5   233.9  5106.4  232.74
  5129.9  231.94  5166.9  230.66  5171.9  231.11  5221.1  230.37  5263.9  230.22
  5306.9  230.64  5311.2  230.11    5314  229.61  5317.2  230.11  5320.7  230.97
  5328.6  230.86    5335  231.54  5357.2  232.33  5392.4  234.62  5421.1  237.28
  5441.9  238.75  5456.2  240.36  5462.7  240.47  5470.6  241.35  5477.8  241.07
#Mann= 5 ,-1 , 0
  4797.7     .05       0  4846.8     .16       0  5129.9     .05       0
  5311.2     .07       0  5317.2     .05       0
Bank Sta=5311.2,5317.2
XS Rating Curve= 0 ,0
Exp/Cntr=0.3,0.1

Type RM Length L Ch R = 1 ,9573    ,884,884,884
BEGIN DESCRIPTION:
UNT0478 IN WICK 8.0
END DESCRIPTION:
XS GIS Cut Line= 6
       3597888.8     10248521.16      3597767.31     10248462.59
      3597636.48     10248405.95      3597534.14     10248383.61
      3597428.77     10248399.65      3597246.79     10248542.63
#Sta/Elev= 30
  4790.9  253.48  4857.3  246.77  4925.8  238.94  4938.8  236.59  4944.3   234.4
  4962.3  233.38  4967.7  230.08  4985.8  231.83  4988.2  226.31    4991  225.81
  4994.2  226.31  4996.8  229.64  5014.7  234.13  5020.2  230.47  5038.2  232.39
  5043.6  229.56  5061.7  231.47  5067.1  228.81  5103.5  232.44  5110.3  232.45
  5115.4  230.11  5136.9  231.25  5154.2  230.88  5159.3  227.98  5191.8  228.12
  5196.8  230.63  5225.7  228.35  5336.1  227.98  5400.2   231.9  5511.1  243.46
#Mann= 5 ,-1 , 0
  4790.9     .05       0  4857.3     .16       0  4988.2     .07       0
  4994.2     .16       0  5136.9     .05       0
Bank Sta=4988.2,4994.2
XS Rating Curve= 0 ,0
Exp/Cntr=0.3,0.1

Type RM Length L Ch R = 1 ,8689    ,228,228,228
BEGIN DESCRIPTION:
UNT0478 IN WICK 7.0
END DESCRIPTION:
XS GIS Cut Line= 3
      3597842.12     10248041.65      3597442.11     10247941.64
      3597042.15     10247991.64
#Sta/Elev= 30
    4568  241.89  4668.5  233.95  4673.7  233.82  4709.7   230.6  4714.9  230.67
    4751  227.83  4756.1  227.81  4784.5  225.94  4805.1  225.87  4815.4  226.28
  4856.6  225.82  4866.9   226.1  4874.7  227.54  4879.8  226.32  4887.6  226.62
  4910.6  225.95  4982.8  225.88  4990.4  223.87  4997.5   220.6  5000.2   220.1
  5003.5   220.6  5011.1  222.47  5018.1  226.04  5050.9  226.08    5192  231.74
  5252.4  234.99    5260  235.83  5292.7   237.1  5340.6  240.56  5383.4  242.83
#Mann= 5 ,-1 , 0
    4568     .05       0  4910.6     .16       0  4997.5     .07       0
  5003.5     .16       0  5011.1     .05       0
Bank Sta=4997.5,5003.5
XS Rating Curve= 0 ,0
Exp/Cntr=0.3,0.1

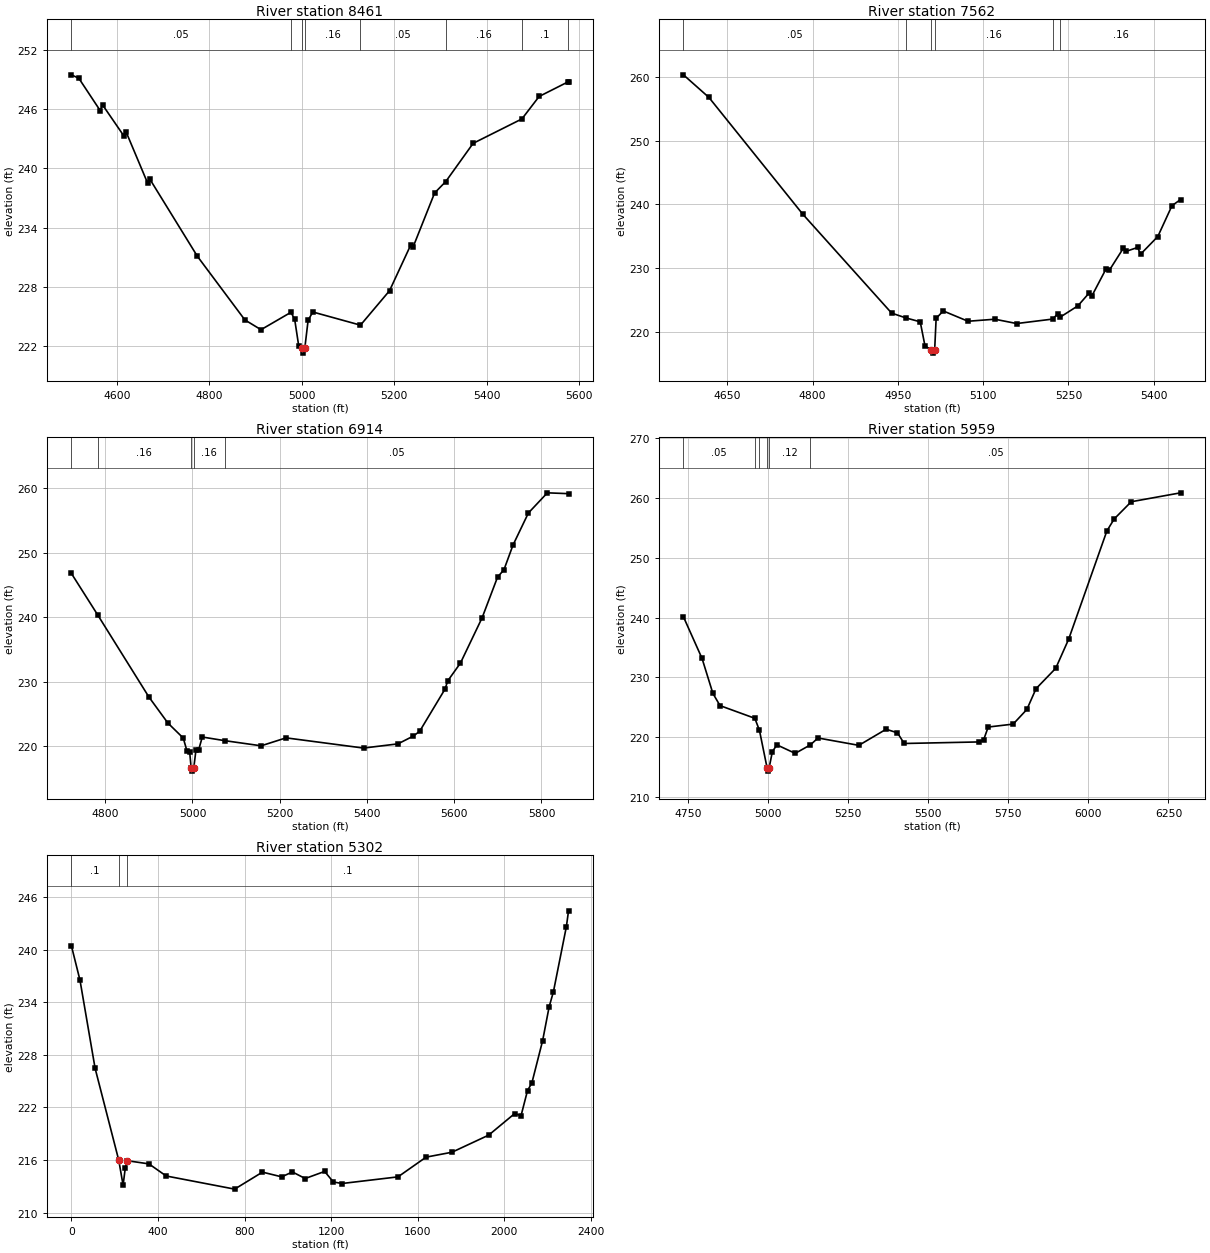
Type RM Length L Ch R = 1 ,8461    ,899,899,899
BEGIN DESCRIPTION:
UNT0478 IN WICK 6.0
END DESCRIPTION:
XS GIS Cut Line= 2
      3597984.31     10247829.49      3596929.69     10247621.17
#Sta/Elev= 30
    4502  249.46  4518.1  249.11  4564.3  245.84  4569.4  246.42  4615.6  243.27
  4620.7  243.64  4666.9   238.5    4672  238.88  4774.5   231.1  4877.1  224.67
    4912  223.68  4976.8  225.44  4984.8  224.73  4993.5  222.06  5000.7  221.81
  5003.5  221.31  5006.7  221.81  5013.9  224.64  5024.1  225.47  5127.1  224.14
  5189.9  227.62  5236.1  232.28  5241.2  232.08  5287.4  237.51  5311.6  238.67
  5370.7  242.53  5476.2     245  5513.4  247.27  5576.1  248.75    5577  248.75
#Mann= 8 ,-1 , 0
    4502     .05       0  4976.8     .16       0  5000.7     .07       0
  5006.7     .16       0  5127.1     .05       0  5311.6     .16       0
  5476.2      .1       0  5576.1     .05       0
Bank Sta=5000.7,5006.7
XS Rating Curve= 0 ,0
Exp/Cntr=0.3,0.1

Type RM Length L Ch R = 1 ,7562    ,648,648,648
BEGIN DESCRIPTION:
UNT0478 IN WICK 5.0
END DESCRIPTION:
XS GIS Cut Line= 3
      3598042.14     10247491.66      3597642.11     10247291.64
      3597242.15     10247141.66
#Sta/Elev= 30
  4572.8  260.35  4617.6   256.8  4782.5  238.47    4939   222.9  4964.2  222.14
  4989.3  221.53  4997.7  217.74  5008.7  217.11  5011.4  216.61  5014.7  217.11
  5017.3  222.08  5029.8  223.24  5073.4  221.62  5120.6  221.94  5158.9  221.26
  5222.1  221.96    5231  222.77  5235.7  222.28  5266.6  224.04  5286.2  226.04
  5291.5  225.65  5316.4  229.89  5321.8  229.61  5346.7  233.12    5352  232.62
  5371.6  233.22  5376.9  232.16  5407.2  234.94  5432.1  239.78  5447.2  240.75
#Mann= 6 ,-1 , 0
  4572.8     .05       0  4964.2     .16       0  5008.7     .07       0
  5014.7     .16       0  5222.1     .05       0  5235.7     .16       0
Bank Sta=5008.7,5014.7
XS Rating Curve= 0 ,0
Exp/Cntr=0.3,0.1

Type RM Length L Ch R = 1 ,6914    ,955,955,955
BEGIN DESCRIPTION:
UNT0478 IN WICK 4.0
END DESCRIPTION:
XS GIS Cut Line= 2
      3598042.12     10247191.65      3597138.83     10246497.01
#Sta/Elev= 30
  4722.5  246.78  4782.5  240.39  4900.1  227.66  4943.6  223.63  4978.9   221.3
  4987.2  219.35  4993.5   219.2    4997  216.68  4999.8  216.18    5003  216.68
    5008  219.44  5014.3   219.5  5022.5  221.46  5073.6   220.9  5157.5   220.1
  5214.5  221.33  5392.1  219.75    5471   220.4  5506.3  221.61  5520.8  222.35
  5578.9  228.88  5585.2  230.16  5614.2   232.9    5664  239.93  5699.4  246.23
  5713.9  247.34  5734.7  251.17    5770  256.14  5813.5  259.26    5862  259.13
#Mann= 5 ,-1 , 0
  4722.5     .05       0  4782.5     .16       0    4997     .07       0
    5003     .16       0  5073.6     .05       0
Bank Sta=4997,5003
XS Rating Curve= 0 ,0
Exp/Cntr=0.3,0.1

Type RM Length L Ch R = 1 ,5959    ,657,657,657
BEGIN DESCRIPTION:
UNT0478 IN WICK 1.0
END DESCRIPTION:
XS GIS Cut Line= 4
      3598258.65     10247043.89      3598315.93     10246929.32
      3597529.48     10246257.44       3597170.1     10246408.48
#Sta/Elev= 30
  4735.5  240.14  4793.7  233.17  4827.5  227.33  4849.8  225.29  4958.5  223.17
  4972.9  221.15  4996.9  214.84  4999.7  214.34  5002.9  214.84  5013.3  217.61
  5027.4  218.73  5084.5  217.31  5131.4  218.71  5155.8  219.88  5283.2  218.65
  5368.4  221.34  5403.9  220.74  5424.8  218.96  5658.6  219.22  5672.9  219.58
  5687.2  221.71  5765.1   222.2  5807.9  224.65  5836.5  228.12    5898  231.53
  5938.5  236.41  6057.8   254.5  6080.8  256.51  6133.8  259.37  6287.8  260.86
#Mann= 6 ,-1 , 0
  4735.5     .05       0  4958.5     .16       0  4972.9     .12       0
  4996.9     .07       0  5002.9     .12       0  5131.4     .05       0
Bank Sta=4996.9,5002.9
XS Rating Curve= 0 ,0
Exp/Cntr=0.3,0.1

Type RM Length L Ch R = 1 ,5302    ,0,0,0
XS GIS Cut Line= 4
     3598271.805    10247101.655       3598666.8    10246830.671
     3598767.845    10246238.179     3597697.685    10245687.023
#Sta/Elev= 30
       0  240.44   39.81   236.5  109.48  226.47  218.95  215.96  238.86  213.13
  248.81  215.06  258.76  215.92  358.28  215.56   437.9  214.18  754.34  212.68
  882.78  214.62  971.69  214.08 1021.09  214.64 1080.37  213.89 1170.12   214.7
 1210.01   213.5  1249.9  213.32 1509.18  214.08 1638.82  216.33 1758.48  216.89
 1928.01  218.84 2047.68  221.29  2077.6  221.06 2107.51  223.93 2127.46  224.78
 2177.32  229.62 2207.24  233.46 2227.18   235.2 2287.01  242.62 2296.99  244.43
#Mann= 3 , 0 , 0
       0      .1       0  218.95     .05       0  258.76      .1       0
Bank Sta=218.95,258.76
XS Rating Curve= 0 ,0
Exp/Cntr=0.3,0.1

Chan Stop Cuts=-1
Use User Specified Reach Order=0
Composite Channel Slope=5