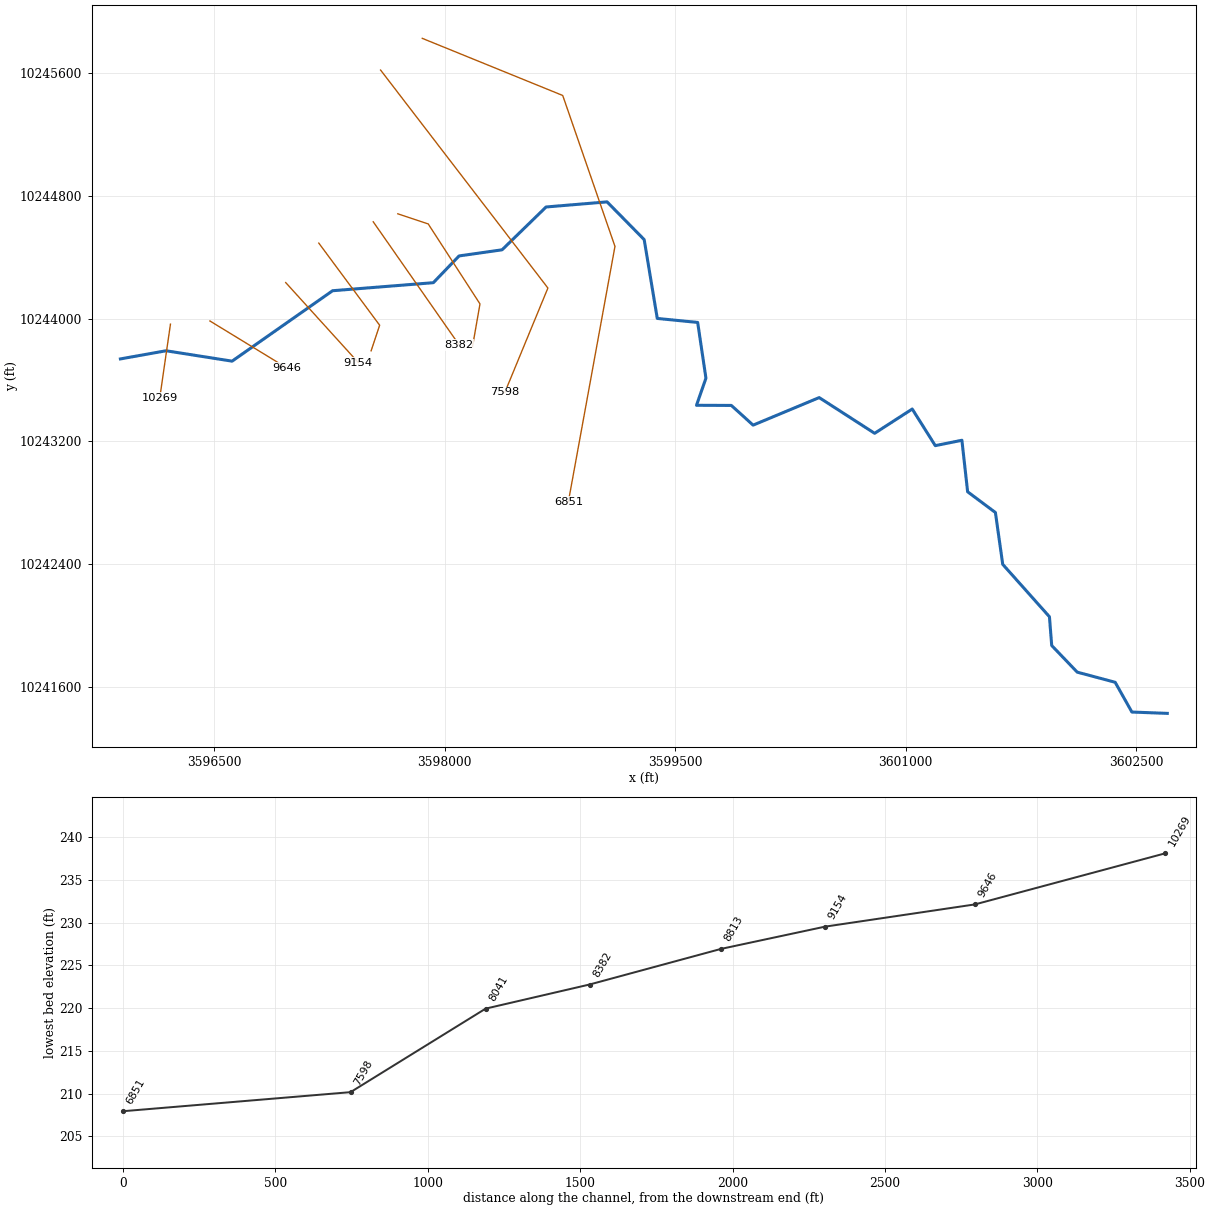
--- NAVASOTARIVERTRIB.prj (project) ---

Proj Title=NAVASOTA RIVER TRIB 18 5
Current Plan=p01
Default Exp/Contr=0.3,0.1
English Units
Geom File=g01
Flow File=f01
Plan File=p01
Y Axis Title=Elevation
X Axis Title(PF)=Main Channel Distance
X Axis Title(XS)=Station
BEGIN DESCRIPTION:
UNT0479 IN WICK
END DESCRIPTION:
DSS Export Rating Curves= 0
DSS Export Rating Curve Sorted= 0
DSS Export Volume Flow Curves= 0
DXF Filename=UNT0479 IN WICK.
DXF OffsetX= 0
DXF OffsetY= 0
DXF ScaleX= 1
DXF ScaleY= 10

--- NAVASOTARIVERTRIB.p01 (plan) ---

Plan Title=Multiple Run
Short Identifier=Multiple
Geom File=g01
Flow File=f01
Subcritical Flow
K Sum by GR= 0
Std Step Tol= 0.01
Critical Tol= 0.01
Num of Std Step Trials= 20
Max Error Tol= 0.3
Flow Tol Ratio= 0.001
Split Flow NTrial= 30
Split Flow Tol= 0.02
Split Flow Ratio= 0.02
Log Output Level= 0
Friction Slope Method= 1
Unsteady Friction Slope Method= 2
Unsteady Bridges Friction Slope Method= 1
Parabolic Critical Depth
Global Vel Dist=  1 , 1 , 1
Global Log Level= 0
CheckData=True
Encroach Param= -1, 0, 0, 0
BEGIN DESCRIPTION:
Multiple Run
END DESCRIPTION:

--- NAVASOTARIVERTRIB.f01 (steady flow) ---

Flow Title=Multiple
Program Version=4.10
Number of Profiles= 7
Profile Names=10-year,25-year,50-year,1pct_min,100-year,1pct_plu,500-year
River Rch & RM=UNT0479 IN WICK,Reach-1         ,10269
     575     771     930     823    1113    1505    1596
River Rch & RM=NAVRIVTRIB185,Reach-1         ,10269
     575     771     930     823    1113    1505    1596
Boundary for River Rch & Prof#=NAVRIVTRIB185,Reach-1         , 1
Up Type= 0
Dn Type= 3
Dn Slope=0.005
Boundary for River Rch & Prof#=NAVRIVTRIB185,Reach-1         , 2
Up Type= 0
Dn Type= 3
Dn Slope=0.005
Boundary for River Rch & Prof#=NAVRIVTRIB185,Reach-1         , 3
Up Type= 0
Dn Type= 3
Dn Slope=0.005
Boundary for River Rch & Prof#=NAVRIVTRIB185,Reach-1         , 4
Up Type= 0
Dn Type= 3
Dn Slope=0.005
Boundary for River Rch & Prof#=NAVRIVTRIB185,Reach-1         , 5
Up Type= 0
Dn Type= 3
Dn Slope=0.005
Boundary for River Rch & Prof#=NAVRIVTRIB185,Reach-1         , 6
Up Type= 0
Dn Type= 3
Dn Slope=0.005
Boundary for River Rch & Prof#=NAVRIVTRIB185,Reach-1         , 7
Up Type= 0
Dn Type= 3
Dn Slope=0.005
DSS Import GetInterval= 0
DSS Import GetPeak= 0
DSS Import FillOption= 0

--- NAVASOTARIVERTRIB.g01 (geometry) ---

Geom Title=Existing Conditions
Program Version=4.10

River Reach=NAVRIVTRIB185   ,Reach-1
Reach XY= 30
      3595889.95     10243737.19      3596187.03     10243790.33
      3596616.59     10243722.66      3597270.62     10244181.31
      3597925.88     10244233.57      3598093.64     10244407.92
      3598373.24     10244447.68       3598659.6     10244726.57
      3599056.36     10244759.84      3599297.86     10244514.11
      3599382.99     10244000.85      3599645.84     10243974.73
      3599699.66     10243611.72      3599638.24     10243435.28
      3599865.06     10243434.32      3600006.59     10243305.99
      3600436.45     10243485.45       3600797.2     10243252.84
      3601041.88     10243410.86      3601191.82     10243172.51
        3601365.     10243207.52      3601402.31     10242872.07
      3601583.05     10242736.94       3601630.6     10242399.62
       3601934.5      10242058.4      3601949.33     10241870.89
       3602115.2     10241697.61      3602362.09      10241631.6
        3602471.     10241437.75      3602701.48     10241429.07

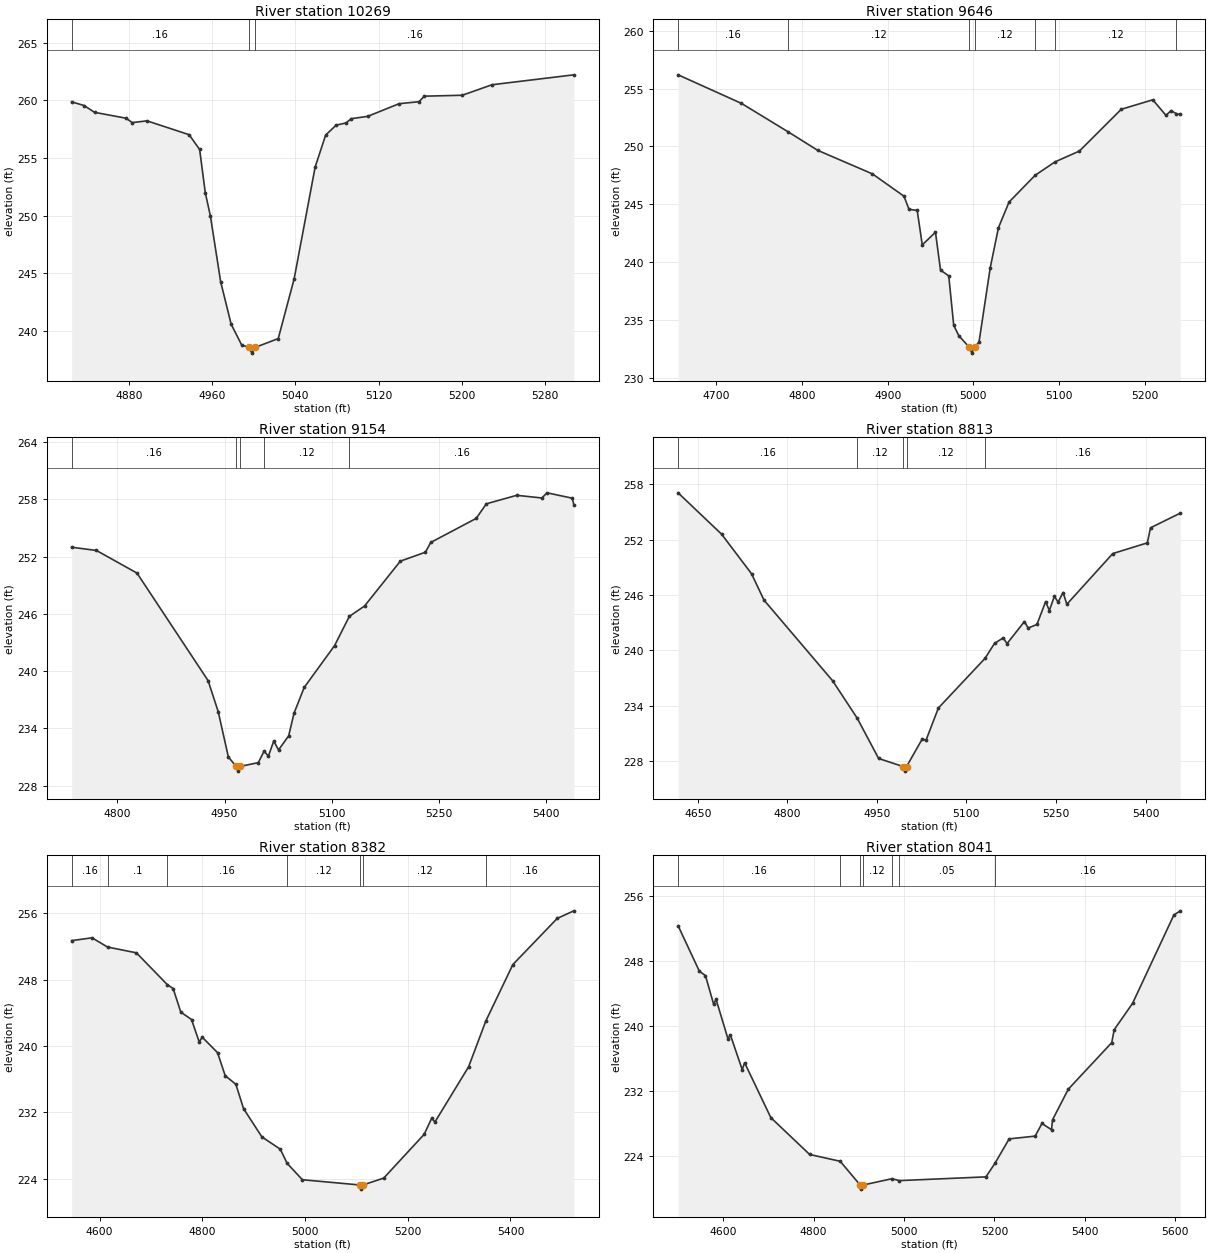
Type RM Length L Ch R = 1 ,10269   ,623,623,623
BEGIN DESCRIPTION:
UNT0479 IN WICK 10.0
END DESCRIPTION:
XS GIS Cut Line= 2
      3596215.59     10243963.43      3596146.31     10243485.42
#Sta/Elev= 30
  4824.8  259.86  4836.7  259.54  4846.8  258.95  4877.1  258.44  4883.1  258.06
  4897.3  258.21  4937.8  257.01  4947.9  255.73  4953.3     252  4958.3  249.94
  4968.1  244.27  4978.2  240.59  4988.3  238.79  4995.4  238.58  4998.1  238.08
  5001.4  238.58  5023.5  239.34  5038.8  244.52    5059  254.21  5069.1  256.98
  5079.2  257.84  5088.7  258.03  5093.7   258.4  5109.5   258.6  5139.8   259.7
  5158.9  259.87    5164  260.35  5200.5  260.43  5229.1  261.34  5307.8   262.2
#Mann= 3 ,-1 , 0
  4824.8     .16       0  4995.4     .07       0  5001.4     .16       0
Bank Sta=4995.4,5001.4
XS Rating Curve= 0 ,0
Exp/Cntr=0.3,0.1

Type RM Length L Ch R = 1 ,9646    ,492,492,492
BEGIN DESCRIPTION:
UNT0479 IN WICK 9.0
END DESCRIPTION:
XS GIS Cut Line= 2
      3596472.55     10243984.28      3596972.58     10243678.71
#Sta/Elev= 30
  4655.4  256.19  4729.3  253.72  4784.2  251.24  4818.3  249.66  4882.2  247.62
    4919  245.69  4924.8  244.56  4934.4  244.46  4940.3  241.48  4955.7  242.58
  4961.6   239.3  4971.2   238.8    4977  234.52    4983  233.62  4995.3  232.62
  4998.1  232.12  5001.3  232.62  5006.5  233.07  5019.6   239.5  5029.2  242.97
  5041.6  245.19    5072   247.5  5095.2  248.66  5123.7   249.6  5172.5  253.21
  5209.3  254.03  5224.7  252.68  5230.6   253.1  5236.9  252.82  5241.4  252.76
#Mann= 7 ,-1 , 0
  4655.4     .16       0  4784.2     .12       0  4995.3     .07       0
  5001.3     .12       0    5072     .16       0  5095.2     .12       0
  5236.9     .16       0
Bank Sta=4995.3,5001.3
XS Rating Curve= 0 ,0
Exp/Cntr=0.3,0.1

Type RM Length L Ch R = 1 ,9154    ,341,341,341
BEGIN DESCRIPTION:
UNT0479 IN WICK 8.0
END DESCRIPTION:
XS GIS Cut Line= 2
       3596965.6     10244234.28      3597437.46     10243713.84
#Sta/Elev= 30
  4736.1  252.98  4770.8  252.64  4827.5  250.27  4926.9  239.01  4941.1  235.76
  4955.3  231.01  4966.1  230.02  4968.9  229.52  4972.1  230.02  4997.2  230.41
  5005.3  231.61  5011.3  231.09  5018.8  232.67  5025.5  231.74  5039.7  233.22
  5047.2  235.59  5061.4  238.29  5103.9  242.67  5124.5  245.73  5145.8  246.82
  5195.9  251.52    5231  252.46  5238.4  253.48    5302     256  5316.2  257.53
  5358.7  258.42  5393.9  258.14  5401.1  258.68  5436.4  258.12  5438.6  257.44
#Mann= 5 ,-1 , 0
  4736.1     .16       0  4966.1     .07       0  4972.1     .16       0
  5005.3     .12       0  5124.5     .16       0
Bank Sta=4966.1,4972.1
XS Rating Curve= 0 ,0
Exp/Cntr=0.3,0.1

Type RM Length L Ch R = 1 ,8813    ,431,431,431
BEGIN DESCRIPTION:
UNT0479 IN WICK 7.0
END DESCRIPTION:
XS GIS Cut Line= 3
      3597180.85     10244491.26       3597576.7     10243956.51
      3597521.15     10243789.84
#Sta/Elev= 30
  4617.2  257.07    4690  252.59  4740.1  248.31    4761  245.45  4875.8  236.72
    4917  232.67    4953  228.29  4993.8  227.42  4996.6  226.92  4999.8  227.42
  5026.1  230.41  5032.3  230.26  5053.1  233.76  5131.1  239.13  5147.1  240.76
  5161.7  241.36    5168  240.73  5197.2  243.13  5203.4  242.42  5218.1  242.81
  5232.7  245.29  5238.9  244.32  5247.3  245.86  5253.5  245.23  5261.9  246.27
  5268.2     245  5345.1  250.49    5403  251.65  5408.3  253.28  5458.2  254.87
#Mann= 5 ,-1 , 0
  4617.2     .16       0    4917     .12       0  4993.8     .07       0
  4999.8     .12       0  5131.1     .16       0
Bank Sta=4993.8,4999.8
XS Rating Curve= 0 ,0
Exp/Cntr=0.3,0.1

Type RM Length L Ch R = 1 ,8382    ,341,341,341
BEGIN DESCRIPTION:
UNT0479 IN WICK 6.0
END DESCRIPTION:
XS GIS Cut Line= 2
      3597535.03     10244630.13      3598094.07     10243828.03
#Sta/Elev= 30
  4545.7  252.69  4585.4  253.03  4615.5  251.92  4671.8  251.22  4732.1  247.38
  4743.3  246.92  4758.2  244.08  4779.1  243.19    4794  240.49    4800  241.06
  4829.7   239.2  4844.6  236.43  4865.5  235.38  4880.3  232.46  4916.1  229.05
  4951.9  227.57  4965.2  225.87  4994.9  223.89  5106.8  223.26  5109.6  222.76
  5112.8  223.26  5153.3  224.09    5232  229.36  5246.8  231.31  5252.9  230.84
  5318.4  237.48  5352.1  243.02  5404.7  249.81  5491.1  255.37  5523.4  256.28
#Mann= 7 ,-1 , 0
  4545.7     .16       0  4615.5      .1       0  4732.1     .16       0
  4965.2     .12       0  5106.8     .07       0  5112.8     .12       0
  5352.1     .16       0
Bank Sta=5106.8,5112.8
XS Rating Curve= 0 ,0
Exp/Cntr=0.3,0.1

Type RM Length L Ch R = 1 ,8041    ,443,443,443
BEGIN DESCRIPTION:
UNT0479 IN WICK 5.0
END DESCRIPTION:
XS GIS Cut Line= 4
      3597694.72     10244682.22      3597892.68     10244616.23
      3598229.48      10244095.4      3598180.87     10243817.63
#Sta/Elev= 30
  4500.4  252.39  4547.4  246.79  4560.9  246.25    4579  242.72  4584.3  243.33
  4610.6  238.47  4615.9  238.96  4642.2  234.66  4647.5  235.51  4705.5  228.75
  4791.4  224.21    4859  223.37  4903.2  220.44    4906  219.94  4909.2  220.44
  4973.1  221.22  4990.1  220.99  5181.3  221.45  5201.3  223.12  5232.7  226.13
  5290.1  226.47  5305.3  228.03  5326.4  227.26  5328.6  228.48  5363.6  232.26
  5459.6  237.99  5465.1  239.59  5505.7  242.83  5597.1  253.72  5611.3  254.23
#Mann= 7 ,-1 , 0
  4500.4     .16       0    4859     .12       0  4903.2    .035       0
  4909.2     .12       0  4973.1     .16       0  4990.1     .05       0
  5201.3     .16       0
Bank Sta=4903.2,4909.2
XS Rating Curve= 0 ,0
Exp/Cntr=0.3,0.1

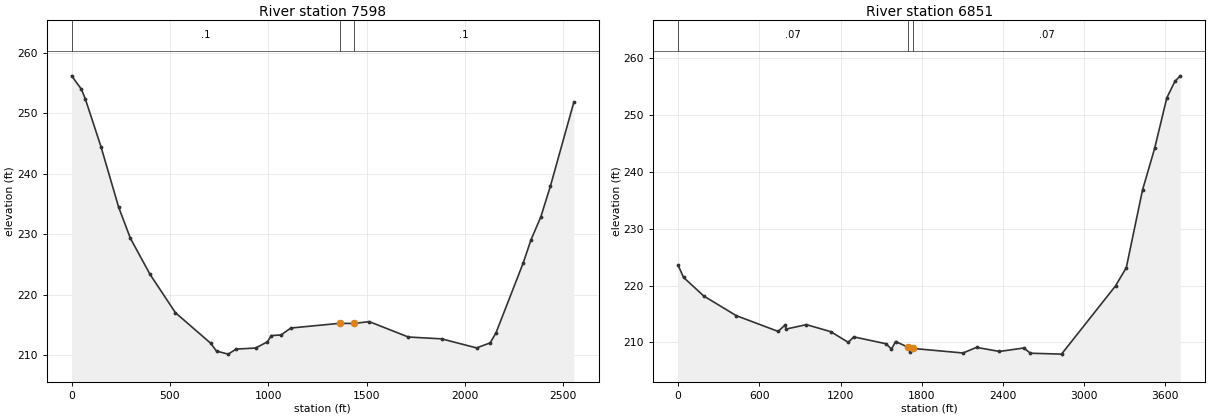
Type RM Length L Ch R = 1 ,7598    ,747,747,747
BEGIN DESCRIPTION:
UNT0479 IN WICK 1.0
END DESCRIPTION:
XS GIS Cut Line= 3
     3597582.861    10245618.129     3598671.393    10244198.904
     3598391.222    10243519.145
#Sta/Elev= 30
       0  256.23   49.77     254   69.68  252.39   149.3  244.49  238.89   234.5
  298.61  229.36  398.15   223.4  527.54  217.04  706.71  211.99  736.57  210.68
  796.29  210.18  836.11  211.01  935.64  211.19  995.37  212.22 1015.27  213.24
 1065.04  213.36 1114.81   214.5 1363.65  215.28 1433.33  215.25 1512.96  215.56
 1712.03  213.01 1880.82  212.71 2058.91  211.21 2128.16  212.04 2157.84  213.71
 2296.35  225.28 2335.92  229.12 2385.39  232.86 2434.86  238.03 2553.58  251.87
#Mann= 3 , 0 , 0
       0      .1       0 1363.65     .05       0 1433.33      .1       0
#XS Ineff= 2 , 0
       0 1341.16  214.88 1458.87       0  214.95
Permanent Ineff=
       T       T
Bank Sta=1363.65,1433.33
XS Rating Curve= 0 ,0
Exp/Cntr=0.3,0.1

Type RM Length L Ch R = 1 ,6851    ,0,0,0
XS GIS Cut Line= 4
     3597853.846    10245824.812     3598767.845    10245452.782
     3599107.724    10244469.888     3598804.589    10242807.236
#Sta/Elev= 30
       0   223.6   39.94  221.46  189.72  218.18  429.37  214.73  738.92  211.95
  788.85  213.04  798.83  212.37  948.61  213.14 1128.15   211.9 1257.78  210.02
 1297.67  210.99 1536.99  209.77 1576.87  208.82 1606.79  210.17 1696.53   209.2
 1716.47   208.3 1736.41  208.95 2105.38  208.15 2205.11  209.14 2374.66  208.42
 2554.19  209.03 2604.06  208.11 2833.45  207.95  3232.4  219.96 3312.18  223.18
 3431.87  236.84 3521.63  244.18 3611.39  253.06 3671.24  255.97 3711.13  256.94
#Mann= 3 , 0 , 0
       0     .07       0 1696.53     .03       0 1736.41     .07       0
Bank Sta=1696.53,1736.41
XS Rating Curve= 0 ,0
Exp/Cntr=0.3,0.1

Chan Stop Cuts=-1
Use User Specified Reach Order=0
Composite Channel Slope=5