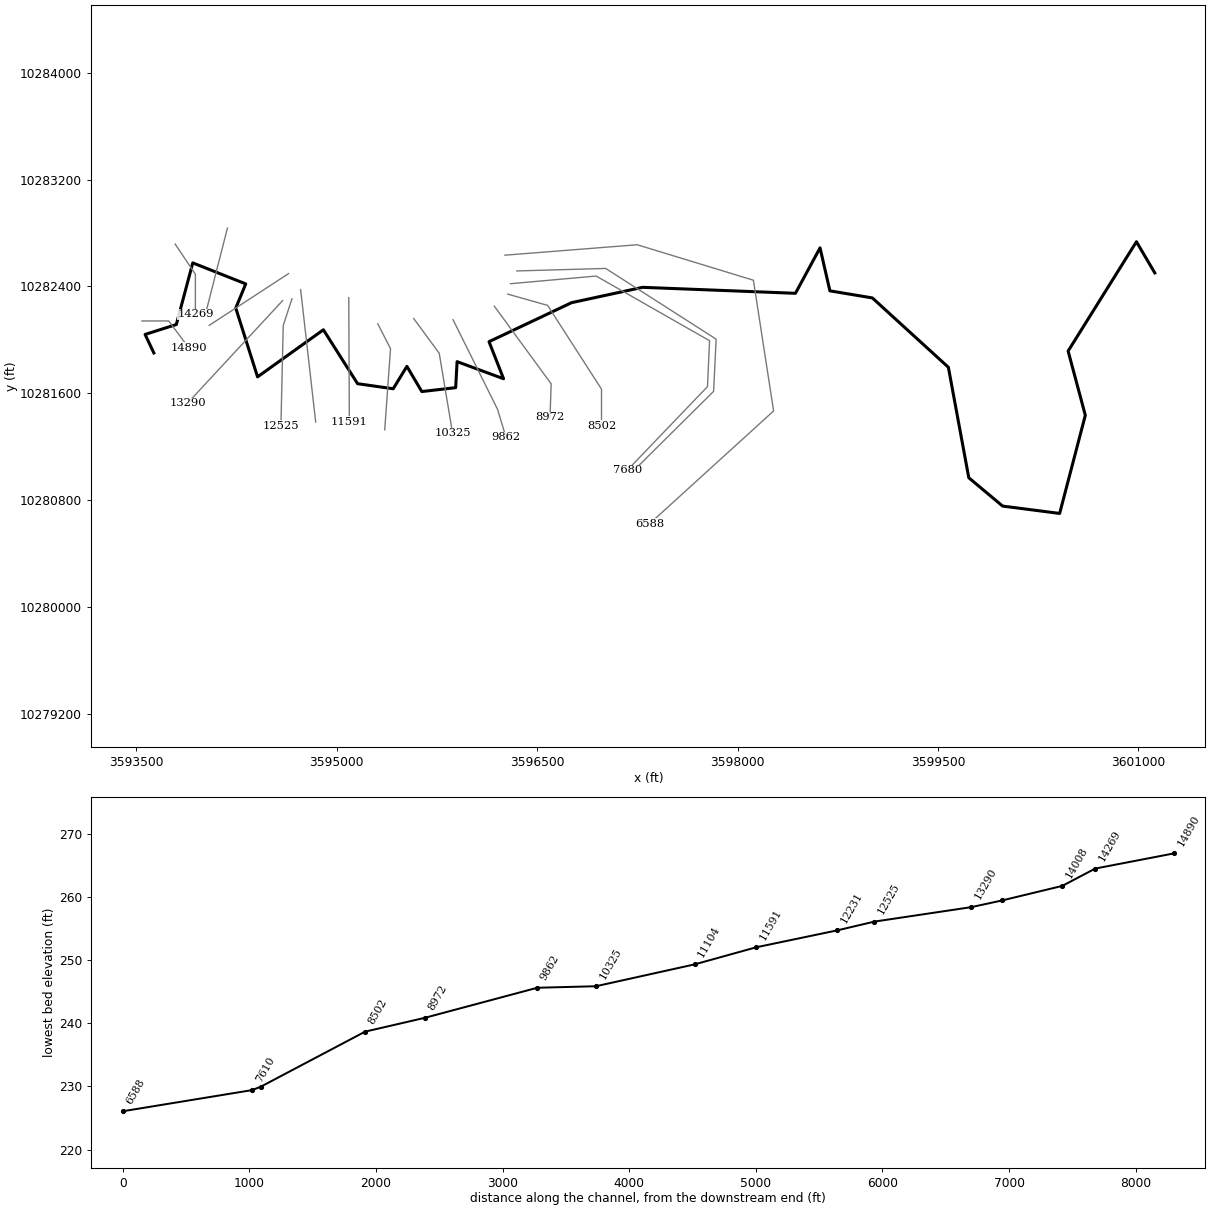
--- NAVASOTARIVTRIB9.prj (project) ---

Proj Title=NAVASOTA RIVER TRIB 9
Current Plan=p01
Default Exp/Contr=0.3,0.1
English Units
Geom File=g01
Flow File=f01
Plan File=p01
Y Axis Title=Elevation
X Axis Title(PF)=Main Channel Distance
X Axis Title(XS)=Station
BEGIN DESCRIPTION:
UNT0461 IN WICK
END DESCRIPTION:
DSS Export Rating Curves= 0
DSS Export Rating Curve Sorted= 0
DSS Export Volume Flow Curves= 0
DXF Filename=UNT0461 IN WICK.
DXF OffsetX= 0
DXF OffsetY= 0
DXF ScaleX= 1
DXF ScaleY= 10

--- NAVASOTARIVTRIB9.p01 (plan) ---

Plan Title=Multiple Run
Short Identifier=Multiple
Geom File=g01
Flow File=f01
Subcritical Flow
K Sum by GR= 0
Std Step Tol= 0.01
Critical Tol= 0.01
Num of Std Step Trials= 20
Max Error Tol= 0.3
Flow Tol Ratio= 0.001
Split Flow NTrial= 30
Split Flow Tol= 0.02
Split Flow Ratio= 0.02
Log Output Level= 0
Friction Slope Method= 1
Unsteady Friction Slope Method= 2
Unsteady Bridges Friction Slope Method= 1
Parabolic Critical Depth
Global Vel Dist=  1 , 1 , 1
Global Log Level= 0
CheckData=True
Encroach Param= -1, 0, 0, 0
BEGIN DESCRIPTION:
Multiple Run
END DESCRIPTION:

--- NAVASOTARIVTRIB9.f01 (steady flow) ---

Flow Title=Multiple
Program Version=4.10
Number of Profiles= 7
Profile Names=10-year,25-year,50-year,1pct_min,100-year,1pct_plu,500-year
River Rch & RM=UNT0461 IN WICK,Reach-1         ,14890
     527     697     834     730     987    1335    1387
River Rch & RM=AVASOTARIVTRIB99,Reach-1         ,14890
     527     697     834     730     987    1335    1387
River Rch & RM=NAVASOTARIVTRIB9,Reach-1         ,14890
     527     697     834     730     987    1335    1387
Boundary for River Rch & Prof#=NAVASOTARIVTRIB9,Reach-1         , 1
Up Type= 0
Dn Type= 3
Dn Slope=0.0063
Boundary for River Rch & Prof#=NAVASOTARIVTRIB9,Reach-1         , 2
Up Type= 0
Dn Type= 3
Dn Slope=0.0063
Boundary for River Rch & Prof#=NAVASOTARIVTRIB9,Reach-1         , 3
Up Type= 0
Dn Type= 3
Dn Slope=0.0063
Boundary for River Rch & Prof#=NAVASOTARIVTRIB9,Reach-1         , 4
Up Type= 0
Dn Type= 3
Dn Slope=0.0063
Boundary for River Rch & Prof#=NAVASOTARIVTRIB9,Reach-1         , 5
Up Type= 0
Dn Type= 3
Dn Slope=0.0063
Boundary for River Rch & Prof#=NAVASOTARIVTRIB9,Reach-1         , 6
Up Type= 0
Dn Type= 3
Dn Slope=0.0063
Boundary for River Rch & Prof#=NAVASOTARIVTRIB9,Reach-1         , 7
Up Type= 0
Dn Type= 3
Dn Slope=0.0063
DSS Import GetInterval= 0
DSS Import GetPeak= 0
DSS Import FillOption= 0

--- NAVASOTARIVTRIB9.g01 (geometry) ---

Geom Title=Existing Conditions
Program Version=4.10

River Reach=NAVASOTARIVTRIB9,Reach-1
Reach XY= 30
       3593631.4     10281901.99      3593565.78     10282040.53
      3593799.63     10282115.01      3593922.55     10282576.47
       3594318.9     10282419.18      3594244.42     10282237.93
      3594407.44     10281722.82      3594900.15     10282075.43
      3595155.88     10281671.78      3595422.55     10281633.76
      3595525.15     10281801.47      3595636.61     10281612.93
      3595890.26     10281642.09      3595900.67     10281836.89
      3596248.59     10281708.76      3596139.74     10281986.36
      3596757.44     10282278.55      3597289.19     10282393.45
      3598432.97     10282348.71      3598617.02     10282688.89
      3598690.84     10282367.02      3599008.45     10282314.11
      3599577.43     10281794.72       3599730.3     10280967.24
      3599983.58     10280755.15      3600410.23     10280700.06
      3600602.41     10281435.15      3600473.66     10281916.19
      3600984.87     10282734.99      3601122.16     10282501.71

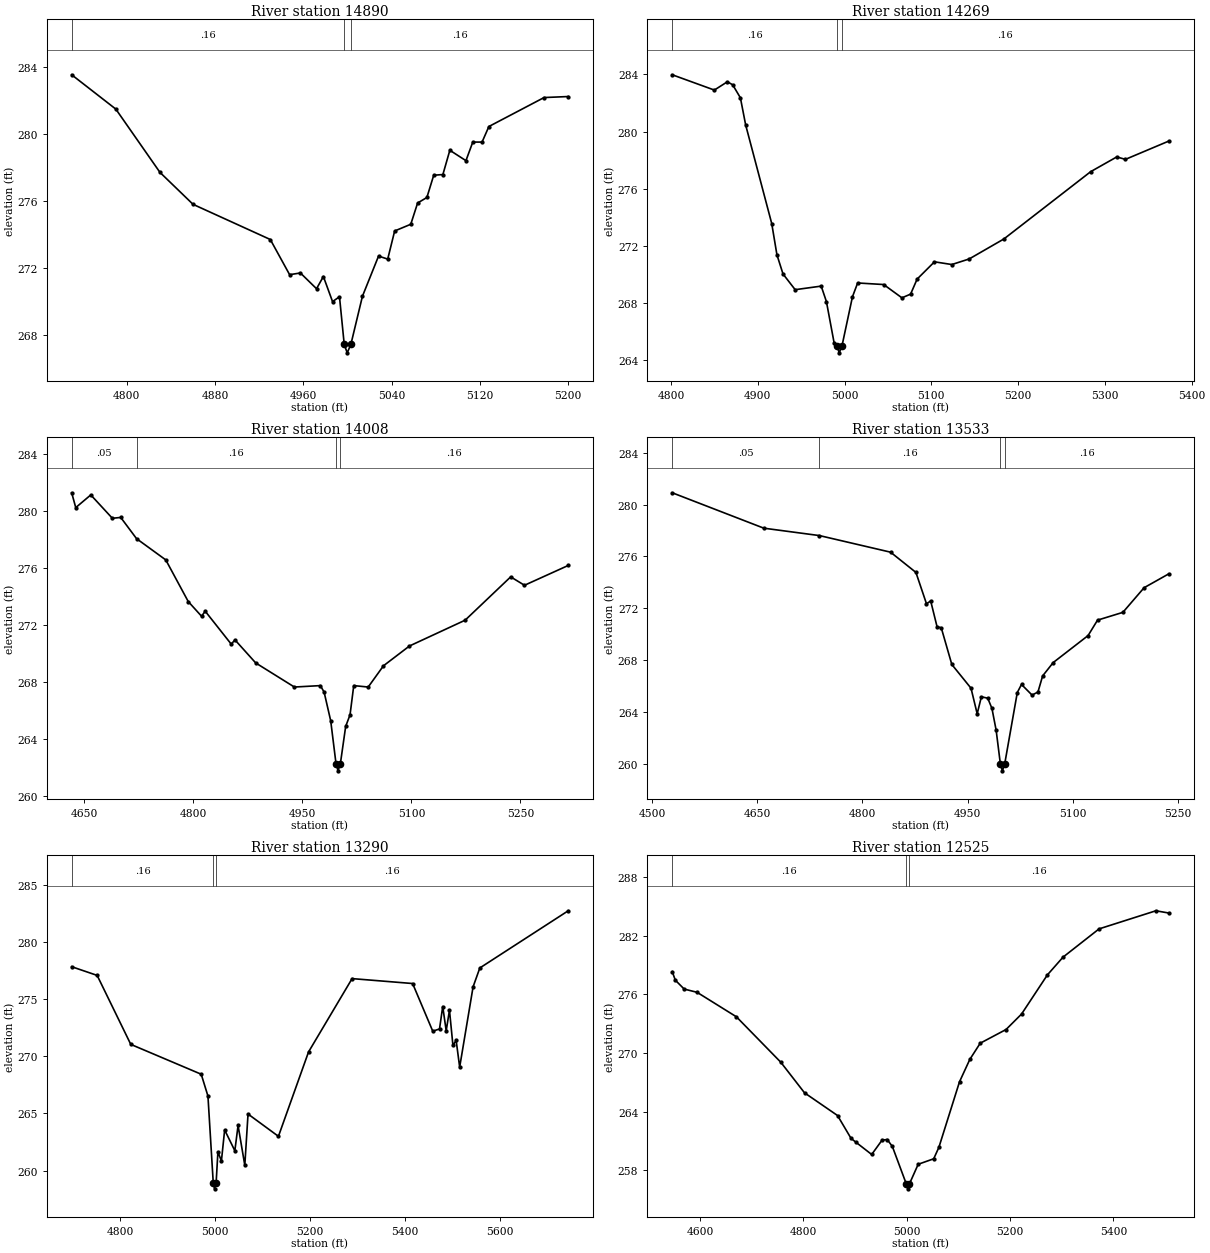
Type RM Length L Ch R = 1 ,14890   ,621,621,621
BEGIN DESCRIPTION:
UNT0461 IN WICK 15.0
END DESCRIPTION:
XS GIS Cut Line= 3
      3593542.12     10282141.64      3593742.11     10282141.64
      3593892.11     10281941.63
#Sta/Elev= 30
    4750  283.53    4790  281.48    4830   277.7    4860  275.79    4930  273.69
  4947.5  271.59  4957.3  271.69  4971.9  270.75  4978.1  271.48  4986.4  269.98
  4992.7  270.27    4997  267.42  4999.7  266.92    5003  267.42  5013.5   270.3
  5028.1   272.7  5036.4  272.52  5042.7   274.2  5057.3   274.6  5063.5  275.87
  5071.9   276.2  5078.1  277.53  5086.4  277.57  5092.7  279.02  5107.3   278.4
  5113.5  279.51  5121.9  279.51  5128.1  280.44  5178.1  282.17    5200  282.23
#Mann= 3 ,-1 , 0
    4750     .16       0    4997     .07       0    5003     .16       0
Bank Sta=4997,5003
XS Rating Curve= 0 ,0
Exp/Cntr=0.3,0.1

Type RM Length L Ch R = 1 ,14269   ,261,261,261
BEGIN DESCRIPTION:
UNT0461 IN WICK 14.0
END DESCRIPTION:
XS GIS Cut Line= 3
      3593790.51     10282717.63      3593942.11     10282491.64
      3593942.11     10282191.67
#Sta/Elev= 30
  4801.5  283.98    4850  282.91    4865  283.49  4871.1  283.28    4880  282.37
  4886.1  280.46  4916.1  273.57  4922.1  271.38  4929.1  270.04  4943.1  268.94
  4973.1  269.19  4979.1  268.11  4988.1  265.18  4991.1  265.02  4993.9  264.52
  4997.1  265.02  5009.1  268.44  5015.1  269.41  5045.1   269.3  5066.1  268.37
  5076.1  268.63  5083.6  269.68  5103.6  270.89  5123.6   270.7  5143.6  271.09
  5183.6  272.49  5283.6   277.2  5313.6  278.23  5323.6  278.06  5373.6  279.34
#Mann= 3 ,-1 , 0
  4801.5     .16       0  4991.1     .07       0  4997.1     .16       0
Bank Sta=4991.1,4997.1
XS Rating Curve= 0 ,0
Exp/Cntr=0.3,0.1

Type RM Length L Ch R = 1 ,14008   ,475,475,475
BEGIN DESCRIPTION:
Mapping XS 49da470e
END DESCRIPTION:
XS GIS Cut Line= 2
      3594181.92      10282837.1      3594013.12     10282174.87
#Sta/Elev= 30
  4632.4  281.28    4638  280.24  4658.7  281.13  4688.4  279.49  4699.9  279.55
  4721.7  278.06  4761.9  276.57  4792.8  273.65  4811.1  272.62  4816.2  272.97
    4852  270.66  4857.1  270.96  4885.7  269.34  4938.9  267.65  4974.6  267.75
  4979.8   267.3  4988.9  265.28  4996.2  262.27    4999  261.77  5002.2  262.27
  5009.5  264.89  5015.5   265.7  5020.6  267.75  5040.5  267.65  5061.5  269.14
  5097.3  270.53  5173.9  272.34  5236.6  275.38  5255.6  274.79  5315.8  276.18
#Mann= 4 ,-1 , 0
  4632.4     .05       0  4721.7     .16       0  4996.2     .07       0
  5002.2     .16       0
Bank Sta=4996.2,5002.2
XS Rating Curve= 0 ,0
Exp/Cntr=0.3,0.1

Type RM Length L Ch R = 1 ,13533   ,243,243,243
BEGIN DESCRIPTION:
UNT0461 IN WICK 13.0
END DESCRIPTION:
XS GIS Cut Line= 2
      3594639.42     10282496.29      3594045.58     10282108.58
#Sta/Elev= 30
  4528.3  280.91  4659.1  278.18  4738.5  277.61  4840.1  276.33  4876.3  274.77
  4891.4  272.35  4897.4  272.57  4906.5  270.58  4912.5   270.5  4927.6  267.67
    4955  265.84  4963.8  263.87  4969.8  265.18  4978.9  265.07  4984.9  264.28
  4990.9   262.6    4997  259.97  4999.8  259.47    5003  259.97  5021.1  265.51
  5027.1  266.13  5042.2  265.31  5050.6  265.55  5057.3  266.79  5072.4  267.82
  5122.2   269.9  5135.7  271.09  5171.9  271.69  5202.2  273.59  5237.5  274.66
#Mann= 4 ,-1 , 0
  4528.3     .05       0  4738.5     .16       0    4997     .07       0
    5003     .16       0
Bank Sta=4997,5003
XS Rating Curve= 0 ,0
Exp/Cntr=0.3,0.1

Type RM Length L Ch R = 1 ,13290   ,765,765,765
BEGIN DESCRIPTION:
UNT0461 IN WICK 12.0
END DESCRIPTION:
XS GIS Cut Line= 2
       3594595.3     10282294.25      3593883.77     10281526.31
#Sta/Elev= 30
  4697.4  277.83  4751.1  277.07    4822  271.04  4970.5  268.43  4984.7  266.52
  4995.9  258.91  4998.6  258.41  5001.9  258.91  5005.7  261.64  5013.1  260.85
  5019.9  263.56  5041.4  261.74  5048.2  263.95  5062.4  260.47  5069.2  264.95
  5133.3     263  5196.8  270.38  5288.6  276.79  5416.2  276.36  5458.7  272.19
  5472.9  272.39  5479.7  274.35    5487  272.23  5493.9  274.03  5501.2  270.95
    5508  271.39  5515.4  269.05  5543.7  276.07  5557.9  277.72  5744.3  282.72
#Mann= 3 ,-1 , 0
  4697.4     .16       0  4995.9     .07       0  5001.9     .16       0
Bank Sta=4995.9,5001.9
XS Rating Curve= 0 ,0
Exp/Cntr=0.3,0.1

Type RM Length L Ch R = 1 ,12525   ,294,294,294
BEGIN DESCRIPTION:
UNT0461 IN WICK 11.0
END DESCRIPTION:
XS GIS Cut Line= 3
      3594664.73     10282307.24      3594599.62     10282107.59
      3594582.26     10281356.69
#Sta/Elev= 30
  4546.3  278.31  4552.2  277.44  4569.4  276.53  4594.3   276.2  4670.4   273.7
  4756.3  269.06  4802.3  265.93  4866.2  263.61  4892.3  261.28  4902.3  260.86
  4932.3  259.63  4952.3  261.09  4962.3  261.16  4972.3  260.45  4999.3  256.62
  5002.1  256.12  5005.3  256.62  5022.3  258.63  5052.3  259.19  5062.3  260.35
  5102.3  267.06  5122.3  269.35  5142.4     271  5192.4   272.4  5222.4  273.98
  5272.4  277.98  5302.6  279.79  5372.4  282.68  5482.4  284.53  5507.4   284.3
#Mann= 3 ,-1 , 0
  4546.3     .16       0  4999.3     .07       0  5005.3     .16       0
Bank Sta=4999.3,5005.3
XS Rating Curve= 0 ,0
Exp/Cntr=0.3,0.1

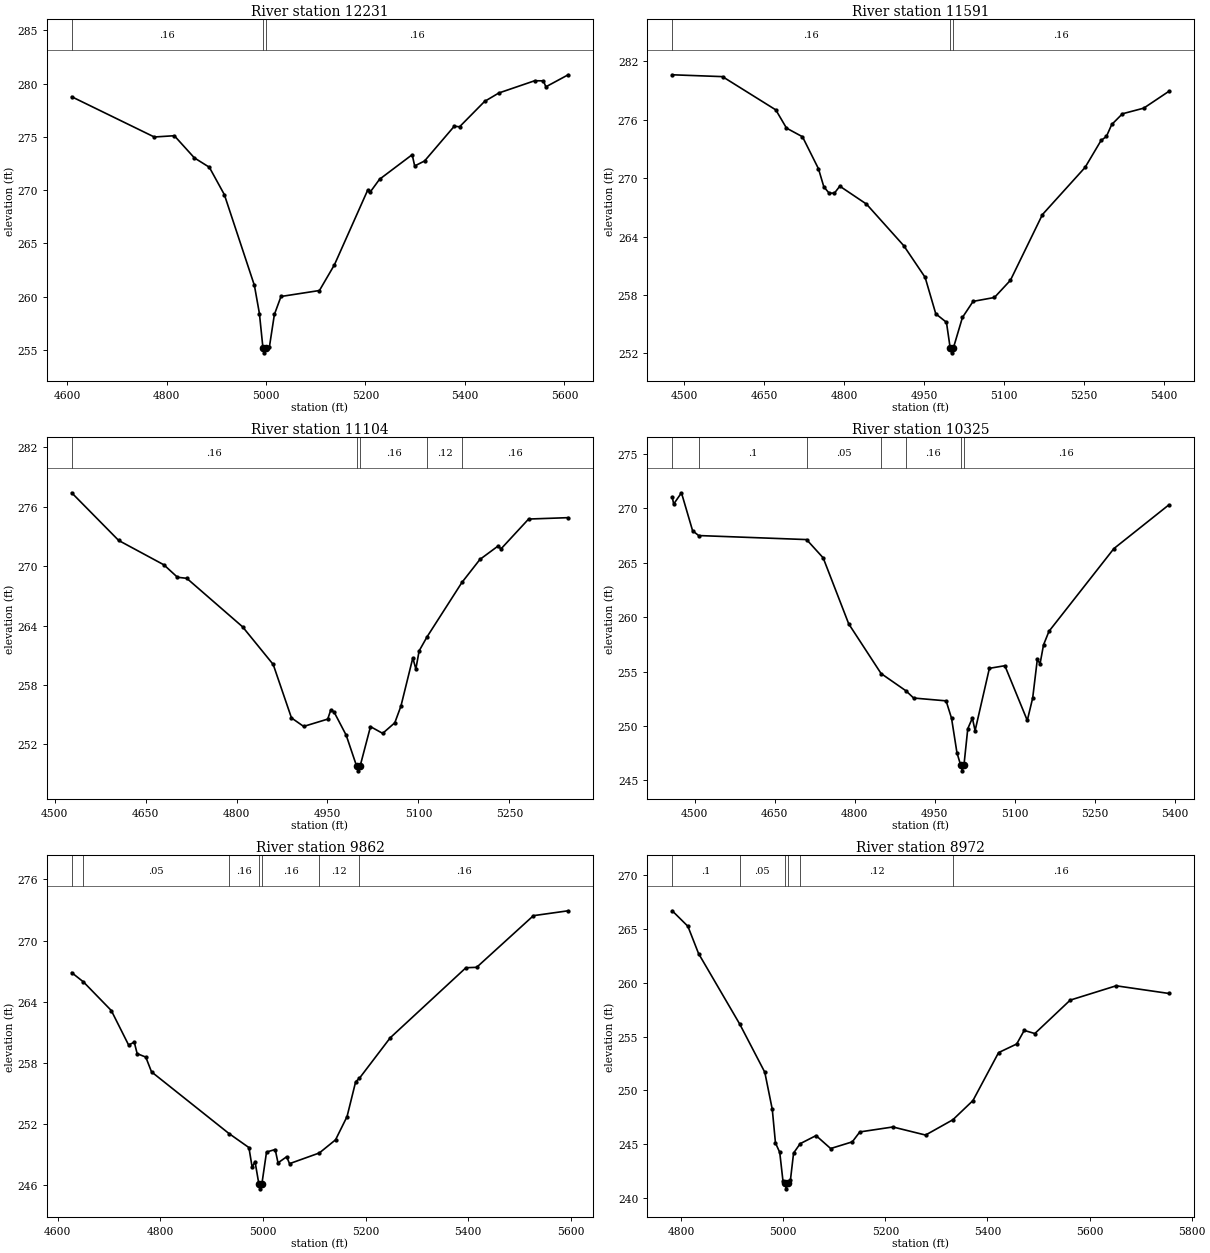
Type RM Length L Ch R = 1 ,12231   ,640,640,640
BEGIN DESCRIPTION:
UNT0461 IN WICK 10.0
END DESCRIPTION:
XS GIS Cut Line= 2
      3594729.83     10282376.69      3594842.46     10281384.66
#Sta/Elev= 30
  4609.2  278.77  4775.3  274.99  4815.6  275.11  4855.9  273.03    4886  272.15
  4916.2  269.58  4976.6  261.06  4986.7  258.42  4993.7  255.23  4996.5  254.73
  4999.7  255.23  5006.8  255.29  5016.8  258.33  5030.1  260.02  5107.4  260.58
  5137.6     263  5204.3  269.99  5209.3  269.81  5228.2  271.02  5293.9  273.33
  5298.9  272.27  5318.8  272.74  5378.5     276  5389.2  275.95  5439.5  278.33
  5468.1  279.12  5540.2  280.27  5557.7  280.26  5562.7   279.7  5607.6  280.83
#Mann= 3 ,-1 , 0
  4609.2     .16       0  4993.7     .07       0  4999.7     .16       0
Bank Sta=4993.7,4999.7
XS Rating Curve= 0 ,0
Exp/Cntr=0.3,0.1

Type RM Length L Ch R = 1 ,11591   ,487,487,487
BEGIN DESCRIPTION:
UNT0461 IN WICK 9.0
END DESCRIPTION:
XS GIS Cut Line= 2
      3595090.07     10282315.94       3595094.4     10281384.75
#Sta/Elev= 30
  4477.9  280.63  4572.2  280.44  4672.2  277.02  4692.2  275.15  4722.2  274.26
  4752.2  270.97  4762.2  269.12  4772.2  268.46  4782.2  268.47  4792.2  269.18
  4842.2  267.34  4912.2  263.06  4952.2  259.81  4972.2  256.06  4992.2  255.19
  4999.2  252.55  5001.9  252.05  5005.2  252.55  5022.2  255.69  5042.2  257.34
  5082.2  257.74  5112.2  259.51  5172.2  266.26  5252.2  271.11  5282.2  273.88
  5292.2  274.29  5302.2  275.52  5322.2  276.62  5362.2   277.2  5409.1  278.92
#Mann= 3 ,-1 , 0
  4477.9     .16       0  4999.2     .07       0  5005.2     .16       0
Bank Sta=4999.2,5005.2
XS Rating Curve= 0 ,0
Exp/Cntr=0.3,0.1

Type RM Length L Ch R = 1 ,11104   ,779,779,779
BEGIN DESCRIPTION:
UNT0461 IN WICK 8.0
END DESCRIPTION:
XS GIS Cut Line= 3
      3595307.07     10282120.65      3595402.57     10281933.98
      3595359.18     10281326.51
#Sta/Elev= 30
  4528.2  277.39  4605.7  272.58  4680.3  270.12  4702.6  268.87    4718  268.76
    4810  263.87  4860.5  260.07  4890.6  254.68  4910.7  253.82  4950.4  254.56
  4955.4  255.48  4960.8  255.28  4980.8  252.94  4997.9  249.84  5000.6  249.34
  5003.9  249.84  5020.9   253.8    5041  253.12    5061  254.19  5071.1  255.87
  5090.7  260.73  5095.7  259.61  5101.1  261.44  5114.1  262.85  5171.6  268.34
  5201.4  270.67  5231.1  272.01  5236.1  271.73  5281.6  274.74  5346.9  274.88
#Mann= 5 ,-1 , 0
  4528.2     .16       0  4997.9     .07       0  5003.9     .16       0
  5114.1     .12       0  5171.6     .16       0
Bank Sta=4997.9,5003.9
XS Rating Curve= 0 ,0
Exp/Cntr=0.3,0.1

Type RM Length L Ch R = 1 ,10325   ,463,463,463
BEGIN DESCRIPTION:
UNT0461 IN WICK 7.0
END DESCRIPTION:
XS GIS Cut Line= 3
      3595576.19     10282159.67      3595767.16     10281899.26
      3595866.99     10281300.25
#Sta/Elev= 30
    4458  271.06  4460.7  270.39  4475.3  271.43  4496.2  267.94  4507.5   267.5
  4709.7  267.13  4740.8  265.45  4788.7  259.38  4849.3  254.82  4895.7  253.24
  4910.3  252.57  4971.1  252.31  4981.3  250.71  4991.4  247.55  4998.5  246.38
  5001.3  245.88  5004.5  246.38  5011.7  249.75  5020.3  250.73  5025.4  249.57
  5052.2   255.3  5081.2  255.54  5123.2  250.51  5133.3  252.57    5142  256.12
  5147.1  255.71  5153.6  257.45  5163.8   258.7  5285.4   266.3  5388.2  270.31
#Mann= 7 ,-1 , 0
    4458     .16       0  4507.5      .1       0  4709.7     .05       0
  4849.3      .1       0  4895.7     .16       0  4998.5     .07       0
  5004.5     .16       0
Bank Sta=4998.5,5004.5
XS Rating Curve= 0 ,0
Exp/Cntr=0.3,0.1

Type RM Length L Ch R = 1 ,9862    ,890,890,890
BEGIN DESCRIPTION:
UNT0461 IN WICK 6.0
END DESCRIPTION:
XS GIS Cut Line= 3
      3595870.44     10282151.02      3596203.79     10281479.12
       3596266.3     10281270.75
#Sta/Elev= 30
  4627.1  266.86    4650  265.95  4704.3  263.14    4738  259.76  4749.1  260.03
  4754.7  258.91  4771.5  258.57  4782.7  257.12  4933.6  251.07  4972.5  249.69
  4978.8  247.76  4984.4  248.32  4991.8  246.14  4994.5  245.64  4997.8  246.14
  5006.8  249.25  5023.7   249.5  5029.2  248.19  5046.1  248.79  5051.6  248.11
  5109.7  249.16  5141.3  250.45  5163.7  252.73  5180.5  256.15  5187.8  256.49
  5247.8  260.46  5395.4  267.34  5416.3  267.38  5526.9  272.45  5594.7  272.93
#Mann= 7 ,-1 , 0
  4627.1     .16       0    4650     .05       0  4933.6     .16       0
  4991.8     .07       0  4997.8     .16       0  5109.7     .12       0
  5187.8     .16       0
Bank Sta=4991.8,4997.8
XS Rating Curve= 0 ,0
Exp/Cntr=0.3,0.1

Type RM Length L Ch R = 1 ,8972    ,470,470,470
BEGIN DESCRIPTION:
UNT0461 IN WICK 5.0
END DESCRIPTION:
XS GIS Cut Line= 3
      3596179.47     10282252.15      3596604.83     10281670.52
      3596596.15     10281418.74
#Sta/Elev= 30
  4782.6  266.67  4813.3  265.23  4834.2   262.7  4914.9  256.15  4963.9  251.69
  4978.6  248.24  4984.8  245.13  4993.2  244.25  4999.4  241.64  5003.2  241.37
    5006  240.87  5009.2  241.37  5014.1  241.67  5020.3  244.19  5033.2  245.06
  5064.3  245.81  5092.9  244.61  5135.3  245.23    5150  246.15  5214.8  246.61
  5278.8  245.86  5332.3  247.28  5371.6  249.06  5421.8  253.51  5457.3  254.31
    5472  255.57  5492.8  255.28  5562.1  258.38  5652.1  259.71  5755.1     259
#Mann= 6 ,-1 , 0
  4782.6      .1       0  4914.9     .05       0  5003.2    .035       0
  5009.2     .05       0  5033.2     .12       0  5332.3     .16       0
Bank Sta=5003.2,5009.2
XS Rating Curve= 0 ,0
Exp/Cntr=0.3,0.1

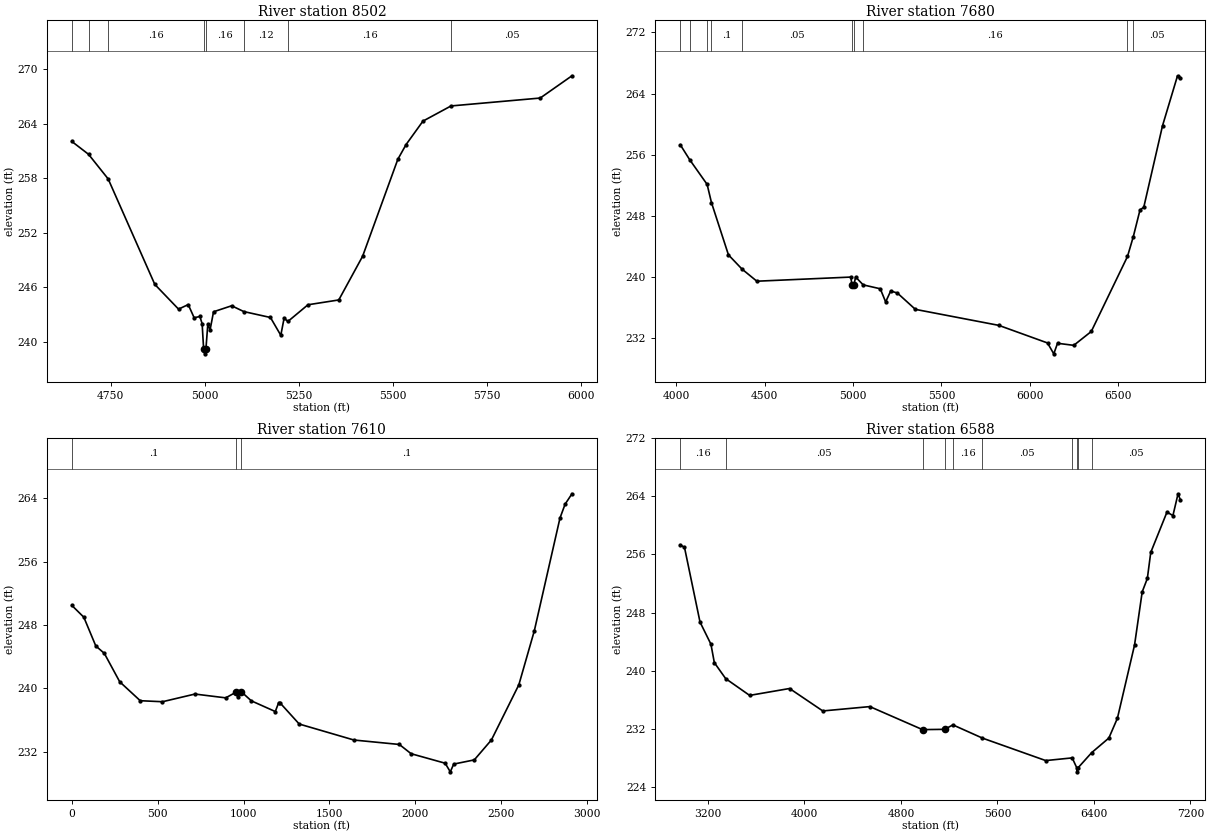
Type RM Length L Ch R = 1 ,8502    ,822,822,822
BEGIN DESCRIPTION:
Mapping XS b3630793
END DESCRIPTION:
XS GIS Cut Line= 4
      3596279.88      10282342.5      3596577.95     10282258.31
      3596981.59      10281630.7      3596981.59     10281357.23
#Sta/Elev= 30
  4646.4  262.06  4690.7  260.65  4742.9  257.94  4866.9  246.33    4930  243.61
  4955.7  244.11  4971.5  242.66  4986.7   242.8  4992.7  242.01  4996.7  239.19
  4999.5  238.69  5002.7  239.19  5007.8  241.96  5013.8  241.32    5023  243.32
  5071.2  243.98  5103.5  243.34  5174.3  242.69  5201.8  240.73  5210.6  242.62
  5220.6  242.25    5274  244.09  5355.9  244.62  5419.3  249.43    5513  260.11
  5534.8  261.72  5579.7   264.3  5654.3  265.97  5891.4  266.84  5975.8  269.29
#Mann= 8 ,-1 , 0
  4646.4     .16       0  4690.7      .1       0  4742.9     .16       0
  4996.7     .07       0  5002.7     .16       0  5103.5     .12       0
  5220.6     .16       0  5654.3     .05       0
Bank Sta=4996.7,5002.7
XS Rating Curve= 0 ,0
Exp/Cntr=0.3,0.1

Type RM Length L Ch R = 1 ,7680    ,70,70,70
BEGIN DESCRIPTION:
Mapping XS a5aee722
END DESCRIPTION:
XS GIS Cut Line= 5
      3596300.65     10282420.63      3596941.32     10282477.93
      3597790.27     10281993.55      3597774.65      10281649.8
       3597175.7     10281024.81
#Sta/Elev= 30
  4021.9   257.3  4074.9  255.36  4173.7  252.13  4198.3  249.75  4294.4  242.92
  4371.3  241.06  4455.1  239.48  4986.6  240.02 4994.19  238.92  5004.2  238.93
    5014  240.03    5057     239  5153.7  238.49  5184.1  236.77  5212.7   238.2
  5250.2  237.94  5352.4   235.8  5824.6  233.71  6100.3  231.41  6135.6  229.99
  6156.9  231.37  6248.7   231.1  6347.8  232.91  6552.8  242.71  6585.7   245.3
  6623.6  248.79    6645  249.15    6751  259.79  6835.9  266.32  6852.3  266.07
#Mann= 10 ,-1 , 0
  4021.9     .16       0  4074.9      .1       0  4173.7     .16       0
  4198.3      .1       0  4371.3     .05       0 4994.19     .03       0
  5004.2     .16       0    5057     .16       0  6552.8     .16       0
  6585.7     .05       0
#Block Obstruct= 2 , 0
                         5088.92          238.77
Bank Sta=4994.19,5004.2
XS Rating Curve= 0 ,0
Exp/Cntr=0.3,0.1

Type RM Length L Ch R = 1 ,7610    ,1022,1022,1022
XS GIS Cut Line= 5
     3596347.746    10282516.151     3597012.755    10282534.904
     3597839.328    10282005.494     3597820.575    10281614.566
     3597207.497    10281005.817
#Sta/Elev= 30
       0  250.46   69.67  248.97  139.33  245.34  189.09   244.4  278.66  240.81
  398.09  238.42  527.47  238.29  716.58  239.26  895.77  238.78   955.5  239.49
  965.46  238.87  985.37  239.57  1045.1   238.4 1184.47  237.05 1204.38  238.19
 1214.34  238.09 1323.85  235.47 1642.41  233.45 1906.72  232.89  1975.2  231.72
 2173.39  230.52 2203.32  229.43 2223.27  230.41    2343  230.94 2442.78  233.46
 2602.42  240.43 2692.22  247.23 2841.88   261.5 2871.82  263.26 2911.73  264.57
#Mann= 3 , 0 , 0
       0      .1       0   955.5     .05       0  985.37      .1       0
#XS Ineff= 2 , 0
       0                   988.1       0  238.81
Permanent Ineff=
       F       T
Bank Sta=955.5,985.37
XS Rating Curve= 0 ,0
Exp/Cntr=0.3,0.1

Type RM Length L Ch R = 1 ,6588    ,0,0,0
BEGIN DESCRIPTION:
UNT0461 IN WICK 1.0
END DESCRIPTION:
XS GIS Cut Line= 5
      3596258.99     10282634.17      3597248.61      10282712.3
       3598118.4     10282446.68      3598269.44     10281467.51
      3597342.39     10280623.79
#Sta/Elev= 30
  2970.8  257.31  3005.6  256.97  3134.4  246.69  3224.7  243.65    3253  241.11
    3347  238.91  3545.7   236.6  3876.7  237.55  4152.1  234.46  4542.2  235.06
  4979.2  231.89 5162.52  231.93  5231.2  232.54  5476.3  230.72  6000.4  227.63
    6220     228  6259.5  226.58  6262.3  226.08  6265.5  226.58    6382  228.73
    6524  230.73    6595  233.46  6736.9  243.53  6800.4  250.85    6843  252.69
  6871.3  256.28  7005.8  261.83  7055.1  261.35  7097.7  264.35  7117.2  263.49
#Mann= 10 ,-1 , 0
  2970.8     .16       0    3347     .05       0  4979.2    .035       0
 5162.52     .16       0  5231.2     .16       0  5476.3     .05       0
    6220     .16       0  6259.5    .035       0  6265.5     .16       0
    6382     .05       0
#Block Obstruct= 2 , 0
                          5335.7          231.64
Bank Sta=4979.2,5162.52
XS Rating Curve= 0 ,0
Exp/Cntr=0.3,0.1

Chan Stop Cuts=-1
Use User Specified Reach Order=0
Composite Channel Slope=5