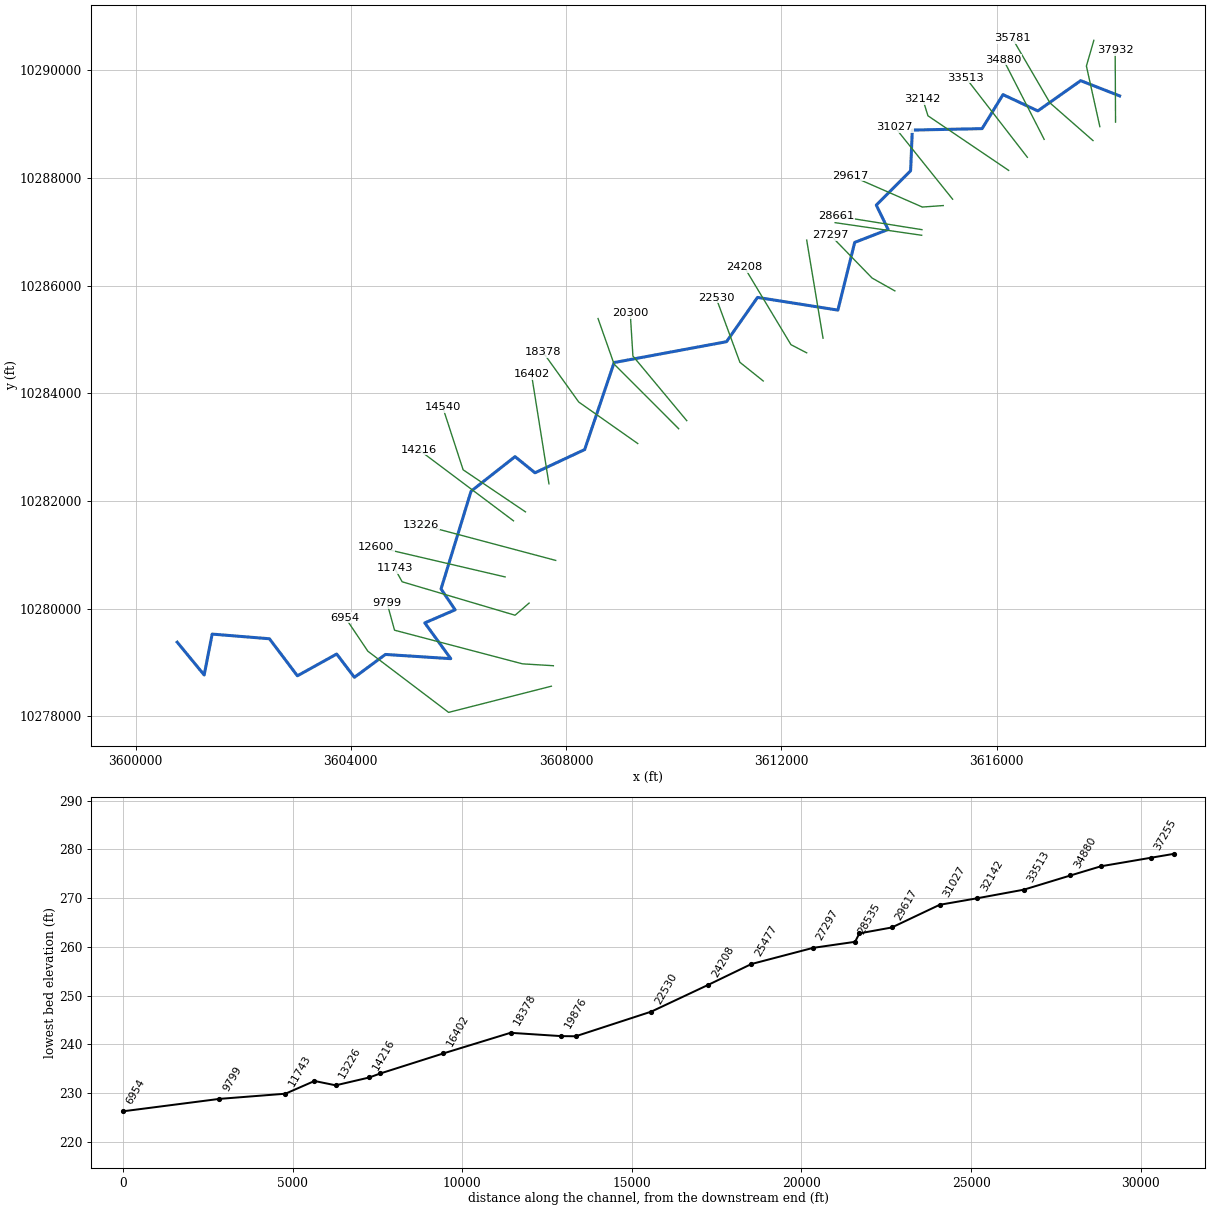
--- NEVILLE CREEK.prj (project) ---

Proj Title=NEVILLE CREEK Base Level Engineering
Current Plan=p01
Default Exp/Contr=0.3,0.1
English Units
Geom File=g01
Flow File=f01
Plan File=p01
Y Axis Title=Elevation
X Axis Title(PF)=Main Channel Distance
X Axis Title(XS)=Station
BEGIN DESCRIPTION:
NEVILLE CREEK
END DESCRIPTION:
DSS Export Rating Curves= 0
DSS Export Rating Curve Sorted= 0
DSS Export Volume Flow Curves= 0
DXF OffsetX= 0
DXF OffsetY= 0
DXF ScaleX= 1
DXF ScaleY= 10

--- NEVILLE CREEK.p01 (plan) ---

Plan Title=Multiple Run
Short Identifier=Multiple
Geom File=g01
Flow File=f01
Subcritical Flow
K Sum by GR= 0
Std Step Tol= 0.01
Critical Tol= 0.01
Num of Std Step Trials= 20
Max Error Tol= 0.3
Flow Tol Ratio= 0.001
Split Flow NTrial= 30
Split Flow Tol= 0.02
Split Flow Ratio= 0.02
Log Output Level= 0
Friction Slope Method= 1
Unsteady Friction Slope Method= 2
Unsteady Bridges Friction Slope Method= 1
Parabolic Critical Depth
Global Vel Dist=  1 , 1 , 1
Global Log Level= 0
CheckData=True
Encroach Param= -1, 0, 0, 0
BEGIN DESCRIPTION:
Multiple Run
END DESCRIPTION:

--- NEVILLE CREEK.f01 (steady flow) ---

Flow Title=Multiple
Number of Profiles=7
Profile Names=10-year,25-year,50-year,1pct_min,100-year,1pct_plu,500-year
River Rch & RM= NEVILLE CREEK,Reach-1,37932
     905    1237    1511    1351    1827    2470    2675
River Rch & RM= NEVILLE CREEK,Reach-1,29617
    1183    1639    2020    1821    2462    3330    3665
River Rch & RM= NEVILLE CREEK,Reach-1,28535
    1312    1821    2247    2026    2740    3705    4083
River Rch & RM= NEVILLE CREEK,Reach-1,20300
    1460    2035    2518    2276    3078    4163    4610
River Rch & RM= NEVILLE CREEK,Reach-1,18378
    1648    2295    2837    2558    3460    4679    5159
Boundary for River Rch & Prof#=NEVILLE CREEK,Reach-1,1
Up Type=0
Dn Type=3
Dn Slope=0.005
Boundary for River Rch & Prof#=NEVILLE CREEK,Reach-1,2
Up Type=0
Dn Type=3
Dn Slope=0.005
Boundary for River Rch & Prof#=NEVILLE CREEK,Reach-1,3
Up Type=0
Dn Type=3
Dn Slope=0.005
Boundary for River Rch & Prof#=NEVILLE CREEK,Reach-1,4
Up Type=0
Dn Type=3
Dn Slope=0.005
Boundary for River Rch & Prof#=NEVILLE CREEK,Reach-1,5
Up Type=0
Dn Type=3
Dn Slope=0.005
Boundary for River Rch & Prof#=NEVILLE CREEK,Reach-1,6
Up Type=0
Dn Type=3
Dn Slope=0.005
Boundary for River Rch & Prof#=NEVILLE CREEK,Reach-1,7
Up Type=0
Dn Type=3
Dn Slope=0.005

--- NEVILLE CREEK.g01 (geometry) ---

Geom Title=Existing Conditions
Program Version=4.10

River Reach=NEVILLE CREEK   ,Reach-1
Reach XY= 30
      3618286.11      10289522.4      3617562.51     10289804.79
       3616766.1     10289243.28      3616119.32     10289545.75
      3615730.83     10288914.07      3614433.85      10288887.1
      3614402.11     10288131.64      3613764.71       10287494.
      3613984.52     10287041.37      3613363.19     10286801.47
      3613051.08     10285544.21      3611557.63     10285780.07
       3610980.8     10284957.45      3608892.95     10284570.58
      3608345.51      10282954.6      3607422.69      10282523.8
      3607051.11      10282823.3      3606234.06       10282181.
      3605676.48     10280366.69      3605938.11      10279979.1
      3605374.34     10279736.24      3605857.46     10279071.78
      3604642.42     10279150.14      3604066.59     10278725.35
      3603737.48     10279157.64      3603006.94     10278753.66
      3602487.53     10279441.55      3601423.22     10279528.06
      3601274.78     10278768.94      3600773.86     10279377.85

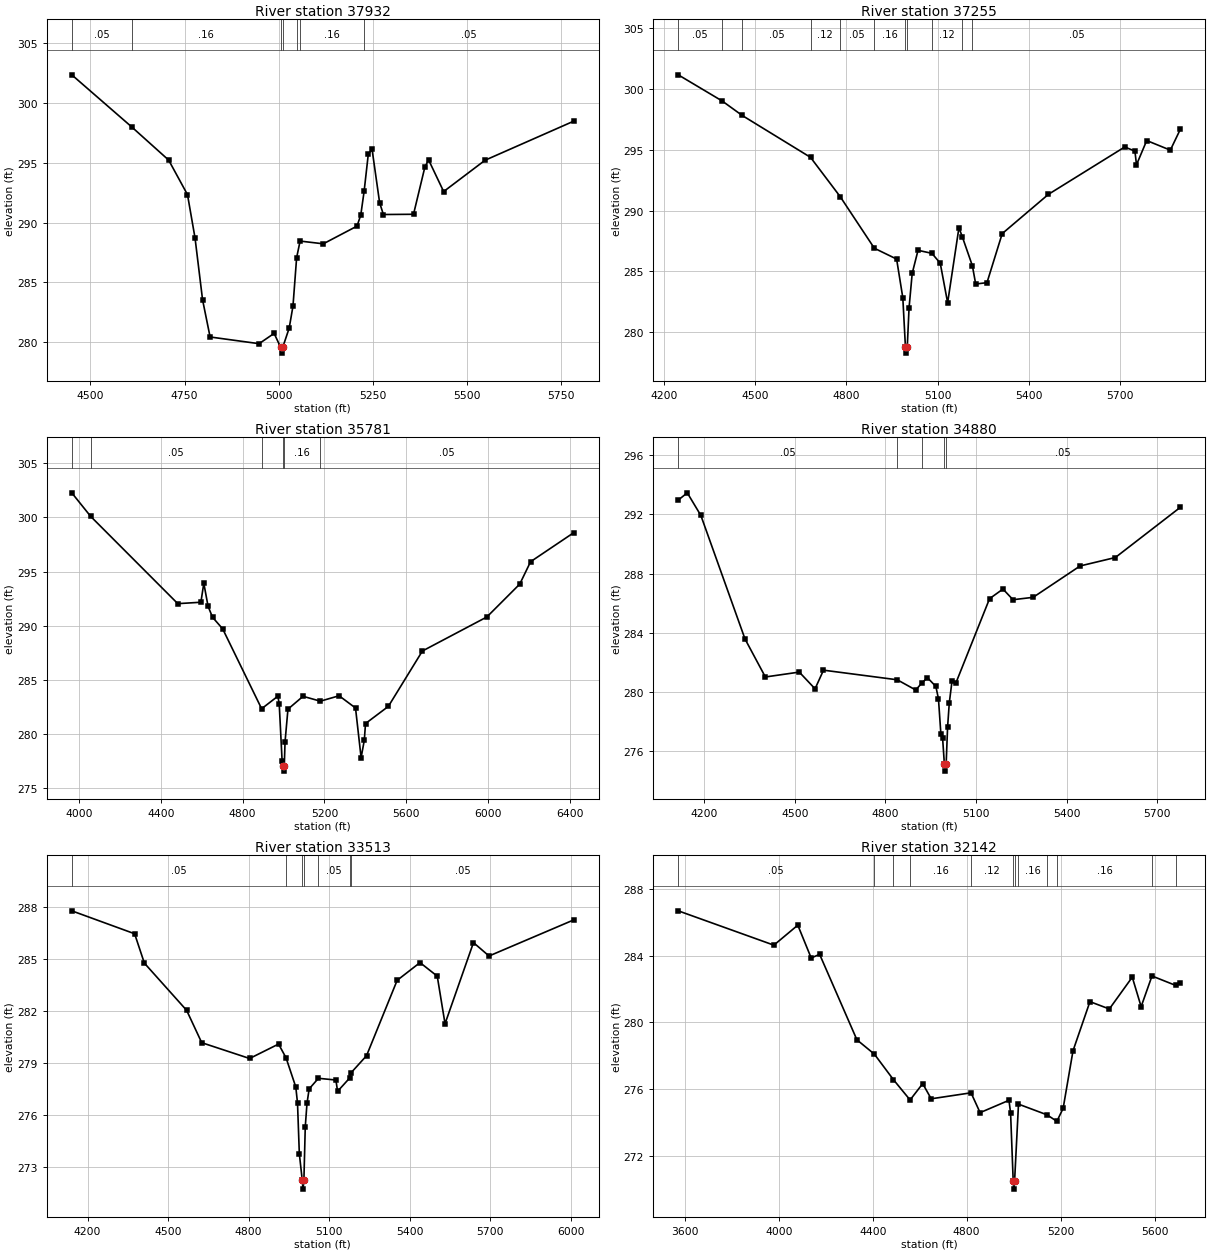
Type RM Length L Ch R = 1 ,37932   ,677,677,677
BEGIN DESCRIPTION:
NEVILLE CREEK 45.0
END DESCRIPTION:
XS GIS Cut Line= 2
      3618210.56     10289034.43      3618203.62     10290367.21
#Sta/Elev= 30
  4450.6  302.36  4609.5  298.01  4707.8  295.23  4757.8  292.34  4777.8  288.72
  4797.8  283.55  4817.8  280.44  4947.8  279.88  4987.8  280.74  5004.8  279.59
  5007.6  279.09  5010.8  279.59  5027.8  281.19  5037.8  283.02  5047.5  287.07
  5056.7  288.46  5118.3  288.23  5207.8  289.71  5217.8  290.64  5226.7  292.63
  5237.8  295.74  5247.8  296.12  5267.8  291.67  5277.8  290.68  5357.8   290.7
  5387.8  294.63  5397.8  295.25  5437.8   292.6  5547.8  295.22  5783.4  298.49
#Mann= 7 ,-1 , 0
  4450.6     .05       0  4609.5     .16       0  5004.8     .07       0
  5010.8     .16       0  5047.5     .12       0  5056.7     .16       0
  5226.7     .05       0
Bank Sta=5004.8,5010.8
XS Rating Curve= 0 ,0
Exp/Cntr=0.3,0.1

Type RM Length L Ch R = 1 ,37255   ,1474,1474,1474
BEGIN DESCRIPTION:
NEVILLE CREEK 44.0
END DESCRIPTION:
XS GIS Cut Line= 3
      3617918.89     10288951.07      3617668.89     10290076.08
      3617807.44     10290554.05
#Sta/Elev= 30
  4247.3  301.16  4391.7  299.01  4457.6  297.82    4682  294.38  4779.3  291.16
  4891.8  286.91    4965  286.02  4985.4  282.84    4994  278.79  4996.7  278.29
    5000  278.79  5005.9  282.01  5016.2  284.84  5035.4  286.74    5081  286.49
  5108.4  285.68  5132.7  282.43  5169.8  288.59  5180.8  287.86    5214  285.47
  5224.9  283.97    5262  284.08    5312  288.11    5464  291.34  5714.7  295.23
  5748.2  294.89  5753.4  293.77    5787  295.76  5864.6  294.97  5897.4  296.68
#Mann= 11 ,-1 , 0
  4247.3     .05       0  4391.7     .16       0  4457.6     .05       0
    4682     .12       0  4779.3     .05       0  4891.8     .16       0
    4994     .07       0    5000     .16       0    5081     .12       0
  5180.8     .16       0    5214     .05       0
Bank Sta=4994,5000
XS Rating Curve= 0 ,0
Exp/Cntr=0.3,0.1

Type RM Length L Ch R = 1 ,35781   ,901,901,901
BEGIN DESCRIPTION:
NEVILLE CREEK 42.0
END DESCRIPTION:
XS GIS Cut Line= 3
      3617792.11     10288691.64      3616992.11     10289391.64
      3616292.09     10290591.67
#Sta/Elev= 30
  3965.7  302.28  4058.1   300.1  4483.5  292.03  4596.4  292.16  4610.6  293.92
  4631.5  291.78  4653.3  290.77  4702.7   289.7    4893  282.31  4972.3  283.47
  4978.9  282.77  4993.1  277.47  4997.7  277.04  5000.5  276.54  5003.7  277.04
  5007.4  279.25  5021.6  282.27  5095.3  283.46  5179.8  283.01  5271.4  283.51
  5351.6  282.38  5378.9  277.79  5394.6   279.4  5400.4  280.94  5512.1  282.53
  5678.3  287.65  5993.3   290.8  6153.8  293.84  6206.7  295.91    6418   298.6
#Mann= 6 ,-1 , 0
  3965.7     .16       0  4058.1     .05       0    4893     .16       0
  4997.7     .07       0  5003.7     .16       0  5179.8     .05       0
Bank Sta=4997.7,5003.7
XS Rating Curve= 0 ,0
Exp/Cntr=0.3,0.1

Type RM Length L Ch R = 1 ,34880   ,1367,1367,1367
BEGIN DESCRIPTION:
NEVILLE CREEK 40.0
END DESCRIPTION:
XS GIS Cut Line= 2
      3616884.16     10288714.99      3616127.21     10290194.16
#Sta/Elev= 30
  4114.5  292.96  4144.4  293.45  4189.4  291.92  4335.4  283.58  4402.8  281.01
  4515.1  281.34  4567.3  280.21  4595.2  281.47  4839.4  280.82  4900.5  280.13
  4920.9  280.61  4939.3  280.96  4967.1  280.37  4975.7  279.54  4983.7  277.16
  4989.3  276.91  4995.2  275.15  4997.9  274.65  5001.2  275.15  5005.9  277.62
  5011.5  279.25  5020.6  280.74  5033.7  280.62  5144.8   286.3  5189.2  286.95
  5222.4  286.23    5289  286.39  5444.5  288.51  5561.1  289.08  5776.1  292.47
#Mann= 5 ,-1 , 0
  4114.5     .05       0  4839.4     .16       0  4920.9     .05       0
  4995.2     .03       0  5001.2     .05       0
Bank Sta=4995.2,5001.2
XS Rating Curve= 0 ,0
Exp/Cntr=0.3,0.1

Type RM Length L Ch R = 1 ,33513   ,1371,1371,1371
BEGIN DESCRIPTION:
NEVILLE CREEK 38.0
END DESCRIPTION:
XS GIS Cut Line= 2
      3616571.69      10288381.6      3615426.45     10289860.01
#Sta/Elev= 30
  4141.3  287.77  4375.4  286.45  4411.7  284.76  4569.2  282.04  4625.3  280.18
  4803.7  279.27  4911.5   280.1  4939.4  279.31  4975.7  277.63  4982.1  276.71
  4988.9  273.79  4999.9  272.25  5002.6  271.75  5005.9  272.25    5011  275.34
  5017.4  276.68  5025.5  277.52    5060  278.13  5125.1  278.03  5131.4  277.38
  5176.6  278.15  5180.6  278.43  5239.2  279.43  5353.3  283.77  5438.4  284.79
  5502.6  284.01  5531.6  281.27  5637.5  285.94  5695.5  285.17  6011.4  287.25
#Mann= 7 ,-1 , 0
  4141.3     .05       0  4939.4     .16       0  4999.9     .07       0
  5005.9     .16       0    5060     .05       0  5176.6     .16       0
  5180.6     .05       0
Bank Sta=4999.9,5005.9
XS Rating Curve= 0 ,0
Exp/Cntr=0.3,0.1

Type RM Length L Ch R = 1 ,32142   ,1115,1115,1115
BEGIN DESCRIPTION:
NEVILLE CREEK 37.0
END DESCRIPTION:
XS GIS Cut Line= 3
      3616224.47     10288138.56      3614724.45     10289152.47
      3614627.23     10289464.95
#Sta/Elev= 30
  3571.8  286.69    3979  284.63  4080.9  285.83  4137.9  283.86  4173.8  284.08
  4332.6  278.95  4406.9  278.09    4488  276.56    4559  275.34  4612.7  276.32
  4648.9  275.41  4818.5  275.77  4857.1  274.58    4980  275.32  4986.9  274.57
    4998  270.49  5000.7  269.99    5004  270.49  5020.6  275.09  5141.8  274.45
    5184  274.06  5210.7  274.84  5252.7  278.29  5324.8  281.24  5407.4   280.8
    5505  282.71  5542.8  280.94    5589  282.78  5690.7  282.21  5709.6  282.36
#Mann= 12 ,-1 , 0
  3571.8     .05       0  4406.9     .16       0    4488     .05       0
    4559     .16       0  4818.5     .12       0    4998     .07       0
    5004     .12       0  5020.6     .16       0  5141.8     .12       0
    5184     .16       0    5589     .12       0  5690.7     .05       0
Bank Sta=4998,5004
XS Rating Curve= 0 ,0
Exp/Cntr=0.3,0.1

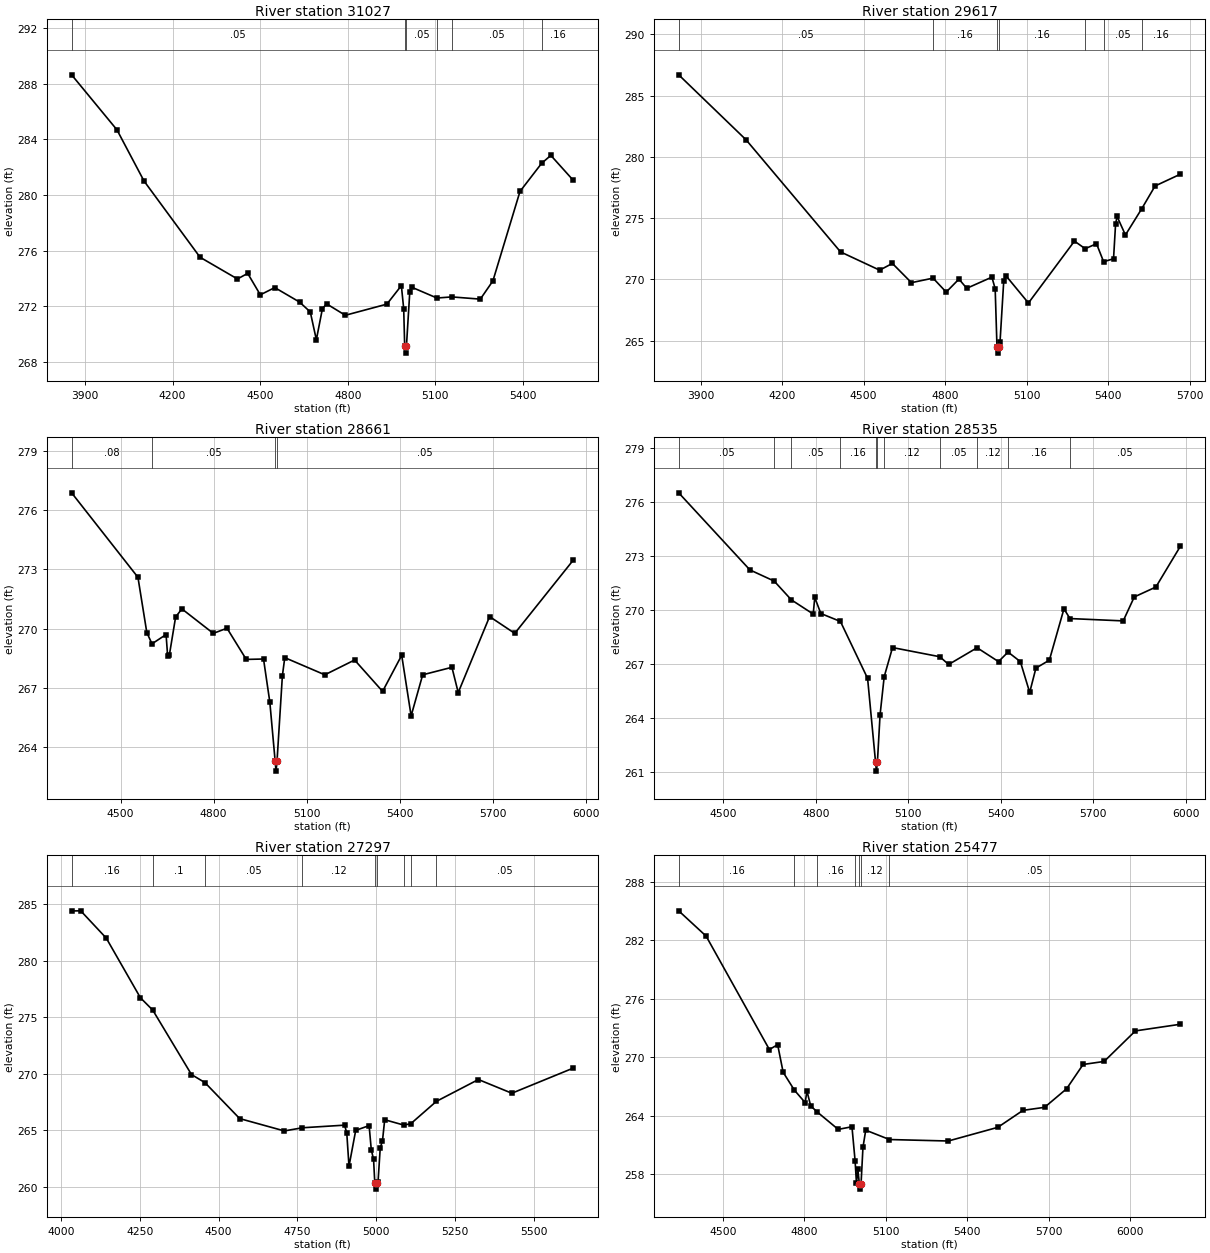
Type RM Length L Ch R = 1 ,31027   ,1410,1410,1410
BEGIN DESCRIPTION:
NEVILLE CREEK 34.0
END DESCRIPTION:
XS GIS Cut Line= 2
       3615182.8     10287603.83      3614106.73     10288943.72
#Sta/Elev= 30
  3854.1  288.64  4009.3  284.69  4102.1  281.01  4294.1  275.53  4422.1  273.97
  4457.3  274.37  4500.5  272.83  4550.1  273.35  4634.9  272.31  4671.7   271.6
  4692.5   269.6  4713.3  271.84  4727.7  272.18  4791.7  271.36  4934.1  272.16
  4983.7  273.49  4991.7  271.84  4995.1  269.14  4997.9  268.64  5001.1  269.14
  5012.5  273.02  5018.9  273.38  5105.6   272.6  5156.7  272.68  5254.2  272.52
  5297.3  273.83  5390.1  280.26  5464.6  282.29  5495.8  282.85  5572.6  281.06
#Mann= 6 ,-1 , 0
  3854.1     .05       0  4995.1     .03       0  5001.1     .05       0
  5105.6     .16       0  5156.7     .05       0  5464.6     .16       0
Bank Sta=4995.1,5001.1
XS Rating Curve= 0 ,0
Exp/Cntr=0.3,0.1

Type RM Length L Ch R = 1 ,29617   ,956,956,956
BEGIN DESCRIPTION:
NEVILLE CREEK 31.0
END DESCRIPTION:
XS GIS Cut Line= 3
      3615009.19      10287485.8      3614620.28     10287458.02
        3613287.     10288041.34
#Sta/Elev= 30
  3819.7   286.7  4067.4   281.4    4415  272.25  4558.9  270.76  4605.7  271.31
  4675.8  269.74  4755.4  270.11  4803.7  268.97  4850.5  270.03  4879.3  269.28
  4971.7  270.19  4983.8  269.25  4990.5  264.49  4993.3  263.99  4996.5  264.49
  5001.7  264.91  5015.3  269.87  5025.1  270.26  5106.2  268.08  5275.4  273.13
    5315  272.51  5356.5  272.92  5382.7  271.45  5419.2  271.69  5426.6  274.49
  5432.1  275.15  5462.9  273.63  5522.3  275.75    5572  277.63  5664.9  278.59
#Mann= 7 ,-1 , 0
  3819.7     .05       0  4755.4     .16       0  4990.5     .03       0
  4996.5     .16       0    5315     .16       0  5382.7     .05       0
  5522.3     .16       0
Bank Sta=4990.5,4996.5
XS Rating Curve= 0 ,0
Exp/Cntr=0.3,0.1

Type RM Length L Ch R = 1 ,28661   ,126,126,126
BEGIN DESCRIPTION:
Mapping XS 66f7ec13
END DESCRIPTION:
XS GIS Cut Line= 2
       3614613.3     10287037.89      3613015.72     10287292.88
#Sta/Elev= 30
  4341.9  276.88  4555.8   272.6  4584.4   269.8  4601.1  269.23  4646.5   269.7
  4651.6  268.61    4657  268.65  4677.3  270.59  4697.5     271  4798.8  269.76
    4843  270.02  4905.1  268.44  4960.8  268.46  4981.1  266.28  4998.3  263.28
  5001.1  262.78  5004.3  263.28  5021.6  267.61  5029.3  268.53  5158.5  267.66
  5254.5  268.41  5344.8  266.82  5406.4  268.65  5436.8  265.58  5474.1  267.66
  5568.4  268.04  5588.7  266.76  5689.9  270.61    5771  269.76  5959.7  273.47
#Mann= 4 ,-1 , 0
  4341.9     .08       0  4601.1     .05       0  4998.3     .04       0
  5004.3     .05       0
Bank Sta=4998.3,5004.3
XS Rating Curve= 0 ,0
Exp/Cntr=0.3,0.1

Type RM Length L Ch R = 1 ,28535   ,1238,1238,1238
BEGIN DESCRIPTION:
NEVILLE CREEK 30.0
END DESCRIPTION:
XS GIS Cut Line= 2
      3614608.11     10286933.72      3612998.79     10287168.09
#Sta/Elev= 30
  4355.6   276.5  4586.5  272.22  4665.2   271.6  4720.7  270.56  4791.7  269.77
  4796.7  270.69  4816.4   269.8  4879.9  269.36    4968   266.2  4993.8  261.55
  4996.6  261.05  4999.8  261.55  5008.4  264.17  5021.8  266.29  5048.8  267.91
  5202.3   267.4  5230.7  266.97    5323   267.9  5392.4  267.13  5423.3  267.66
  5463.2  267.13  5493.5  265.42  5513.7  266.77  5557.3  267.21  5604.6  270.06
  5624.1  269.52  5796.7  269.39  5832.6  270.72  5902.6  271.27  5981.9  273.53
#Mann= 11 ,-1 , 0
  4355.6     .05       0  4665.2     .08       0  4720.7     .05       0
  4879.9     .16       0  4993.8     .07       0  4999.8     .16       0
  5021.8     .12       0  5202.3     .05       0    5323     .12       0
  5423.3     .16       0  5624.1     .05       0
Bank Sta=4993.8,4999.8
XS Rating Curve= 0 ,0
Exp/Cntr=0.3,0.1

Type RM Length L Ch R = 1 ,27297   ,1820,1820,1820
BEGIN DESCRIPTION:
NEVILLE CREEK 29.0
END DESCRIPTION:
XS GIS Cut Line= 3
      3614109.66     10285900.94      3613686.47     10286139.66
      3612916.58     10286931.24
#Sta/Elev= 30
  4034.3  284.38  4063.2  284.39  4144.1  281.98  4252.4  276.71  4291.5  275.62
  4414.2  269.93  4456.8  269.22    4567  266.04  4708.5  264.95  4766.1  265.23
  4899.6  265.46  4906.5  264.75  4913.5  261.83  4934.8     265  4977.3  265.42
  4984.2  263.28  4991.4  262.44  4995.4  260.31  4998.1  259.81  5001.4  260.31
  5005.6  260.45  5012.5  263.44  5019.7  264.09  5026.7  265.94  5086.8  265.47
  5109.1  265.58  5190.4  267.56  5323.7  269.49  5429.7  268.28  5624.4   270.5
#Mann= 9 ,-1 , 0
  4034.3     .16       0  4291.5      .1       0  4456.8     .05       0
  4766.1     .12       0  4995.4     .07       0  5001.4     .12       0
  5086.8     .05       0  5109.1     .12       0  5190.4     .05       0
Bank Sta=4995.4,5001.4
XS Rating Curve= 0 ,0
Exp/Cntr=0.3,0.1

Type RM Length L Ch R = 1 ,25477   ,1269,1269,1269
BEGIN DESCRIPTION:
NEVILLE CREEK 26.0
END DESCRIPTION:
XS GIS Cut Line= 2
      3612775.01     10285022.06       3612471.2     10286844.92
#Sta/Elev= 30
  4337.3     285  4438.3  282.41  4671.4  270.79  4701.8  271.29  4722.1  268.46
  4763.5  266.63  4803.2  265.35  4809.7  266.54  4823.5  265.02  4847.8  264.39
  4924.9  262.61  4975.6  262.88  4987.2  259.37  4992.2  257.07  4997.3  258.51
    5003  256.99  5005.7  256.49    5009  256.99  5016.1  260.76  5026.3  262.53
  5113.8  261.57  5330.4  261.42  5512.9  262.82  5605.6  264.56  5685.2  264.87
  5766.3  266.77  5827.1  269.26  5904.6  269.57  6019.8   272.7  6185.3  273.38
#Mann= 7 ,-1 , 0
  4337.3     .16       0  4763.5      .1       0  4847.8     .16       0
  4987.2     .12       0    5003     .07       0    5009     .12       0
  5113.8     .05       0
Bank Sta=5003,5009
XS Rating Curve= 0 ,0
Exp/Cntr=0.3,0.1

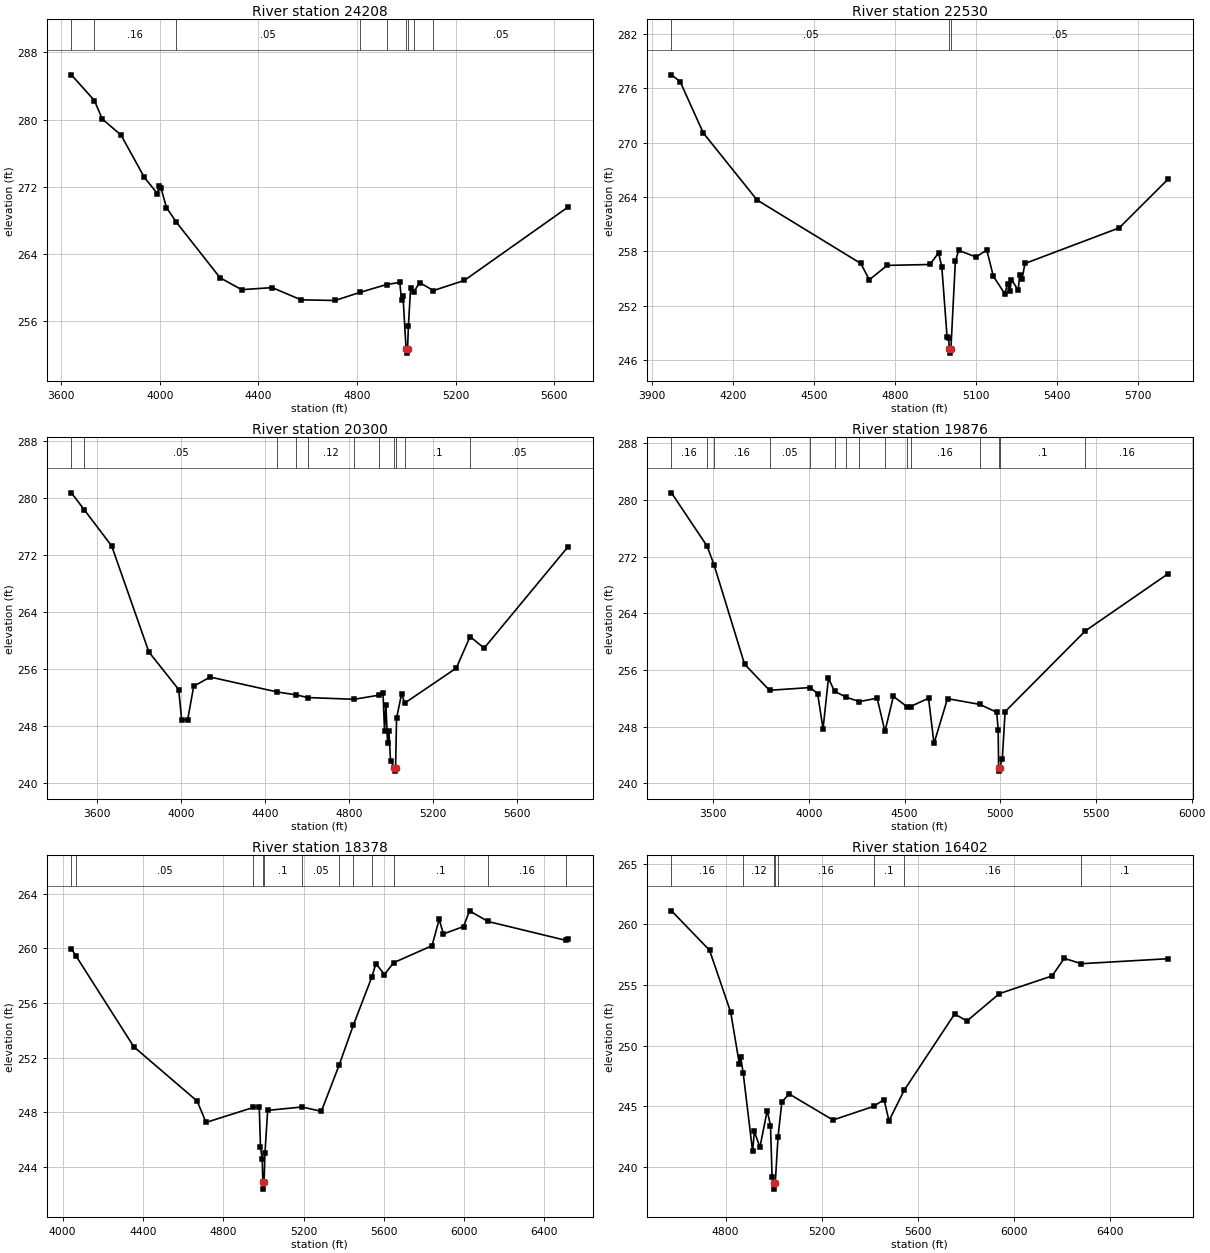
Type RM Length L Ch R = 1 ,24208   ,1678,1678,1678
BEGIN DESCRIPTION:
NEVILLE CREEK 24.0
END DESCRIPTION:
XS GIS Cut Line= 3
      3612471.21     10284750.77      3612178.22     10284902.69
      3611310.18      10286345.8
#Sta/Elev= 30
    3641  285.33  3734.7  282.27    3766  280.09  3842.8  278.15  3937.3  273.12
    3990  271.21  3995.8  272.12  4004.8  271.85  4026.9  269.55  4066.5  267.82
  4244.4  261.19  4331.6  259.78  4456.2  260.02  4572.7  258.57  4710.6  258.49
  4813.4  259.47    4920  260.39  4973.4  260.64  4980.6  258.53  4986.5  259.02
    4999  252.73  5001.8  252.23    5005  252.73  5008.4  255.47  5017.5  260.01
  5029.3  259.49  5054.5  260.62  5109.7  259.67  5235.1  260.87  5655.1  269.58
#Mann= 9 ,-1 , 0
    3641      .1       0  3734.7     .16       0  4066.5     .05       0
  4813.4      .1       0    4920     .05       0    4999     .03       0
    5005     .05       0  5029.3      .1       0  5109.7     .05       0
Bank Sta=4999,5005
XS Rating Curve= 0 ,0
Exp/Cntr=0.3,0.1

Type RM Length L Ch R = 1 ,22530   ,2230,2230,2230
BEGIN DESCRIPTION:
NEVILLE CREEK 22.0
END DESCRIPTION:
XS GIS Cut Line= 3
      3611663.92     10284228.15      3611229.92     10284575.35
      3610785.62     10285778.23
#Sta/Elev= 30
  3973.4  277.51  4005.4  276.76    4091  271.09  4290.3  263.67  4674.5  256.65
  4705.8  254.85    4772  256.44  4930.3  256.54  4962.3  257.82  4974.3  256.26
    4994  248.47  4999.4  248.45    5002  247.24  5004.7  246.74    5008  247.24
  5024.5   256.9  5036.9   258.1  5100.9  257.37  5140.8  258.15  5164.9  255.26
  5207.5   253.3  5218.2   254.4  5226.7  253.64  5232.1  254.87  5257.2  253.71
  5262.5  255.36  5271.5  254.95  5282.1  256.65  5631.3  260.59  5811.5  265.96
#Mann= 3 ,-1 , 0
  3973.4     .05       0    5002     .03       0    5008     .05       0
Bank Sta=5002,5008
XS Rating Curve= 0 ,0
Exp/Cntr=0.3,0.1

Type RM Length L Ch R = 1 ,20300   ,424,424,424
BEGIN DESCRIPTION:
NEVILLE CREEK 19.0
END DESCRIPTION:
XS GIS Cut Line= 3
      3610242.11     10283491.64      3609242.11     10284691.64
      3609192.11     10285491.63
#Sta/Elev= 30
  3477.6  280.69  3538.1  278.35  3669.6  273.24  3846.6  258.39  3988.5  253.12
  4002.8  248.86  4031.5   248.9  4060.1  253.58  4138.2  254.87  4457.1  252.78
  4549.2  252.36  4603.4  251.99  4824.5  251.75  4944.4  252.34  4961.5  252.58
  4968.7  247.36  4975.2  250.94    4983  245.69  4989.5  247.25  4997.3  243.11
  5015.2  242.18  5017.9  241.68  5021.2  242.18    5026   249.1  5049.7  252.49
  5065.4  251.23  5310.2  256.12    5376  260.54  5442.9  258.92  5841.2  273.09
#Mann= 11 ,-1 , 0
  3477.6     .16       0  3538.1     .05       0  4457.1     .12       0
  4549.2     .05       0  4603.4     .12       0  4824.5      .1       0
  4944.4     .12       0  5015.2     .07       0  5021.2     .12       0
  5065.4      .1       0    5376     .05       0
Bank Sta=5015.2,5021.2
XS Rating Curve= 0 ,0
Exp/Cntr=0.3,0.1

Type RM Length L Ch R = 1 ,19876   ,1498,1498,1498
BEGIN DESCRIPTION:
NEVILLE CREEK 18.0
END DESCRIPTION:
XS GIS Cut Line= 3
      3610092.13     10283341.62      3608892.11     10284541.64
      3608593.66     10285387.87
#Sta/Elev= 30
  3281.5  281.03  3467.5   273.5  3503.8  270.87  3663.4  256.82  3793.8  253.13
    4006  253.52  4045.2  252.66  4073.5  247.68  4101.8  254.82  4133.6     253
  4194.7  252.15  4263.4  251.54  4356.3  252.01  4397.1  247.33  4441.2  252.27
  4514.6  250.77  4530.7  250.84    4625  252.01  4653.3  245.62    4724  251.95
  4892.1  251.14  4981.2  250.03  4988.8  247.58  4991.1  242.21  4993.8  241.71
  4997.1  242.21  5010.4  243.47    5025  250.11  5444.1  261.52  5875.9  269.58
#Mann= 15 ,-1 , 0
  3281.5     .16       0  3467.5     .05       0  3503.8     .16       0
  3793.8     .05       0    4006     .16       0  4133.6     .05       0
  4194.7     .16       0  4263.4     .12       0  4397.1     .16       0
  4514.6     .05       0  4530.7     .16       0  4892.1      .1       0
  4991.1     .07       0  4997.1      .1       0  5444.1     .16       0
Bank Sta=4991.1,4997.1
XS Rating Curve= 0 ,0
Exp/Cntr=0.3,0.1

Type RM Length L Ch R = 1 ,18378   ,1976,1976,1976
BEGIN DESCRIPTION:
NEVILLE CREEK 15.0
END DESCRIPTION:
XS GIS Cut Line= 3
      3609331.07     10283067.09      3608235.13      10283837.5
      3607574.38     10284758.22
#Sta/Elev= 30
  4043.3  259.97  4065.5  259.47  4354.6   252.8    4670  248.83  4714.3  247.27
  4950.5  248.37  4979.3  248.39  4985.4  245.46  4994.1   244.6  4997.2  242.89
    5000  242.39  5003.2  242.89  5007.7  245.03  5021.2  248.15  5192.1   248.4
  5288.6  248.08  5376.8  251.45  5448.3   254.4  5539.9   257.9  5560.3  258.89
    5603  258.09    5648  258.95    5840   260.2  5875.6  262.13  5896.5  261.06
  5997.1   261.6  6026.6  262.75  6118.8  261.97  6506.6  260.59  6516.2  260.66
#Mann= 12 ,-1 , 0
  4043.3     .16       0  4065.5     .05       0  4950.5      .1       0
  4997.2     .07       0  5003.2      .1       0  5192.1     .05       0
  5376.8      .1       0  5448.3     .05       0  5539.9     .16       0
    5648      .1       0  6118.8     .16       0  6506.6      .1       0
Bank Sta=4997.2,5003.2
XS Rating Curve= 0 ,0
Exp/Cntr=0.3,0.1

Type RM Length L Ch R = 1 ,16402   ,1862,1862,1862
BEGIN DESCRIPTION:
NEVILLE CREEK 11.0
END DESCRIPTION:
XS GIS Cut Line= 2
      3607681.74     10282318.42      3607356.36     10284357.52
#Sta/Elev= 30
  4575.3  261.12  4733.6  257.87  4821.6  252.76  4857.8  248.47  4862.9  249.07
  4873.3  247.78  4912.7  241.28  4919.9  242.93  4943.1  241.62  4973.5  244.65
  4987.1   243.4  4993.7   239.2  5000.9  238.67  5003.6  238.17  5006.9  238.67
  5018.5  242.48  5034.3  245.35  5064.6  246.02  5246.9  243.87  5416.7     245
  5459.6  245.56  5479.8   243.8  5543.1  246.32  5753.2  252.62  5803.9  252.03
    5939  254.29  6158.3  255.75  6208.9   257.2  6280.1  256.76  6640.2  257.17
#Mann= 8 ,-1 , 0
  4575.3     .16       0  4873.3     .12       0  5000.9     .07       0
  5006.9     .12       0  5018.5     .16       0  5416.7      .1       0
  5543.1     .16       0  6280.1      .1       0
Bank Sta=5000.9,5006.9
XS Rating Curve= 0 ,0
Exp/Cntr=0.3,0.1

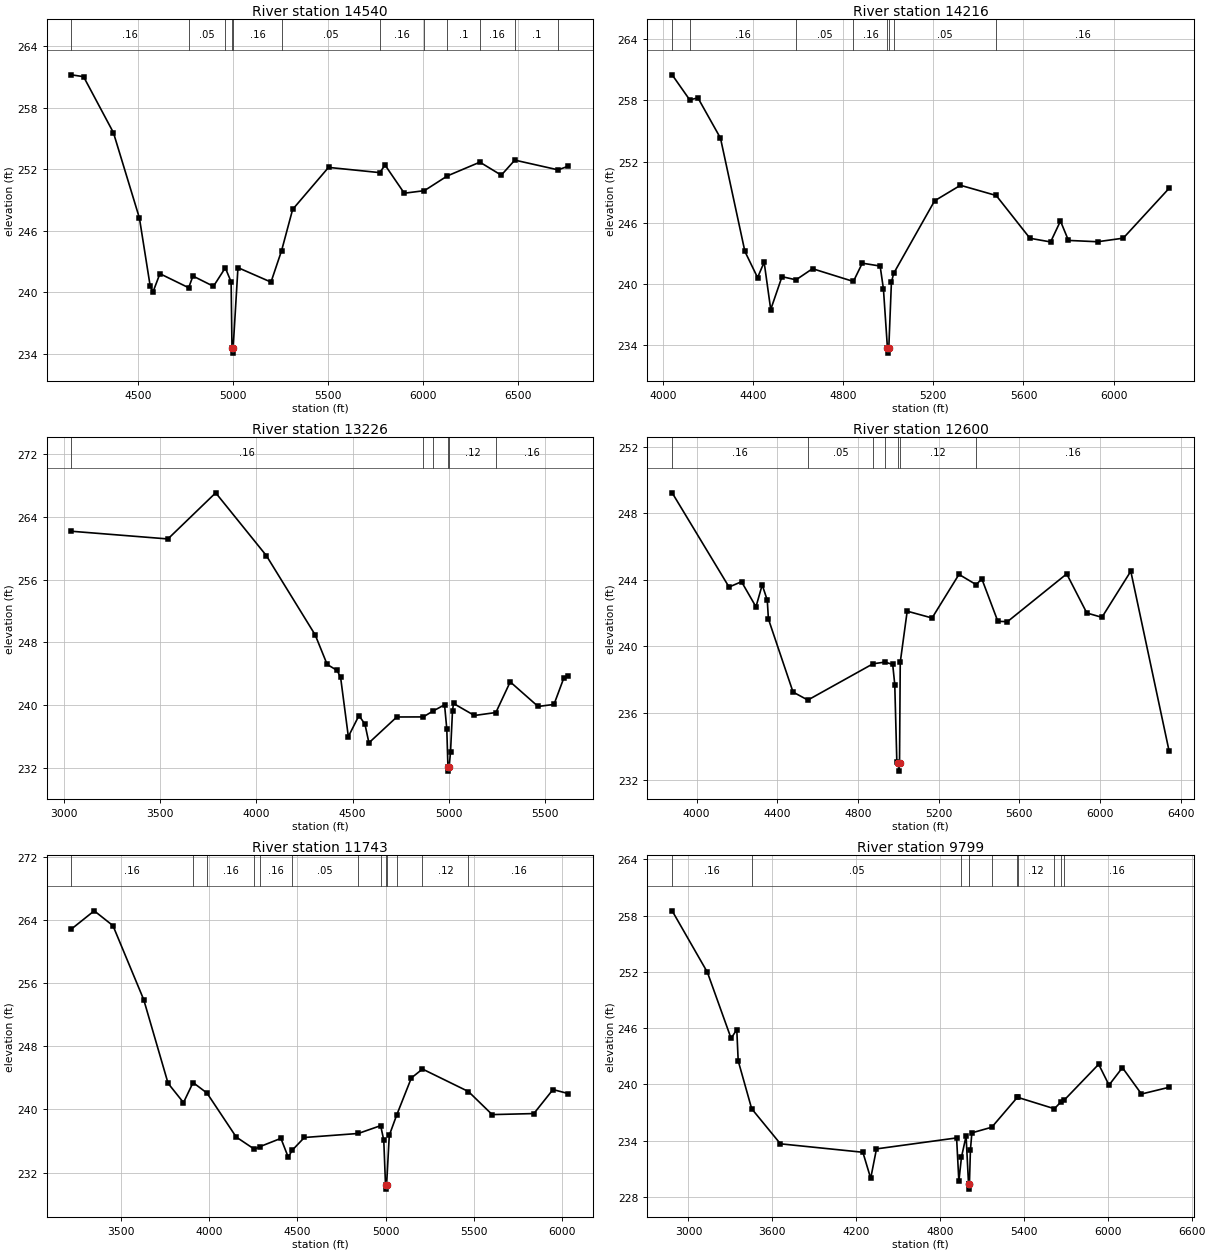
Type RM Length L Ch R = 1 ,14540   ,324,324,324
BEGIN DESCRIPTION:
NEVILLE CREEK 9.0
END DESCRIPTION:
XS GIS Cut Line= 3
      3607245.53     10281797.58       3606086.7     10282578.82
      3605709.25     10283737.19
#Sta/Elev= 30
  4147.7   261.2  4211.8  261.02  4368.9  255.56  4505.7  247.23  4562.7  240.56
  4577.7  240.04  4613.6   241.8  4764.9  240.43  4787.5  241.57  4895.5  240.57
  4957.8  242.37  4988.4     241    4993  234.55  4995.8  234.05    4999  234.55
  5024.4  242.39  5198.3  240.98  5254.2  244.06  5312.2  248.07  5501.1  252.17
  5770.3  251.66  5798.8  252.39  5899.8  249.65  6005.6   249.9  6126.6  251.34
  6297.7  252.68  6410.4  251.41  6481.5  252.88  6709.2  251.93  6763.6  252.29
#Mann= 12 ,-1 , 0
  4147.7     .16       0  4764.9     .05       0  4957.8     .16       0
    4993     .07       0    4999     .16       0  5254.2     .05       0
  5770.3     .16       0  6005.6     .05       0  6126.6      .1       0
  6297.7     .16       0  6481.5      .1       0  6709.2     .16       0
Bank Sta=4993,4999
XS Rating Curve= 0 ,0
Exp/Cntr=0.3,0.1

Type RM Length L Ch R = 1 ,14216   ,990,990,990
BEGIN DESCRIPTION:
Mapping XS c76d39e0
END DESCRIPTION:
XS GIS Cut Line= 2
      3607023.09     10281631.39      3605259.17     10282954.33
#Sta/Elev= 30
  4041.3  260.49  4119.1  258.04  4155.7  258.23  4255.7  254.29    4364  243.19
  4420.3  240.63  4449.4  242.14  4478.6   237.5  4528.6  240.72  4590.8  240.41
    4664   241.5  4845.3  240.25  4884.8  242.04    4964  241.76  4978.6  239.52
  4996.4  233.73  4999.2  233.23  5002.4  233.73    5014  240.16    5024  241.04
  5205.7  248.15  5320.3  249.67  5478.9  248.67  5628.6  244.48  5720.3  244.12
    5764  246.17  5799.4  244.27  5928.6  244.14  6042.5  244.49  6246.2  249.38
#Mann= 8 ,-1 , 0
  4041.3      .1       0  4119.1     .16       0  4590.8     .05       0
  4845.3     .16       0  4996.4     .07       0  5002.4     .16       0
    5024     .05       0  5478.9     .16       0
Bank Sta=4996.4,5002.4
XS Rating Curve= 0 ,0
Exp/Cntr=0.3,0.1

Type RM Length L Ch R = 1 ,13226   ,626,626,626
BEGIN DESCRIPTION:
NEVILLE CREEK 8.0
END DESCRIPTION:
XS GIS Cut Line= 2
      3607807.12     10280896.49      3605309.76     10281560.01
#Sta/Elev= 30
  3037.6  262.15  3539.4  261.17  3787.8  267.04  4051.2  259.05  4305.1  248.96
  4367.3   245.2  4418.9  244.44  4437.3  243.55  4477.5  236.01  4532.7  238.69
  4563.8   237.6  4584.5  235.22  4729.3  238.51    4867  238.52  4918.6  239.28
  4977.7  240.06  4989.3  237.01  4995.4  232.12  4998.1  231.62  5001.4  232.12
  5008.7  234.03  5019.1  239.32  5024.3  240.23  5132.9   238.7  5244.6  239.08
  5319.1  242.98    5464  239.85  5546.7  240.11  5598.5  243.52  5621.6  243.78
#Mann= 6 ,-1 , 0
  3037.6     .16       0    4867     .05       0  4918.6     .12       0
  4995.4     .07       0  5001.4     .12       0  5244.6     .16       0
Bank Sta=4995.4,5001.4
XS Rating Curve= 0 ,0
Exp/Cntr=0.3,0.1

Type RM Length L Ch R = 1 ,12600   ,857,857,857
BEGIN DESCRIPTION:
Mapping XS 7b8686c1
END DESCRIPTION:
XS GIS Cut Line= 2
      3606866.76     10280589.76      3604467.52     10281148.77
#Sta/Elev= 30
  3878.9  249.23  4160.9  243.57  4222.7  243.89  4294.4  242.38  4325.2   243.7
  4350.4  242.78    4356  241.65  4478.1  237.26  4551.5  236.78  4874.6  238.96
    4934  239.06  4972.1  238.92  4982.3  237.71  4992.6  233.07  4999.9  233.01
  5002.6  232.51  5005.9  233.01  5009.5  239.05  5043.9  242.12  5167.2  241.71
  5300.6  244.33  5386.3  243.71  5413.6  244.07  5493.2  241.51  5540.9  241.49
  5834.6  244.36  5934.3  242.01  6009.1  241.75  6152.2  244.52  6342.4   233.7
#Mann= 7 ,-1 , 0
  3878.9     .16       0  4551.5     .05       0  4874.6     .16       0
    4934     .12       0  4999.9     .07       0  5005.9     .12       0
  5386.3     .16       0
Bank Sta=4999.9,5005.9
XS Rating Curve= 0 ,0
Exp/Cntr=0.3,0.1

Type RM Length L Ch R = 1 ,11743   ,1944,1944,1944
BEGIN DESCRIPTION:
NEVILLE CREEK 7.0
END DESCRIPTION:
XS GIS Cut Line= 4
      3607312.21     10280104.02      3607051.83     10279878.36
      3604953.91     10280499.34      3604813.61     10280751.36
#Sta/Elev= 30
  3216.7  262.84  3346.3  265.15  3452.7  263.27  3627.2   253.9  3765.5   243.3
    3853  240.86  3907.3   243.4  3986.2  242.07  4152.2   236.5  4255.8  234.95
  4284.4  235.26  4405.9  236.33  4447.4  233.95  4470.7  234.84  4538.9  236.44
  4845.1  236.95    4972  237.94  4989.7   236.1  4999.6   230.4  5002.3   229.9
  5005.6   230.4    5021  236.71  5062.1  239.23  5146.2  243.98  5209.4  245.11
  5470.3  242.26    5605  239.34  5841.5  239.47  5950.1  242.51  6037.6     242
#Mann= 13 ,-1 , 0
  3216.7     .16       0  3907.3     .05       0  3986.2     .16       0
  4255.8     .05       0  4284.4     .16       0  4470.7     .05       0
  4845.1     .16       0    4972     .12       0  4999.6     .07       0
  5005.6     .12       0  5062.1     .16       0  5209.4     .12       0
  5470.3     .16       0
Bank Sta=4999.6,5005.6
XS Rating Curve= 0 ,0
Exp/Cntr=0.3,0.1

Type RM Length L Ch R = 1 ,9799    ,2845,2845,2845
BEGIN DESCRIPTION:
NEVILLE CREEK 1.0
END DESCRIPTION:
XS GIS Cut Line= 4
       3607763.6     10278940.86      3607190.72     10278975.58
      3604812.25     10279600.58      3604673.37     10280104.02
#Sta/Elev= 30
  2883.6  258.51  3135.6  251.96  3305.3  244.91  3345.9  245.85    3356  242.52
  3452.5  237.41  3658.1  233.67  4247.9  232.77  4303.9  229.99  4345.3  233.13
  4918.4   234.3  4934.6  229.68  4953.2  232.24  4986.3   234.5    5004  229.34
  5006.8  228.84    5010  229.34  5017.4  233.04  5027.7  234.84  5170.1  235.44
  5352.7  238.62  5354.3  238.63  5618.1  237.41  5662.2   238.1  5689.5  238.35
  5934.8  242.15  6008.7  239.93  6104.6  241.79  6240.8  238.98    6439   239.7
#Mann= 11 ,-1 , 0
  2883.6     .16       0  3452.5     .05       0  4953.2     .16       0
    5004     .07       0    5010     .16       0  5170.1     .05       0
  5352.7     .16       0  5354.3     .12       0  5618.1     .16       0
  5662.2     .12       0  5689.5     .16       0
Bank Sta=5004,5010
XS Rating Curve= 0 ,0
Exp/Cntr=0.3,0.1

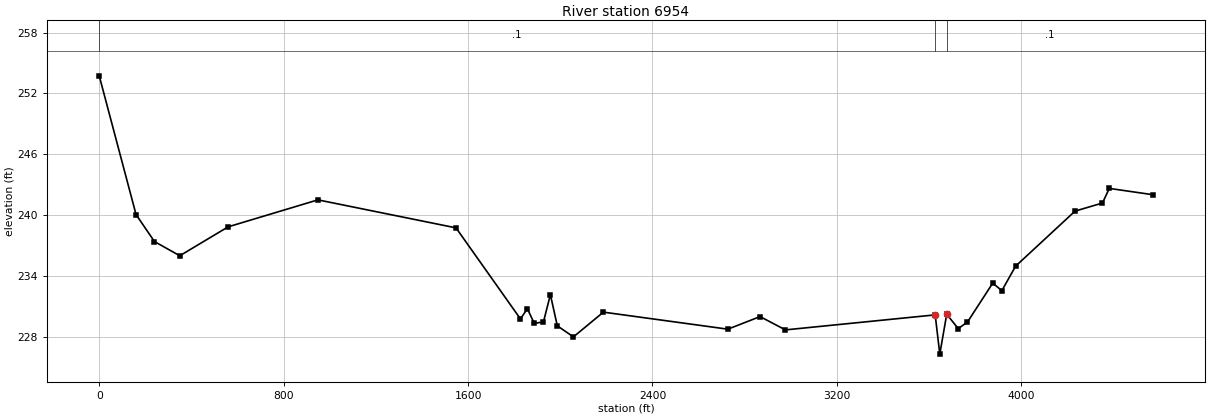
Type RM Length L Ch R = 1 ,6954    ,0,0,0
XS GIS Cut Line= 4
      3607726.67      10278560.5     3605816.948    10278074.389
     3604316.948    10279209.806     3603896.809    10279834.806
#Sta/Elev= 30
       0  253.73  159.77  240.05  239.65  237.39  349.49  235.99  559.19  238.84
  948.63   241.5 1547.76  238.74 1827.35  229.76 1857.31  230.77 1887.26  229.32
 1927.21  229.47 1957.16  232.16 1987.15  229.08 2057.12  227.99 2187.06  230.43
 2726.83  228.75 2866.76  229.99 2976.72  228.68 3626.43  230.16 3646.42  226.29
 3676.41  230.22 3726.39  228.81 3766.37  229.45    3876  233.29 3915.67  232.55
 3975.17  234.96    4233  240.39    4352  241.19 4381.75  242.63 4570.16  242.01
#Mann= 3 , 0 , 0
       0      .1       0 3626.43     .05       0 3676.41      .1       0
Bank Sta=3626.43,3676.41
XS Rating Curve= 0 ,0
Exp/Cntr=0.3,0.1

Chan Stop Cuts=-1
Use User Specified Reach Order=0
Composite Channel Slope=5