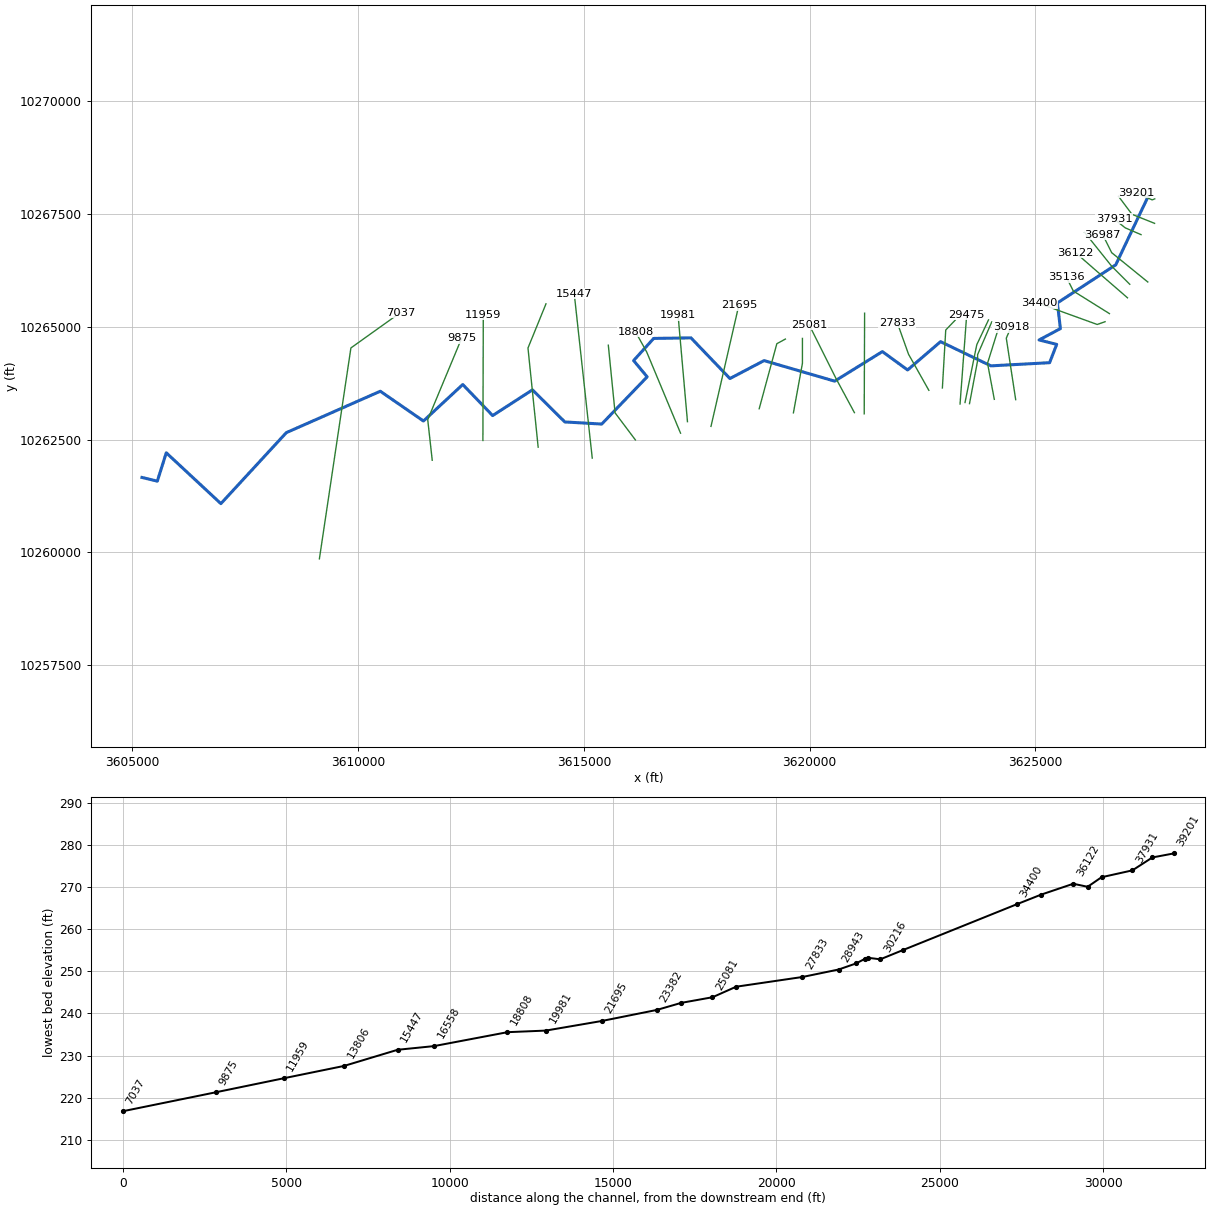
--- RAGAN CREEK.prj (project) ---

Proj Title=RAGAN CREEK Base Level Engineering
Current Plan=p01
Default Exp/Contr=0.3,0.1
English Units
Geom File=g01
Flow File=f01
Plan File=p01
Y Axis Title=Elevation
X Axis Title(PF)=Main Channel Distance
X Axis Title(XS)=Station
BEGIN DESCRIPTION:
RAGAN CREEK
END DESCRIPTION:
DSS Export Rating Curves= 0
DSS Export Rating Curve Sorted= 0
DSS Export Volume Flow Curves= 0
DXF OffsetX= 0
DXF OffsetY= 0
DXF ScaleX= 1
DXF ScaleY= 10

--- RAGAN CREEK.p01 (plan) ---

Plan Title=Multiple Run
Short Identifier=Multiple
Geom File=g01
Flow File=f01
Subcritical Flow
K Sum by GR= 0
Std Step Tol= 0.01
Critical Tol= 0.01
Num of Std Step Trials= 20
Max Error Tol= 0.3
Flow Tol Ratio= 0.001
Split Flow NTrial= 30
Split Flow Tol= 0.02
Split Flow Ratio= 0.02
Log Output Level= 0
Friction Slope Method= 1
Unsteady Friction Slope Method= 2
Unsteady Bridges Friction Slope Method= 1
Parabolic Critical Depth
Global Vel Dist=  1 , 1 , 1
Global Log Level= 0
CheckData=True
Encroach Param= -1, 0, 0, 0
BEGIN DESCRIPTION:
Multiple Run
END DESCRIPTION:

--- RAGAN CREEK.f01 (steady flow) ---

Flow Title=Multiple
Program Version=4.10
Number of Profiles= 7
Profile Names=10-year,25-year,50-year,1pct_min,100-year,1pct_plu,500-year
River Rch & RM=RAGAN CREEK,Reach-1         ,39201
     828    1127    1373    1225    1657    2241    2417
River Rch & RM=RAGAN CREEK,Reach-1         ,30918
    1400    1957    2426    2199    2974    4022    4477
River Rch & RM=RAGAN CREEK,Reach-1         ,27833
    1613    2267    2821    2565    3469    4692    5258
River Rch & RM=RAGAN CREEK,Reach-1         ,25805
    1672    2345    2915    2645    3577    4837    5401
River Rch & RM=RAGAN CREEK,Reach-1         ,21695
    1817    2549    3167    2871    3883    5252    5852
River Rch & RM=RAGAN CREEK,Reach-1         ,13806
    1961    2759    3434    3118    4217    5703    6376
River Rch & RM=RAGAN CREEK,Reach-1         ,7037
    2048    2879    3582    3250    4396    5945    6636
Boundary for River Rch & Prof#=RAGAN CREEK,Reach-1         , 1
Up Type= 0
Dn Type= 3
Dn Slope=0.00208
Boundary for River Rch & Prof#=RAGAN CREEK,Reach-1         , 2
Up Type= 0
Dn Type= 3
Dn Slope=0.00208
Boundary for River Rch & Prof#=RAGAN CREEK,Reach-1         , 3
Up Type= 0
Dn Type= 3
Dn Slope=0.00208
Boundary for River Rch & Prof#=RAGAN CREEK,Reach-1         , 4
Up Type= 0
Dn Type= 3
Dn Slope=0.00208
Boundary for River Rch & Prof#=RAGAN CREEK,Reach-1         , 5
Up Type= 0
Dn Type= 3
Dn Slope=0.00208
Boundary for River Rch & Prof#=RAGAN CREEK,Reach-1         , 6
Up Type= 0
Dn Type= 3
Dn Slope=0.00208
Boundary for River Rch & Prof#=RAGAN CREEK,Reach-1         , 7
Up Type= 0
Dn Type= 3
Dn Slope=0.00208
DSS Import GetInterval= 0
DSS Import GetPeak= 0
DSS Import FillOption= 0

--- RAGAN CREEK.g01 (geometry) ---

Geom Title=Existing Conditions
Program Version=4.10

River Reach=RAGAN CREEK     ,Reach-1
Reach XY= 30
      3627501.43     10267890.62      3626781.67     10266372.31
      3625489.53     10265528.08      3625556.23     10264958.88
      3625084.53     10264707.12      3625473.93     10264608.94
      3625316.72     10264203.37      3624017.26     10264133.42
      3622901.75     10264669.56      3622171.74     10264042.17
      3621612.55     10264449.63      3620556.57     10263794.34
      3618992.28     10264249.88      3618236.43     10263852.31
      3617373.14     10264753.34       3616547.3     10264741.33
      3616102.54      10264250.9      3616402.37     10263889.64
       3615396.4     10262843.49      3614578.41     10262890.33
      3613862.11     10263601.64      3612980.14     10263031.68
      3612318.22     10263719.81      3611447.12     10262911.39
      3610491.78     10263570.96      3608409.59     10262652.97
      3606960.52     10261080.12      3605750.79     10262206.51
      3605552.72     10261578.76      3605211.66     10261660.44

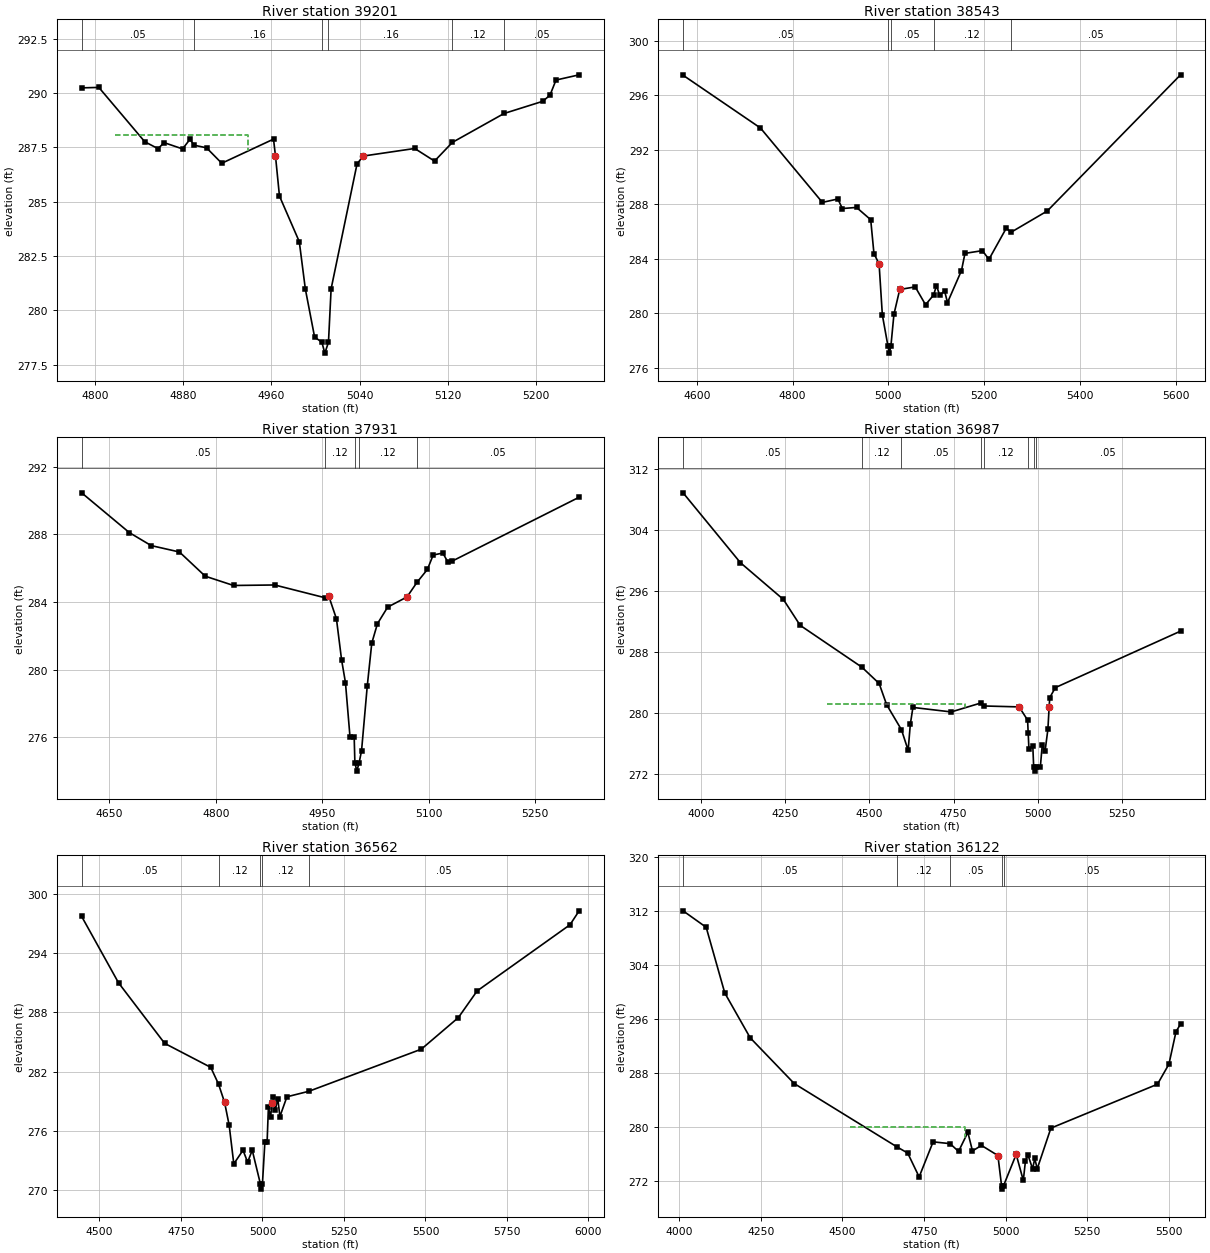
Type RM Length L Ch R = 1 ,39201   ,658,658,658
BEGIN DESCRIPTION:
RAGAN CREEK 47.0
END DESCRIPTION:
XS GIS Cut Line= 3
      3627646.53     10267834.77      3627590.15     10267811.35
      3627231.72      10267966.7
#Sta/Elev= 30
  4787.7  290.24  4803.3  290.26    4845  287.76  4857.1  287.44  4862.5  287.72
  4879.3  287.43    4886  287.87  4889.9   287.6  4901.1  287.48  4914.9  286.77
  4961.9  287.88 4963.67  287.11  4967.3  285.26  4985.3  283.16  4990.8  280.98
  4999.2  278.77  5005.8  278.53  5008.5  278.03  5011.8  278.53  5014.2  280.99
  5037.7  286.73  5043.2   287.1  5090.1  287.45  5108.1  286.87  5124.3  287.73
  5171.2  289.06  5206.3  289.62  5212.9   289.9  5218.4   290.6  5239.4  290.84
#Mann= 6 ,-1 , 0
  4787.7     .05       0  4889.9     .16       0  5005.8     .07       0
  5011.8     .16       0  5124.3     .12       0  5171.2     .05       0
#XS Ineff= 1 ,-1
 4817.61 4938.64  288.06
Permanent Ineff=
       F
Bank Sta=4963.67,5043.2
XS Rating Curve= 0 ,0
Exp/Cntr=0.3,0.1

Type RM Length L Ch R = 1 ,38543   ,612,612,612
BEGIN DESCRIPTION:
RAGAN CREEK 46.0
END DESCRIPTION:
XS GIS Cut Line= 3
      3627642.06     10267291.66      3627142.11     10267491.64
      3626842.09     10267891.67
#Sta/Elev= 30
  4571.4  297.46  4732.9  293.59  4862.2  288.13  4894.5  288.38  4903.9  287.68
  4933.5  287.76  4963.1  286.86  4969.9  284.37  4980.6  283.62  4987.4  279.87
  4999.2  277.57  5001.9  277.07  5005.2  277.57  5011.6  279.92  5023.7  281.74
    5056  281.93  5077.6  280.62  5094.5  281.34  5100.4  282.03  5107.2   281.3
  5117.2  281.65  5123.4  280.78  5152.6  283.13  5159.9  284.39  5196.3  284.59
  5209.9  283.95  5246.3  286.25  5255.6  285.93  5331.7   287.5  5609.9  297.49
#Mann= 5 ,-1 , 0
  4571.4     .05       0  4999.2     .03       0  5005.2     .05       0
  5094.5     .12       0  5255.6     .05       0
Bank Sta=4980.6,5023.7
XS Rating Curve= 0 ,0
Exp/Cntr=0.3,0.1

Type RM Length L Ch R = 1 ,37931   ,944,944,944
BEGIN DESCRIPTION:
RAGAN CREEK 45.0
END DESCRIPTION:
XS GIS Cut Line= 3
      3627342.11     10267041.64      3626992.11     10267191.64
      3626742.07     10267391.67
#Sta/Elev= 30
  4611.1  290.46  4678.2  288.11    4709  287.34  4748.9  286.96  4785.2  285.53
  4825.1  284.98  4883.1  285.01  4953.5  284.26  4959.3  284.35  4970.1  283.01
  4977.4  280.57  4982.8  279.24  4989.2  276.03  4995.1  276.03  4996.1   274.5
  4998.8     274  5002.1   274.5  5005.5  275.21  5013.5  279.02  5019.9  281.57
  5027.9  282.72  5042.3   283.7  5069.5   284.3  5083.7  285.17  5098.3  285.93
  5106.4  286.78    5120   286.9  5127.2  286.36  5133.6  286.43  5312.1   290.2
#Mann= 5 ,-1 , 0
  4611.1     .05       0  4953.5     .12       0  4996.1     .07       0
  5002.1     .12       0  5083.7     .05       0
Bank Sta=4959.3,5069.5
XS Rating Curve= 0 ,0
Exp/Cntr=0.3,0.1

Type RM Length L Ch R = 1 ,36987   ,425,425,425
BEGIN DESCRIPTION:
RAGAN CREEK 43.0
END DESCRIPTION:
XS GIS Cut Line= 3
      3627492.09     10265991.66      3626692.11     10266641.64
      3626492.09     10267041.67
#Sta/Elev= 30
  3946.5  308.85  4116.7   299.7  4244.6  294.87  4294.4  291.48  4477.9  285.99
    4529  283.86  4551.3  281.08  4595.4  277.79  4615.2   275.1  4621.7  278.53
  4629.4  280.72  4743.1  280.13  4830.4  281.29  4840.5  280.91 4944.97  280.79
  4970.1  279.06  4971.9  277.32    4974   275.3  4985.6  275.63  4988.2  272.87
    4991  272.37  4994.2  272.87    5008  272.93  5013.6  275.78    5022     275
  5030.4  277.84 5034.11  280.79    5036  282.02  5052.7  283.32  5424.5  290.72
#Mann= 8 ,-1 , 0
  3946.5     .05       0  4477.9     .12       0  4595.4     .05       0
  4830.4     .16       0  4840.5     .12       0  4971.9     .05       0
  4988.2     .03       0  4994.2     .05       0
#XS Ineff= 1 ,-1
 4374.77 4782.85281.1089
Permanent Ineff=
       F
Bank Sta=4944.97,5034.11
XS Rating Curve= 0 ,0
Exp/Cntr=0.3,0.1

Type RM Length L Ch R = 1 ,36562   ,440,440,440
BEGIN DESCRIPTION:
RAGAN CREEK 42.0
END DESCRIPTION:
XS GIS Cut Line= 3
       3627092.1     10265941.65      3626692.11     10266341.64
      3626092.14      10267091.6
#Sta/Elev= 30
  4445.4  297.71  4558.5  290.99    4700  284.86  4841.4  282.43  4865.2  280.74
  4883.8  278.89  4897.9  276.57  4912.1  272.66  4940.4  274.04  4954.5  272.83
  4968.7  274.04  4993.9   270.6  4996.7   270.1  4999.9   270.6  5007.5  274.89
  5014.3  274.89  5018.3  278.41  5024.7  277.41 5029.95  278.79  5032.7  279.46
  5039.1  278.09  5047.1  279.25  5053.5  277.45  5075.1  279.45  5142.6  280.01
  5487.3  284.27    5601  287.47  5658.6  290.17  5943.5  296.87  5971.5  298.28
#Mann= 5 ,-1 , 0
  4445.4     .05       0  4865.2     .12       0  4993.9     .07       0
  4999.9     .12       0  5142.6     .05       0
Bank Sta=4883.8,5029.95
XS Rating Curve= 0 ,0
Exp/Cntr=0.3,0.1

Type RM Length L Ch R = 1 ,36122   ,986,986,986
BEGIN DESCRIPTION:
RAGAN CREEK 41.0
END DESCRIPTION:
XS GIS Cut Line= 3
      3627042.11     10265641.64      3626292.11     10266291.64
      3625892.09     10266641.65
#Sta/Elev= 30
  4011.9  312.07  4082.7  309.63  4139.7  299.89  4217.5  293.25  4352.4  286.47
  4667.1  277.08    4700  276.17  4735.1  272.63  4777.9  277.83  4829.9  277.56
  4855.8  276.41  4884.3  279.24  4898.5  276.48    4926   277.3  4976.4   275.8
  4987.6  271.32  4990.4  270.82  4993.6  271.32  5032.4  275.97  5054.2   272.1
  5060.8  275.01  5068.4   275.9  5082.7  273.82  5089.3  275.36  5096.9  273.84
  5138.7  279.86  5465.2  286.37  5500.3  289.34  5522.1  294.18  5535.9  295.27
#Mann= 5 ,-1 , 0
  4011.9     .05       0  4667.1     .12       0  4829.9     .05       0
  4987.6     .03       0  4993.6     .05       0
#XS Ineff= 1 ,-1
 4522.73 4876.36  280.08
Permanent Ineff=
       F
Bank Sta=4976.4,5032.4
XS Rating Curve= 0 ,0
Exp/Cntr=0.3,0.1

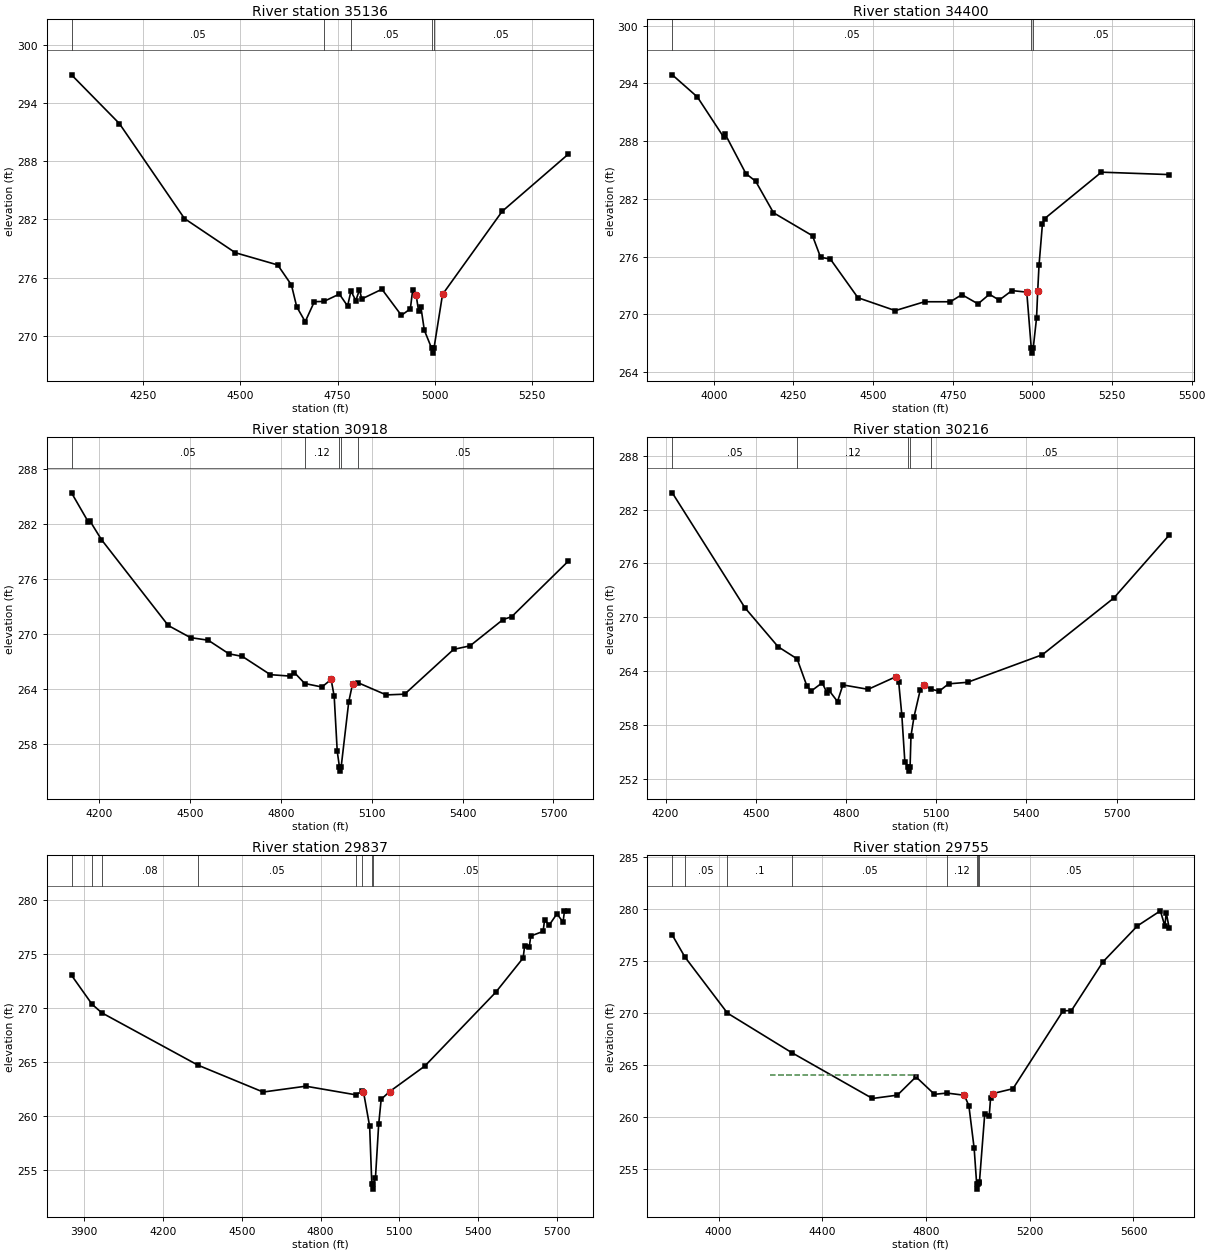
Type RM Length L Ch R = 1 ,35136   ,736,736,736
BEGIN DESCRIPTION:
RAGAN CREEK 39.0
END DESCRIPTION:
XS GIS Cut Line= 3
       3626642.1     10265291.65      3625842.11     10265791.64
       3625692.1     10266091.65
#Sta/Elev= 30
  4065.2  296.89  4188.4  291.87  4355.9  282.09  4486.8  278.57  4595.9  277.31
  4631.2  275.25  4644.8     273  4666.6  271.47  4690.2  273.53  4714.4  273.55
  4754.5  274.31  4775.7  273.08  4784.4  274.63  4796.9  273.63  4806.3  274.77
  4812.2  273.81  4864.1  274.81  4914.2  272.12  4937.2  272.79  4943.1  274.68
 4951.96  274.24  4958.5  272.57  4964.4  272.97  4973.2  270.59    4992  268.73
  4994.8  268.23    4998  268.73 5020.09  274.28  5173.5  282.83    5344  288.73
#Mann= 5 ,-1 , 0
  4065.2     .05       0  4714.4     .12       0  4784.4     .05       0
    4992     .03       0    4998     .05       0
Bank Sta=4951.96,5020.09
XS Rating Curve= 0 ,0
Exp/Cntr=0.3,0.1

Type RM Length L Ch R = 1 ,34400   ,3482,3482,3482
BEGIN DESCRIPTION:
RAGAN CREEK 38.0
END DESCRIPTION:
XS GIS Cut Line= 3
      3626545.05     10265111.34      3626371.43     10265050.57
        3625078.     10265519.33
#Sta/Elev= 30
  3869.7   294.9  3948.4   292.6  4030.9  288.43  4036.2   288.7  4100.8  284.63
  4131.4  283.84  4187.4  280.56  4309.9  278.17  4335.2  275.93  4365.8  275.75
  4452.4  271.73  4569.6  270.39  4661.5  271.31  4742.7  271.31  4778.7  272.05
  4829.3  271.09  4865.2  272.09  4895.9  271.48  4935.8  272.47  4982.4  272.31
  4996.6  266.47  4999.3  265.97  5002.6  266.47  5013.1  269.62 5016.71   272.4
  5020.8  275.08  5031.5  279.36  5038.4  279.95  5216.8  284.78  5429.4  284.53
#Mann= 3 ,-1 , 0
  3869.7     .05       0  4996.6     .03       0  5002.6     .05       0
Bank Sta=4982.4,5016.71
XS Rating Curve= 0 ,0
Exp/Cntr=0.3,0.1

Type RM Length L Ch R = 1 ,30918   ,702,702,702
BEGIN DESCRIPTION:
RAGAN CREEK 35.0
END DESCRIPTION:
XS GIS Cut Line= 3
      3624565.87      10263383.9      3624357.54     10264746.75
      3624461.03     10264988.23
#Sta/Elev= 30
  4107.9  285.36  4163.6  282.18  4168.6  282.31  4206.8  280.27  4427.5  270.93
    4501  269.61  4559.4  269.33  4627.9  267.85  4672.1  267.57  4764.9  265.58
  4828.3  265.43  4844.1  265.81  4878.3  264.62  4935.1  264.24  4965.5  265.06
  4975.6  263.23  4985.7  257.23  4992.8  255.59  4995.6  255.09  4998.8  255.59
  5023.7  262.63  5036.3  264.58  5054.1  264.71  5147.6  263.38  5208.3  263.46
  5370.1  268.33  5424.5  268.72  5533.1  271.57  5562.1  271.89  5749.3  277.94
#Mann= 5 ,-1 , 0
  4107.9     .05       0  4878.3     .12       0  4992.8     .07       0
  4998.8     .12       0  5054.1     .05       0
Bank Sta=4965.5,5036.3
XS Rating Curve= 0 ,0
Exp/Cntr=0.3,0.1

Type RM Length L Ch R = 1 ,30216   ,379,379,379
BEGIN DESCRIPTION:
RAGAN CREEK 33.0
END DESCRIPTION:
XS GIS Cut Line= 3
      3624092.11     10263391.63      3623942.11     10264191.64
       3624192.1     10264991.64
#Sta/Elev= 30
  4222.5  283.86  4464.1  271.06  4574.4  266.72  4637.6  265.37  4670.2  262.34
  4684.6  261.79    4721  262.71  4737.2  261.57  4742.2  261.92  4771.9  260.62
  4789.7  262.47  4873.7  261.98  4965.2  263.37  4975.4  262.74  4985.6  259.16
  4995.8  253.89  5007.2  253.37  5009.9  252.87  5013.2  253.37  5016.1  256.78
  5026.3  258.93  5046.9  261.91  5057.9  262.42    5084  261.99  5109.8  261.77
  5141.2  262.59  5204.1  262.76  5452.9  265.83  5690.7  272.15  5874.6  279.15
#Mann= 5 ,-1 , 0
  4222.5     .05       0  4637.6     .12       0  5007.2     .07       0
  5013.2     .12       0    5084     .05       0
Bank Sta=4965.2,5057.9
XS Rating Curve= 0 ,0
Exp/Cntr=0.3,0.1

Type RM Length L Ch R = 1 ,29837   ,82,82,82
BEGIN DESCRIPTION:
Mapping XS b5784580
END DESCRIPTION:
XS GIS Cut Line= 4
      3623542.72     10263296.05       3623722.4     10264249.17
       3623722.4     10264381.98      3624034.88      10265105.9
#Sta/Elev= 30
    3852  273.02  3930.1  270.34  3967.1  269.55  4332.9  264.71  4581.3  262.22
  4743.7  262.76  4934.4  261.96  4957.1  262.29  4963.2  262.25  4986.7  259.05
  4994.9  253.74  4997.7  253.24  5000.9  253.74  5008.8  254.27  5021.1  259.23
  5030.6  261.55  5062.7  262.26  5196.6  264.62    5466  271.43    5571  274.62
  5576.4   275.7  5594.5  275.66  5599.9  276.65  5646.9  277.08  5652.4  278.11
  5670.4  277.67  5699.4   278.7  5722.9  277.94  5728.3  278.98  5743.2  278.98
#Mann= 8 ,-1 , 0
    3852     .08       0  3930.1     .05       0  3967.1     .08       0
  4332.9     .05       0  4934.4     .12       0  4957.1     .05       0
  4994.9     .04       0  5000.9     .05       0
Bank Sta=4963.2,5062.7
XS Rating Curve= 0 ,0
Exp/Cntr=0.3,0.1

Type RM Length L Ch R = 1 ,29755   ,280,280,280
BEGIN DESCRIPTION:
Mapping XS d475646c
END DESCRIPTION:
XS GIS Cut Line= 3
      3623443.11     10263320.81      3623703.52     10264601.17
      3623963.93     10265152.37
#Sta/Elev= 30
  3821.4  277.46  3870.3  275.34  4034.2  269.95  4282.1  266.15  4593.4  261.74
  4689.5  262.06  4761.1  263.82  4832.5  262.14  4880.8  262.26  4947.6  262.05
  4965.2  261.04  4985.6  256.93  4995.2  253.52  4997.9  253.02  5001.2  253.52
  5002.8  253.59    5006  253.73  5026.4  260.27  5043.7  260.09  5048.8  261.76
    5057  262.21  5135.2  262.68  5328.4  270.17  5360.8   270.2  5482.2  274.88
  5615.1  278.34  5703.7  279.79  5720.9  278.33  5726.4  279.59  5737.6  278.15
#Mann= 8 ,-1 , 0
  3821.4     .16       0  3870.3     .05       0  4034.2      .1       0
  4282.1     .05       0  4880.8     .12       0  4995.2     .07       0
  5001.2     .12       0  5002.8     .05       0
#XS Ineff= 1 ,-1
 4198.86 4761.36  264.01
Permanent Ineff=
       F
Bank Sta=4947.6,5057
XS Rating Curve= 0 ,0
Exp/Cntr=0.3,0.1

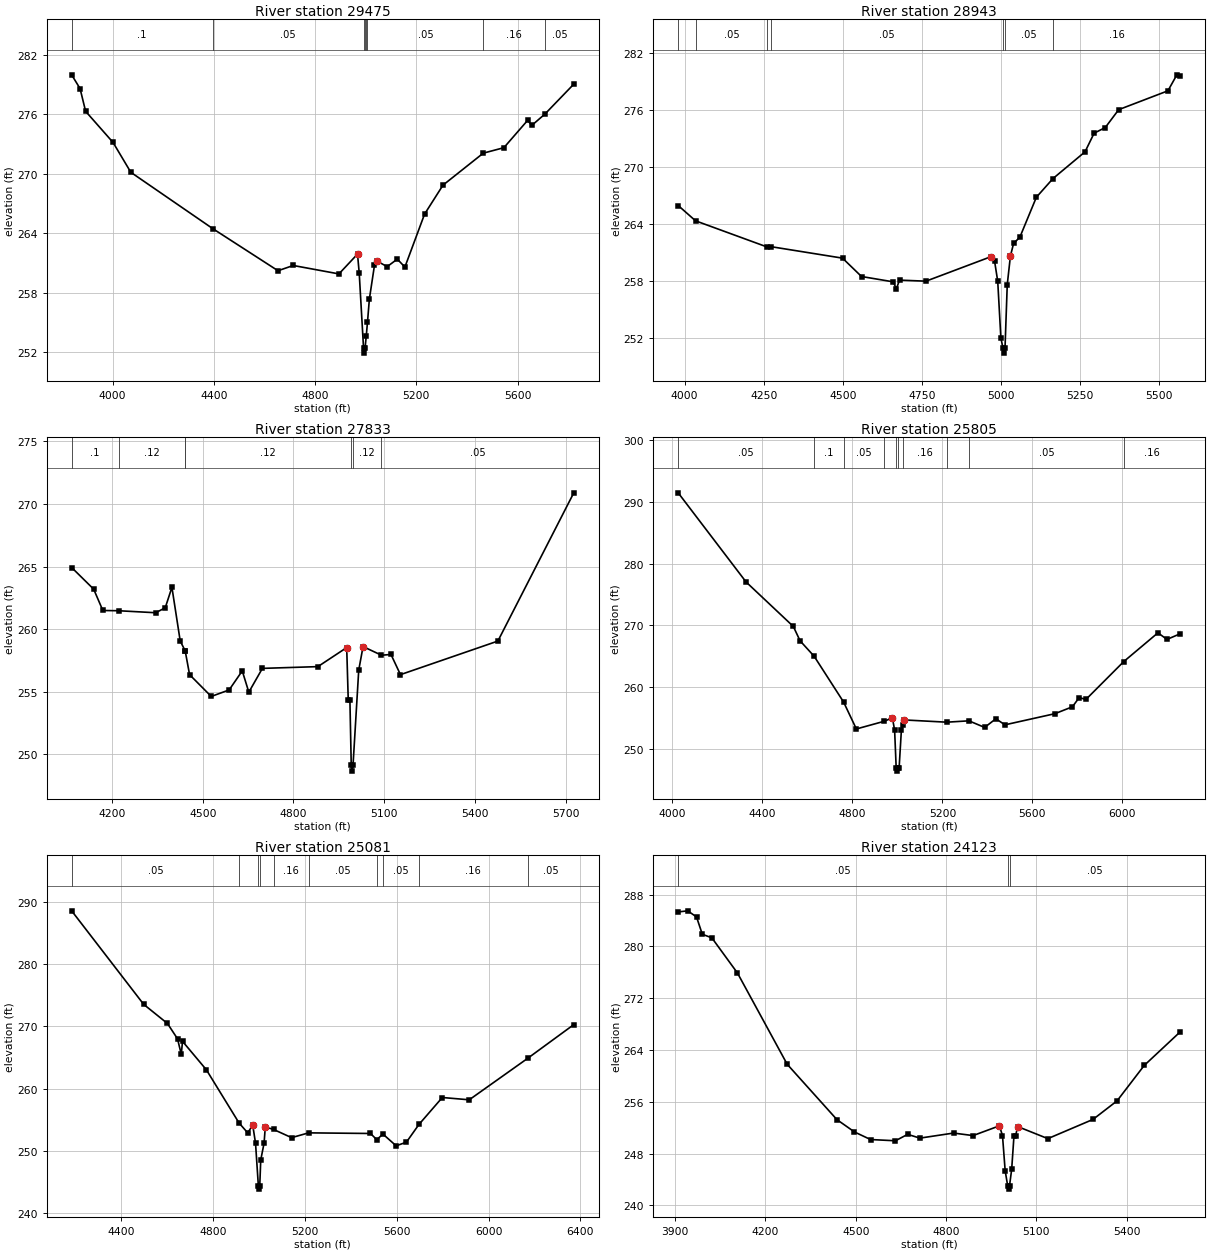
Type RM Length L Ch R = 1 ,29475   ,532,532,532
BEGIN DESCRIPTION:
RAGAN CREEK 32.0
END DESCRIPTION:
XS GIS Cut Line= 2
      3623333.24     10263288.46      3623480.76     10265267.07
#Sta/Elev= 30
    3838  279.96  3871.3  278.57  3893.2  276.28  4001.6  273.14  4071.8  270.13
  4395.4  264.45  4653.4   260.2  4713.6  260.73  4894.1  259.88  4967.6  261.88
  4974.3  259.96  4991.4  252.39  4994.1  251.89  4997.4  252.39    5002  253.59
  5006.9  254.99  5014.4  257.34  5034.5  260.74  5044.5  261.18  5084.6  260.61
  5124.7  261.37  5154.8  260.57  5232.5  265.91  5305.2  268.83  5464.5  272.06
  5545.9  272.61  5639.8  275.37  5656.2  274.86    5708     276  5822.1  279.02
#Mann= 8 ,-1 , 0
    3838      .1       0  4395.4     .05       0  4991.4    .035       0
  4997.4     .05       0    5002     .12       0  5006.9     .05       0
  5464.5     .16       0    5708     .05       0
Bank Sta=4967.6,5044.5
XS Rating Curve= 0 ,0
Exp/Cntr=0.3,0.1

Type RM Length L Ch R = 1 ,28943   ,1110,1110,1110
BEGIN DESCRIPTION:
RAGAN CREEK 31.0
END DESCRIPTION:
XS GIS Cut Line= 3
       3622942.1      10263642.9      3623016.16     10264927.67
      3623224.47     10265144.66
#Sta/Elev= 30
  3979.6  265.96  4034.6  264.35    4261   261.6    4274  261.63  4499.2  260.43
  4559.3   258.5  4659.5  257.94  4669.5  257.21  4679.5  258.12  4763.1  258.01
    4970   260.6    4980  260.12    4990     258    5000  252.01    5007  250.95
  5009.8  250.45    5013  250.95  5020.1  257.64  5030.1  260.65  5040.1  261.97
  5060.1  262.64  5112.2  266.83  5164.7  268.79    5266   271.6  5294.8  273.56
    5330  274.15  5372.5  276.03  5528.1  278.01  5556.4  279.69  5567.3  279.53
#Mann= 7 ,-1 , 0
  3979.6      .1       0  4034.6     .05       0    4261      .1       0
    4274     .05       0    5007    .035       0    5013     .05       0
  5164.7     .16       0
Bank Sta=4970,5030.1
XS Rating Curve= 0 ,0
Exp/Cntr=0.3,0.1

Type RM Length L Ch R = 1 ,27833   ,2028,2028,2028
BEGIN DESCRIPTION:
RAGAN CREEK 30.0
END DESCRIPTION:
XS GIS Cut Line= 3
      3622642.09     10263591.68      3622192.11     10264391.64
      3621942.12      10265091.6
#Sta/Elev= 30
  4066.1  264.92    4139  263.19  4169.3  261.49  4221.3  261.47  4344.3  261.31
  4375.8  261.71  4397.8  263.34  4425.2  259.06  4441.8  258.26  4441.9  258.24
  4456.2  256.37  4527.9  254.63  4587.1  255.15  4630.5  256.67  4652.2  254.97
  4697.1  256.87  4880.7  257.01    4976  258.53  4981.1  254.36  4986.6  254.36
    4991  249.17  4993.8  248.67    4997  249.17  5015.8  256.73  5030.1  258.61
  5091.1  257.92  5122.5  257.98  5153.8  256.37  5476.1  259.05  5727.2  270.88
#Mann= 7 ,-1 , 0
  4066.1      .1       0  4221.3     .12       0  4441.8      .1       0
  4441.9     .12       0    4991     .07       0    4997     .12       0
  5091.1     .05       0
Bank Sta=4976,5030.1
XS Rating Curve= 0 ,0
Exp/Cntr=0.3,0.1

Type RM Length L Ch R = 1 ,25805   ,724,724,724
BEGIN DESCRIPTION:
RAGAN CREEK 27.0
END DESCRIPTION:
XS GIS Cut Line= 2
       3621210.6     10263070.05      3621219.28     10265300.93
#Sta/Elev= 30
  4026.1  291.51  4327.7  277.05  4537.7  269.83  4567.7   267.5  4630.1     265
    4761  257.57  4817.7   253.2  4940.8  254.44  4977.7     255  4987.7  253.03
  4994.7  246.86  4997.4  246.36  5000.7  246.86  5007.7  246.88  5017.7  252.97
  5023.1  253.89  5027.7  254.67  5219.6   254.3  5317.8  254.52  5387.7  253.45
  5437.7  254.86  5477.7  253.87    5700  255.68  5777.7   256.8  5807.7  258.29
  5837.7  257.99  6005.6  264.13  6157.7   268.8  6197.7  267.73    6257  268.65
#Mann= 10 ,-1 , 0
  4026.1     .05       0  4630.1      .1       0    4761     .05       0
  4940.8     .12       0  4994.7     .07       0  5000.7     .12       0
  5023.1     .16       0  5219.6     .12       0  5317.8     .05       0
  6005.6     .16       0
Bank Sta=4977.7,5027.7
XS Rating Curve= 0 ,0
Exp/Cntr=0.3,0.1

Type RM Length L Ch R = 1 ,25081   ,958,958,958
BEGIN DESCRIPTION:
RAGAN CREEK 25.0
END DESCRIPTION:
XS GIS Cut Line= 3
      3620993.58     10263096.08      3620592.11     10263841.64
      3619992.12     10265041.62
#Sta/Elev= 30
  4183.1  288.57  4496.9  273.55  4600.7  270.47  4644.5  268.01  4660.8  265.53
  4666.4   267.6  4770.3  263.03  4912.8  254.48  4950.4   252.9  4972.3  254.14
  4984.5  251.24  4996.9  244.36  4999.6  243.86  5002.9  244.36  5007.2  248.54
  5021.8  251.26    5027  253.85  5062.9  253.45  5141.7  252.13    5216   252.9
  5485.5   252.8  5513.1   251.8  5539.6  252.71  5597.3  250.82    5642   251.4
  5696.7  254.25  5798.5  258.58  5915.9  258.21  6170.1  264.86  6371.5  270.29
#Mann= 10 ,-1 , 0
  4183.1     .05       0  4912.8     .12       0  4996.9     .07       0
  5002.9     .12       0  5062.9     .16       0    5216     .05       0
  5513.1     .16       0  5539.6     .05       0  5696.7     .16       0
  6170.1     .05       0
Bank Sta=4972.3,5027
XS Rating Curve= 0 ,0
Exp/Cntr=0.3,0.1

Type RM Length L Ch R = 1 ,24123   ,741,741,741
BEGIN DESCRIPTION:
RAGAN CREEK 23.0
END DESCRIPTION:
XS GIS Cut Line= 3
       3619642.1     10263091.62      3619842.11     10264191.64
      3619842.11     10264741.68
#Sta/Elev= 30
  3910.1  285.34  3941.9  285.51  3971.1  284.56  3990.2  281.89  4021.9  281.34
  4107.1   275.9  4272.2  261.81  4437.4  253.26  4495.8  251.35  4549.2  250.18
  4631.8  249.99  4672.4  250.98  4713.1   250.4  4824.9  251.18  4889.7  250.79
  4977.3   252.3  4987.5  250.78  4996.4  245.34  5004.8  243.02  5007.6  242.52
  5010.8  243.02    5018  245.58  5025.6  250.73  5030.7  250.73  5038.2  252.18
  5138.2  250.32  5288.2  253.29  5368.2  256.16  5458.2  261.62  5578.2  266.83
#Mann= 3 ,-1 , 0
  3910.1     .05       0  5004.8     .03       0  5010.8     .05       0
Bank Sta=4977.3,5038.2
XS Rating Curve= 0 ,0
Exp/Cntr=0.3,0.1

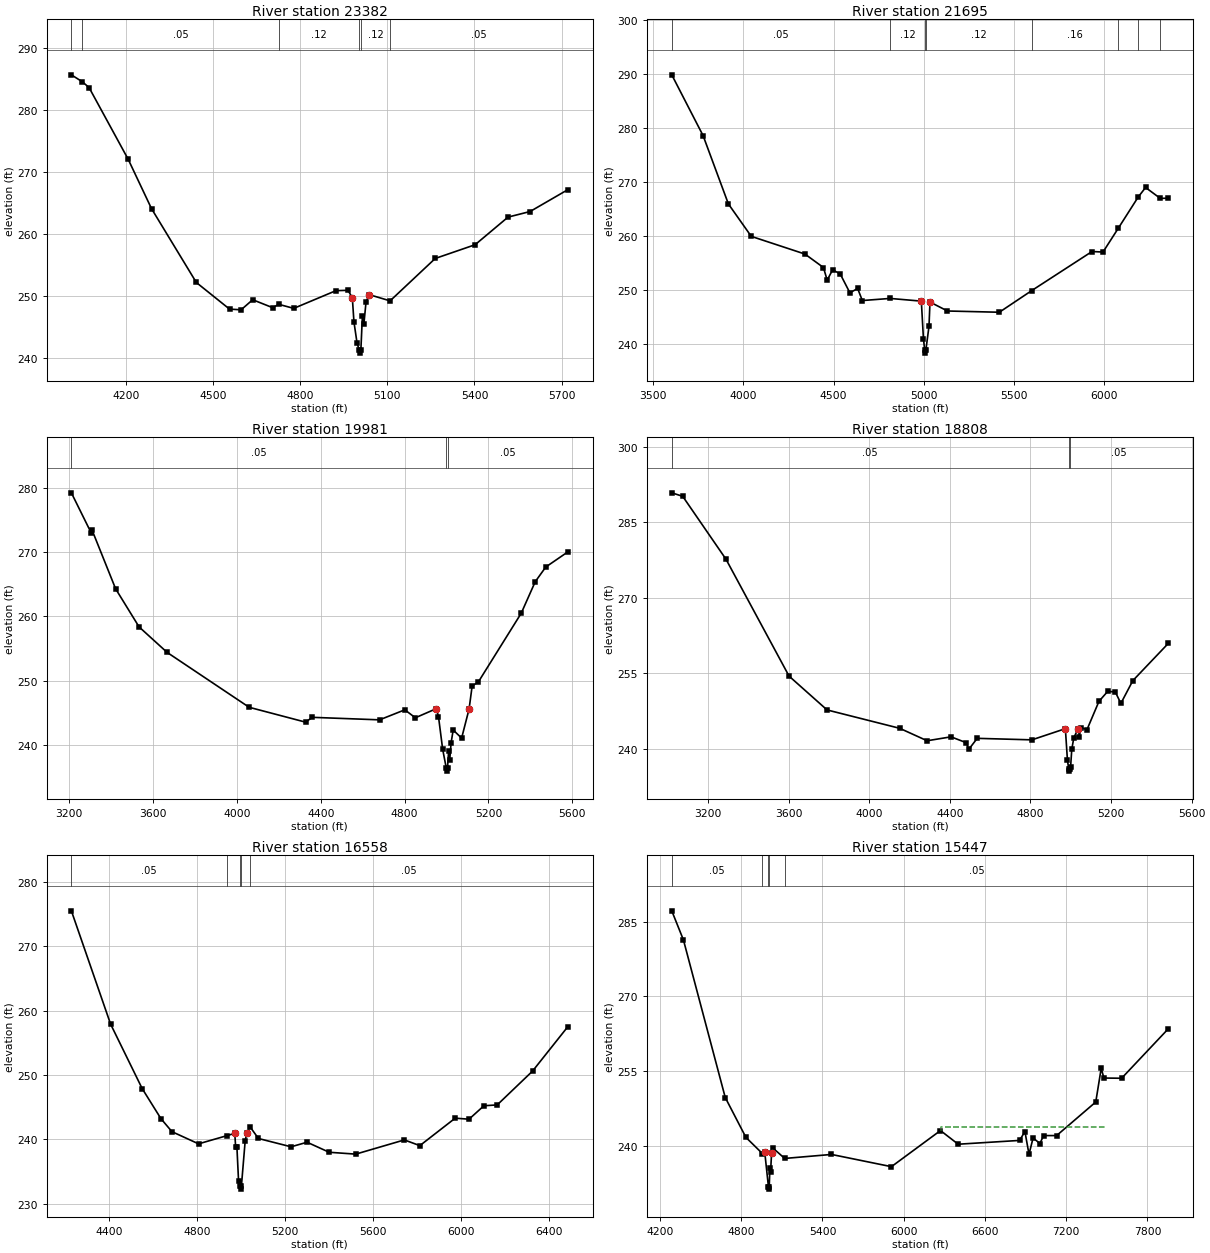
Type RM Length L Ch R = 1 ,23382   ,1687,1687,1687
BEGIN DESCRIPTION:
RAGAN CREEK 21.0
END DESCRIPTION:
XS GIS Cut Line= 3
      3618884.21     10263182.88      3619274.84     10264623.85
      3619464.57     10264727.34
#Sta/Elev= 30
  4012.5  285.68  4050.2  284.56  4073.4  283.63  4208.1  272.07  4288.4  264.12
  4442.6  252.23  4556.9  247.94  4596.7  247.83  4636.6  249.45  4705.4  248.17
  4726.2  248.71  4777.9  248.06    4923  250.91  4964.4  250.97  4979.5  249.79
  4985.1  245.88  4995.5  242.56  5002.9  241.35  5005.6  240.85  5008.9  241.35
  5014.2  246.87  5019.3  245.55  5026.6  249.04  5036.9  250.28  5109.5  249.27
  5264.9   256.1  5402.1  258.31  5515.4  262.76  5591.3  263.66  5721.6  267.19
#Mann= 6 ,-1 , 0
  4012.5     .16       0  4050.2     .05       0  4726.2     .12       0
  5002.9     .07       0  5008.9     .12       0  5109.5     .05       0
Bank Sta=4979.5,5036.9
XS Rating Curve= 0 ,0
Exp/Cntr=0.3,0.1

Type RM Length L Ch R = 1 ,21695   ,1714,1714,1714
BEGIN DESCRIPTION:
RAGAN CREEK 19.0
END DESCRIPTION:
XS GIS Cut Line= 2
      3617816.51     10262792.27      3618432.83     10265474.57
#Sta/Elev= 30
  3603.1  289.82  3776.9  278.53  3916.9  265.88  4043.7  259.87  4341.2  256.59
  4443.8  254.09  4464.3  251.75  4494.4  253.65  4536.2  252.93  4590.4   249.4
  4633.2  250.21  4659.3  247.97  4813.3  248.36  4986.3  247.86  4997.9  240.91
  5005.2  238.72  5007.9  238.22  5011.2  238.72  5028.7  243.19  5034.3  247.69
  5131.3  246.03  5418.6   245.8  5598.9  249.83  5932.3  257.06  5993.2  256.96
  6077.8  261.37  6188.2  267.16  6229.2  268.93  6310.8  266.91  6355.3  266.95
#Mann= 8 ,-1 , 0
  3603.1     .05       0  4813.3     .12       0  5005.2     .07       0
  5011.2     .12       0  5598.9     .16       0  6077.8      .1       0
  6188.2     .16       0  6310.8     .05       0
Bank Sta=4986.3,5034.3
XS Rating Curve= 0 ,0
Exp/Cntr=0.3,0.1

Type RM Length L Ch R = 1 ,19981   ,1173,1173,1173
BEGIN DESCRIPTION:
RAGAN CREEK 16.0
END DESCRIPTION:
XS GIS Cut Line= 2
      3617295.67     10262896.45      3617087.38     10265257.08
#Sta/Elev= 30
  3209.6  279.19  3303.6     273  3308.6  273.38  3420.7  264.28  3532.8  258.35
  3666.6  254.39  4058.1  245.86  4327.6  243.55  4359.2   244.3  4680.5  243.91
    4801  245.47  4851.1  244.23  4951.5  245.65  4961.6  244.42  4981.7  239.31
  4998.7  236.44  5001.5  235.94  5004.7  236.44  5010.2  239.11  5015.2  237.65
  5021.8  240.34  5031.8  242.33    5072  241.07 5107.67  245.59  5122.2  249.16
  5152.3  249.82  5356.5  260.48  5423.4  265.38  5473.7  267.66  5579.4  270.02
#Mann= 3 ,-1 , 0
  3209.6     .05       0  4998.7     .03       0  5004.7     .05       0
Bank Sta=4951.5,5107.67
XS Rating Curve= 0 ,0
Exp/Cntr=0.3,0.1

Type RM Length L Ch R = 1 ,18808   ,2250,2250,2250
BEGIN DESCRIPTION:
RAGAN CREEK 15.0
END DESCRIPTION:
XS GIS Cut Line= 3
      3617142.12     10262641.61      3616392.11     10264441.64
      3616142.11     10264891.63
#Sta/Elev= 30
  3019.4  290.82  3073.6  290.13  3288.6  277.63  3601.7  254.42  3790.2  247.71
    4151  244.06  4286.9  241.59  4405.6  242.37  4481.9  241.19  4493.3  239.87
  4535.6  242.07  4806.9  241.77 4973.07  243.99  4983.2  237.83  4989.3  236.06
  4992.1  235.56  4995.3  236.06  4999.2  236.46  5004.9  239.89  5015.2  242.21
  5036.9  244.02  5042.6  242.41  5049.5  244.22  5080.4   243.8  5139.9  249.42
  5183.4   251.4  5221.1  251.27  5248.6  249.01    5308  253.53  5484.2  260.93
#Mann= 3 ,-1 , 0
  3019.4     .05       0  4989.3     .03       0  4995.3     .05       0
Bank Sta=4973.07,5036.9
XS Rating Curve= 0 ,0
Exp/Cntr=0.3,0.1

Type RM Length L Ch R = 1 ,16558   ,1111,1111,1111
BEGIN DESCRIPTION:
RAGAN CREEK 13.0
END DESCRIPTION:
XS GIS Cut Line= 3
      3616142.13     10262491.61      3615692.11     10263091.64
      3615542.11     10264591.62
#Sta/Elev= 30
  4227.1  275.51  4405.3  257.91    4549  247.88  4634.4   243.2  4684.4  241.18
  4805.3  239.29  4933.2  240.55 4969.98  240.92    4974  238.77  4979.7  238.77
  4987.2  233.51  4994.2  232.75    4997  232.25  5000.2  232.75  5017.3  239.76
  5024.9  240.97  5038.8  241.96  5077.6  240.12  5225.9  238.83  5298.7  239.54
  5399.2  237.98  5519.8  237.69  5740.9   239.9  5811.3  239.01  5972.1  243.28
  6034.9  243.12  6102.7  245.21    6163  245.34  6323.8   250.6  6484.6  257.52
#Mann= 5 ,-1 , 0
  4227.1     .05       0  4933.2     .12       0  4994.2     .07       0
  5000.2     .12       0  5038.8     .05       0
Bank Sta=4969.98,5024.9
XS Rating Curve= 0 ,0
Exp/Cntr=0.3,0.1

Type RM Length L Ch R = 1 ,15447   ,1641,1641,1641
BEGIN DESCRIPTION:
RAGAN CREEK 11.0
END DESCRIPTION:
XS GIS Cut Line= 2
       3615186.3     10262089.08      3614787.04     10265734.48
#Sta/Elev= 30
    4287  287.15  4373.3   281.3  4681.9  249.74  4834.3  241.76  4956.6   238.5
  4973.6   238.8  5000.8  231.88  5003.6  231.38  5006.8  231.88  5011.6  235.58
  5016.7  234.82  5023.9  238.53    5034  239.61    5121  237.53  5466.6  238.33
  5909.2  235.88  6271.4  243.12  6402.1  240.38  6855.6  241.14  6895.1  242.92
  6925.2  238.36  6955.4  241.64  7005.7  240.52    7033  242.11  7129.2  242.11
  7418.2  248.84  7458.4  255.58  7478.5  253.64  7609.3   253.6  7954.2  263.52
#Mann= 5 ,-1 , 0
    4287     .05       0  4956.6     .12       0  5000.8     .07       0
  5006.8     .12       0    5121     .05       0
#XS Ineff= 1 ,-1
 6274.02 7504.26  243.82
Permanent Ineff=
       F
Bank Sta=4973.6,5023.9
XS Rating Curve= 0 ,0
Exp/Cntr=0.3,0.1

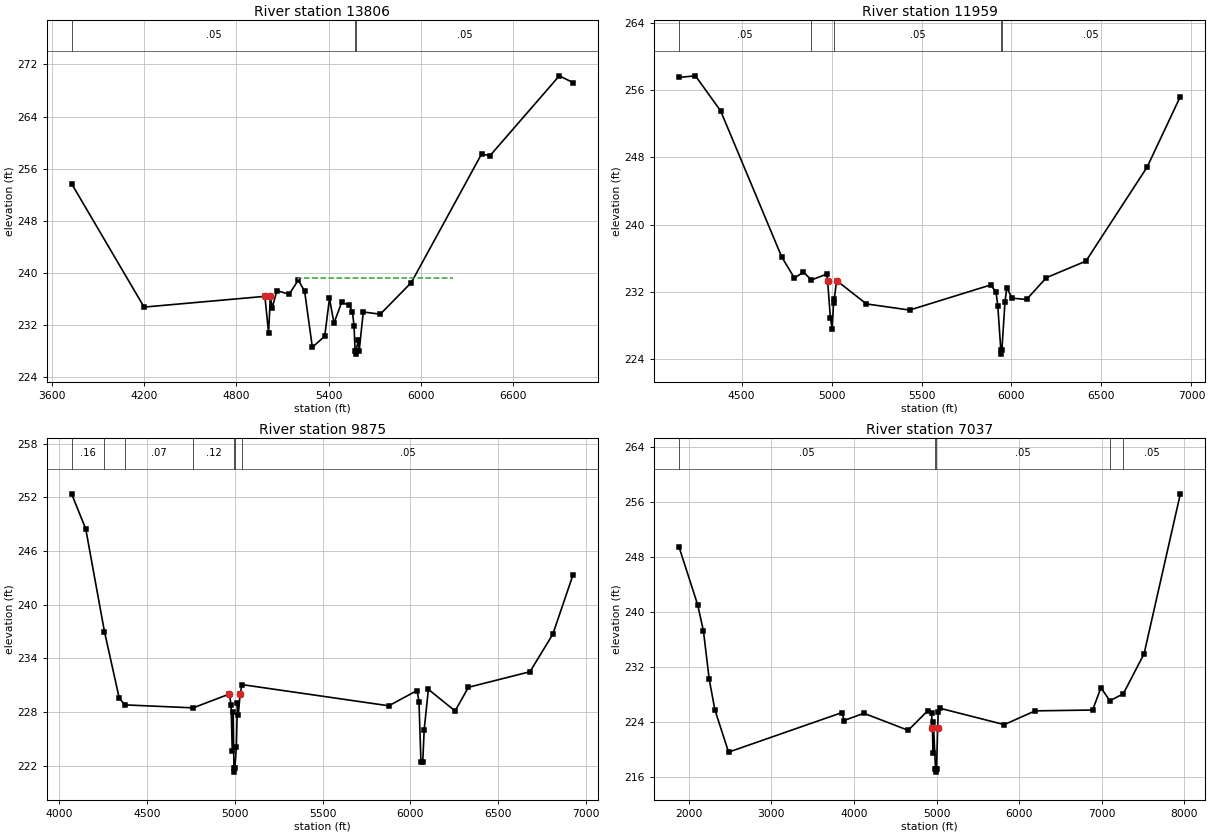
Type RM Length L Ch R = 1 ,13806   ,1847,1847,1847
BEGIN DESCRIPTION:
RAGAN CREEK 9.0
END DESCRIPTION:
XS GIS Cut Line= 3
      3613988.38     10262332.19      3613762.69     10264528.37
      3614161.46     10265507.97
#Sta/Elev= 30
  3726.4   253.7  4198.3  234.76 4985.09  236.41    5009  230.79 5020.65   236.4
  5032.7  234.63  5062.9  237.28  5143.3  236.74  5202.4   238.9  5243.8  237.19
  5294.1  228.59  5374.5  230.29  5405.7  236.09  5434.8  232.29  5485.1   235.5
  5535.3  235.02  5555.4  233.97  5565.5  231.88  5572.5  228.04  5575.3  227.54
  5578.5  228.04    5594  229.74  5599.1  228.06  5625.8  234.01  5736.4  233.67
  5938.6  238.53  6396.6  258.28  6450.2  257.98  6902.3  270.26  6991.8  269.22
#Mann= 3 ,-1 , 0
  3726.4     .05       0  5572.5     .03       0  5578.5     .05       0
#XS Ineff= 1 ,-1
 5202.27 6208.52  239.22
Permanent Ineff=
       F
Bank Sta=4985.09,5020.65
XS Rating Curve= 0 ,0
Exp/Cntr=0.3,0.1

Type RM Length L Ch R = 1 ,11959   ,2084,2084,2084
BEGIN DESCRIPTION:
RAGAN CREEK 6.0
END DESCRIPTION:
XS GIS Cut Line= 2
      3612764.42     10262479.72       3612773.1     10265266.21
#Sta/Elev= 30
  4151.8  257.51  4243.7   257.7  4383.7  253.53  4723.7  236.14  4793.7  233.66
  4843.7  234.36  4888.4  233.43  4973.7  234.13 4978.19  233.34  4993.7  228.89
  5003.7  227.63    5011  230.65  5015.3  231.14 5027.98  233.36  5193.7  230.58
  5433.7  229.85  5883.7  232.83  5913.7  232.03  5923.7  230.39  5940.7  225.11
  5943.5  224.61  5946.7  225.11  5963.7  230.79  5973.7  232.51  6003.7  231.26
  6083.7  231.11  6193.7   233.7  6413.7  235.67  6753.7  246.85  6938.3  255.24
#Mann= 5 ,-1 , 0
  4151.8     .05       0  4888.4     .12       0  5015.3     .05       0
  5940.7     .07       0  5946.7     .05       0
Bank Sta=4978.19,5027.98
XS Rating Curve= 0 ,0
Exp/Cntr=0.3,0.1

Type RM Length L Ch R = 1 ,9875    ,2838,2838,2838
BEGIN DESCRIPTION:
RAGAN CREEK 5.0
END DESCRIPTION:
XS GIS Cut Line= 3
      3611642.11     10262041.62      3611542.11     10262941.64
      3612292.12     10264741.68
#Sta/Elev= 30
  4070.9   252.4  4151.4  248.47    4258  236.98  4342.6  229.51  4375.8  228.79
  4763.1  228.46 4969.83  230.01  4979.2  228.73  4985.7  223.65  4991.1  228.01
  4995.1  221.77  4997.9  221.27  5001.1  221.77    5009  224.08  5014.9     229
  5020.3   227.7  5030.6  230.03  5041.3  231.06  5877.2  228.69  6038.1   230.4
    6049  229.16  6060.3  222.41  6070.6  222.44  6078.7  226.03  6102.6  230.53
  6254.8  228.11  6330.6  230.76  6681.1   232.5  6811.1  236.69  6926.5  243.35
#Mann= 7 ,-1 , 0
  4070.9     .16       0    4258     .12       0  4375.8     .07       0
  4763.1     .12       0  4995.1     .07       0  5001.1     .12       0
  5041.3     .05       0
Bank Sta=4969.83,5030.6
XS Rating Curve= 0 ,0
Exp/Cntr=0.3,0.1

Type RM Length L Ch R = 1 ,7037    ,0,0,0
BEGIN DESCRIPTION:
RAGAN CREEK 1.0
END DESCRIPTION:
XS GIS Cut Line= 3
      3609142.61     10259856.94      3609840.52     10264530.54
      3610934.25     10265311.77
#Sta/Elev= 30
  1881.7  249.58  2108.9  241.11  2178.8   237.3    2248  230.33  2317.3  225.83
    2483  219.69  3858.1  225.45  3879.5  224.28    4121  225.34  4656.8  222.86
  4892.9   225.7  4939.9  225.33 4950.52   223.2  4957.1  219.58  4962.1  224.02
  4987.5  217.28  4990.2  216.78  4993.5  217.28  5000.6   217.3 5013.23   223.2
  5020.8  225.48    5041  226.07  5819.6  223.69  6193.7  225.69  6889.2  225.81
    6990  229.05  7098.2  227.16  7260.4  228.17  7512.3  233.99  7951.2  257.25
#Mann= 5 ,-1 , 0
  1881.7     .05       0  4987.5     .03       0  4993.5     .05       0
  7098.2     .16       0  7260.4     .05       0
Bank Sta=4950.52,5013.23
XS Rating Curve= 0 ,0
Exp/Cntr=0.3,0.1

Chan Stop Cuts=-1
Use User Specified Reach Order=0
Composite Channel Slope=5