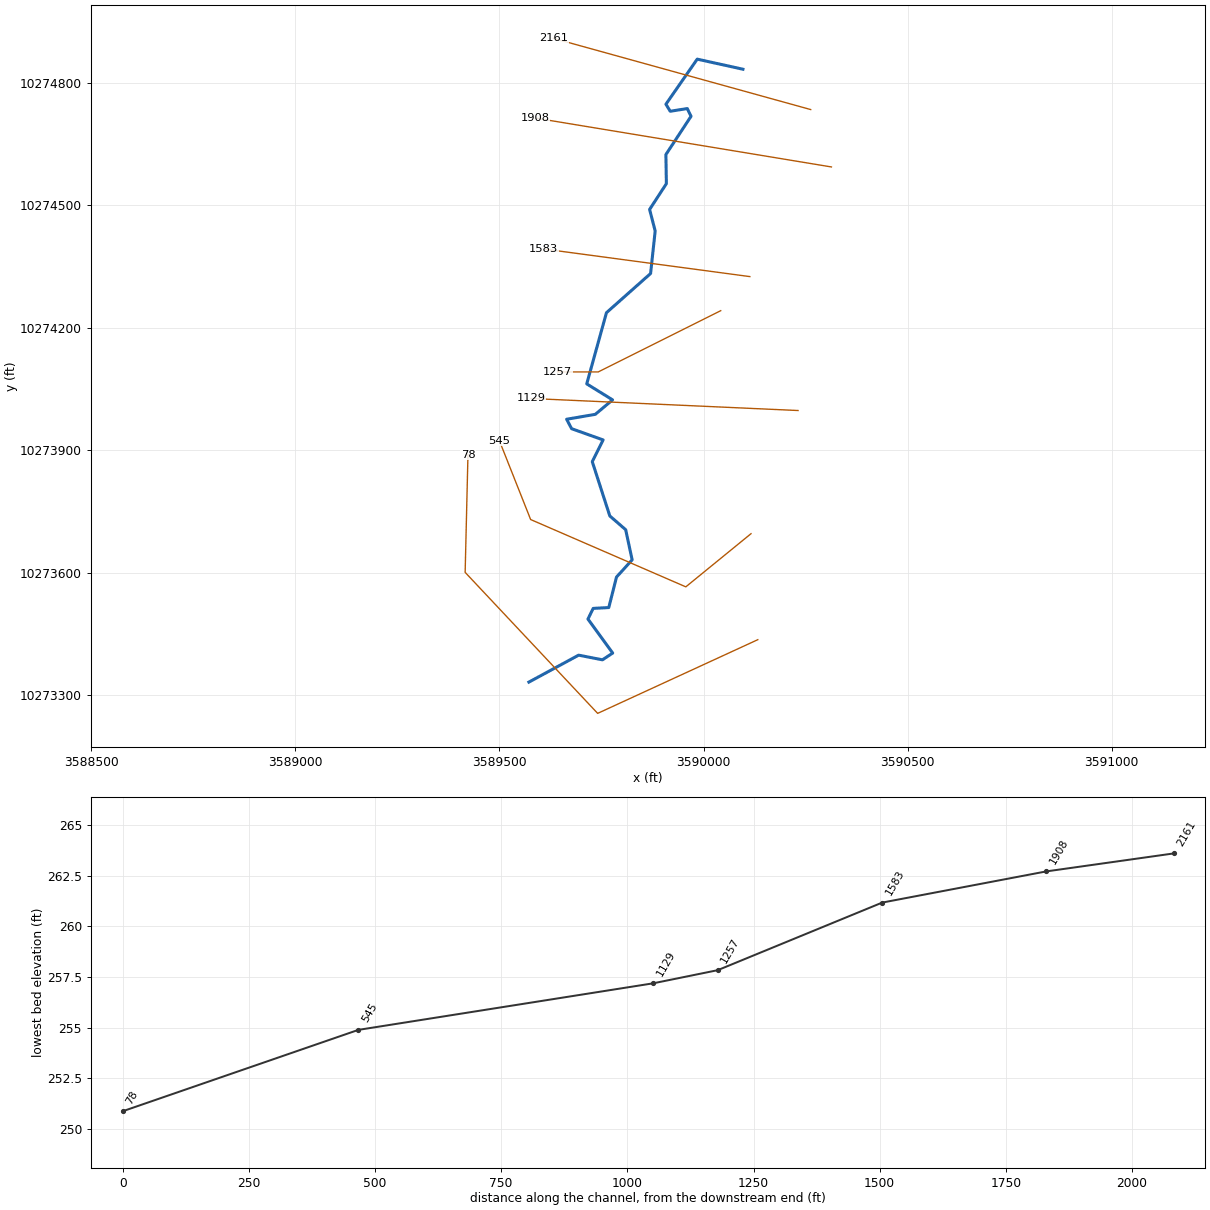
--- ROBERTSONBRANCHTR.prj (project) ---

Proj Title=ROBERTSON BRANCH TRIB 1
Current Plan=p01
Default Exp/Contr=0.3,0.1
English Units
Geom File=g01
Flow File=f01
Plan File=p01
Y Axis Title=Elevation
X Axis Title(PF)=Main Channel Distance
X Axis Title(XS)=Station
BEGIN DESCRIPTION:
UNT04918 IN WICK
END DESCRIPTION:
DSS Export Rating Curves= 0
DSS Export Rating Curve Sorted= 0
DSS Export Volume Flow Curves= 0
DXF OffsetX= 0
DXF OffsetY= 0
DXF ScaleX= 1
DXF ScaleY= 10

--- ROBERTSONBRANCHTR.p01 (plan) ---

Plan Title=Multiple Run
Short Identifier=Multiple
Geom File=g01
Flow File=f01
Subcritical Flow
K Sum by GR= 0
Std Step Tol= 0.01
Critical Tol= 0.01
Num of Std Step Trials= 20
Max Error Tol= 0.3
Flow Tol Ratio= 0.001
Split Flow NTrial= 30
Split Flow Tol= 0.02
Split Flow Ratio= 0.02
Log Output Level= 0
Friction Slope Method= 1
Unsteady Friction Slope Method= 2
Unsteady Bridges Friction Slope Method= 1
Parabolic Critical Depth
Global Vel Dist=  1 , 1 , 1
Global Log Level= 0
CheckData=True
Encroach Param= -1, 0, 0, 0
BEGIN DESCRIPTION:
Multiple Run
END DESCRIPTION:

--- ROBERTSONBRANCHTR.f01 (steady flow) ---

Flow Title=Multiple
Program Version=4.10
Number of Profiles= 7
Profile Names=10-year,25-year,50-year,1pct_min,100-year,1pct_plu,500-year
River Rch & RM=UNT04918 IN WICK,Reach-1         ,2161
     291     375     441     381     516     697     705
River Rch & RM=ROBERTSONBRTRIB1,Reach-1         ,2161
     291     375     441     381     516     697     705
Boundary for River Rch & Prof#=ROBERTSONBRTRIB1,Reach-1         , 1
Up Type= 0
Dn Type= 3
Dn Slope=0.005
Boundary for River Rch & Prof#=ROBERTSONBRTRIB1,Reach-1         , 2
Up Type= 0
Dn Type= 3
Dn Slope=0.005
Boundary for River Rch & Prof#=ROBERTSONBRTRIB1,Reach-1         , 3
Up Type= 0
Dn Type= 3
Dn Slope=0.005
Boundary for River Rch & Prof#=ROBERTSONBRTRIB1,Reach-1         , 4
Up Type= 0
Dn Type= 3
Dn Slope=0.005
Boundary for River Rch & Prof#=ROBERTSONBRTRIB1,Reach-1         , 5
Up Type= 0
Dn Type= 3
Dn Slope=0.005
Boundary for River Rch & Prof#=ROBERTSONBRTRIB1,Reach-1         , 6
Up Type= 0
Dn Type= 3
Dn Slope=0.005
Boundary for River Rch & Prof#=ROBERTSONBRTRIB1,Reach-1         , 7
Up Type= 0
Dn Type= 3
Dn Slope=0.005
DSS Import GetInterval= 0
DSS Import GetPeak= 0
DSS Import FillOption= 0

--- ROBERTSONBRANCHTR.g01 (geometry) ---

Geom Title=Existing Conditions
Program Version=4.10

River Reach=ROBERTSONBRTRIB1,Reach-1
Reach XY= 30
      3590096.49     10274833.28      3589984.55     10274857.95
      3589907.87     10274747.53      3589918.46     10274730.27
      3589960.19      10274736.9      3589969.38     10274717.88
      3589907.81     10274624.19      3589908.99     10274552.83
      3589867.92     10274489.73      3589881.53     10274436.86
      3589870.32     10274332.71       3589762.2     10274236.74
      3589713.87     10274062.34      3589777.14     10274023.16
      3589734.89     10273987.72      3589664.61     10273975.67
      3589676.77     10273952.57      3589753.99     10273925.02
      3589727.39     10273871.87      3589770.37     10273738.79
      3589809.28     10273705.01      3589825.12     10273631.19
      3589786.79     10273588.96      3589767.89      10273514.3
      3589729.72     10273512.25      3589716.83     10273486.11
      3589777.45     10273402.83      3589752.35     10273386.26
        3589694.     10273397.67      3589572.11     10273331.64

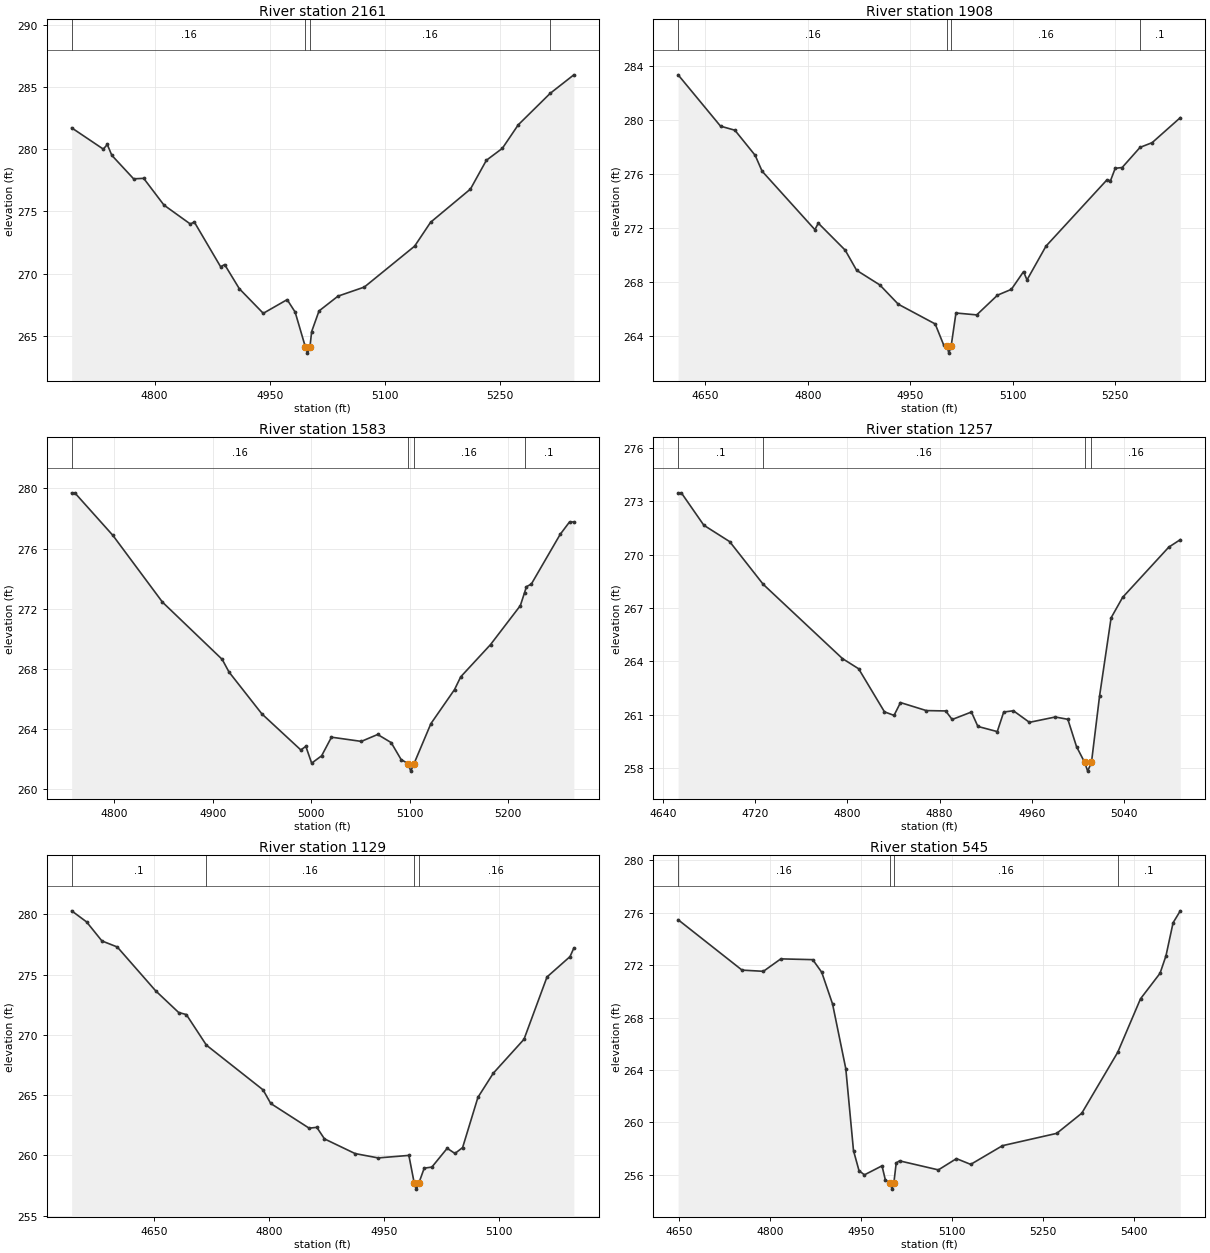
Type RM Length L Ch R = 1 ,2161    ,253,253,253
BEGIN DESCRIPTION:
UNT04918 IN WICK 3.0
END DESCRIPTION:
XS GIS Cut Line= 2
      3590262.53     10274734.46      3589632.34     10274908.94
#Sta/Elev= 30
  4692.1  281.72  4733.3  280.01  4738.5  280.38  4744.4  279.51  4772.8  277.62
  4785.9  277.66  4812.3  275.51  4846.6  273.99  4851.8  274.15  4886.1  270.55
  4891.3  270.73  4910.4  268.79  4941.6  266.81  4972.7  267.91  4983.1  266.91
  4996.4  264.11  4999.1  263.61  5002.4  264.11  5004.6  265.34  5014.2     267
  5038.9  268.19  5073.2  268.92  5138.7  272.21  5159.5  274.13  5211.4   276.8
  5232.1  279.11  5252.9  280.07  5273.6  281.96  5315.2  284.49    5346  285.98
#Mann= 4 ,-1 , 0
  4692.1     .16       0  4996.4     .07       0  5002.4     .16       0
  5315.2      .1       0
Bank Sta=4996.4,5002.4
XS Rating Curve= 0 ,0
Exp/Cntr=0.3,0.1

Type RM Length L Ch R = 1 ,1908    ,325,325,325
BEGIN DESCRIPTION:
Mapping XS 1554db12
END DESCRIPTION:
XS GIS Cut Line= 2
      3590313.39     10274593.82      3589588.11     10274713.61
#Sta/Elev= 30
  4610.1  283.32  4672.2  279.52  4693.2  279.22  4722.9  277.36    4733  276.19
  4810.3  271.86  4815.3  272.34  4854.7  270.34  4871.4  268.85  4905.3  267.77
  4932.4  266.34  4986.4  264.88  4998.6  263.35  5003.7  263.22  5006.4  262.72
  5009.7  263.22  5016.8  265.69  5047.2  265.55  5077.6  267.01  5097.9  267.44
  5115.7  268.75  5120.8  268.14  5148.6  270.64  5237.9  275.55    5243  275.48
  5249.9   276.4  5260.1  276.46  5286.3  277.95    5304   278.3  5345.2  280.15
#Mann= 4 ,-1 , 0
  4610.1     .16       0  5003.7     .07       0  5009.7     .16       0
  5286.3      .1       0
Bank Sta=5003.7,5009.7
XS Rating Curve= 0 ,0
Exp/Cntr=0.3,0.1

Type RM Length L Ch R = 1 ,1583    ,326,326,326
BEGIN DESCRIPTION:
Mapping XS 11dba211
END DESCRIPTION:
XS GIS Cut Line= 2
      3590113.51     10274325.18      3589608.33     10274392.88
#Sta/Elev= 30
  4756.8  279.71    4760  279.71  4798.6  276.88    4849  272.43  4909.6  268.62
  4916.5  267.78  4949.9  264.99  4989.4  262.59  4994.5  262.83  5000.4  261.71
  5010.5   262.2  5020.5  263.44  5050.8  263.16  5067.4  263.62  5081.1  263.08
  5091.2  261.95  5098.3  261.68    5101  261.18  5104.3  261.68  5121.4  264.34
  5145.4  266.61  5151.7  267.46    5182  269.61  5212.2   272.2  5216.5  273.07
  5218.4  273.46  5223.4  273.64  5252.6  276.94  5262.1  277.77  5266.5  277.77
#Mann= 4 ,-1 , 0
  4756.8     .16       0  5098.3     .07       0  5104.3     .16       0
  5216.5      .1       0
Bank Sta=5098.3,5104.3
XS Rating Curve= 0 ,0
Exp/Cntr=0.3,0.1

Type RM Length L Ch R = 1 ,1257    ,128,128,128
BEGIN DESCRIPTION:
UNT04918 IN WICK 2.0
END DESCRIPTION:
XS GIS Cut Line= 3
      3590042.09     10274241.63      3589742.11     10274091.64
      3589642.09     10274091.64
#Sta/Elev= 30
  4653.3  273.47  4656.1  273.47  4675.6  271.65    4698  270.73  4727.1  268.33
  4795.8  264.16  4809.8  263.59  4832.2  261.17  4840.5  260.97  4846.1  261.69
  4868.5  261.24  4885.3  261.22  4890.9  260.74  4907.6  261.16  4913.2  260.35
    4930  260.06  4935.6  261.16    4944  261.23  4957.9  260.58  4980.3  260.88
  4991.2  260.75  4998.7  259.22  5005.7  258.34  5008.4  257.84  5011.7  258.34
  5018.7  262.06  5028.7  266.45  5038.7   267.6  5078.7  270.42  5088.7  270.84
#Mann= 4 ,-1 , 0
  4653.3      .1       0  4727.1     .16       0  5005.7     .07       0
  5011.7     .16       0
Bank Sta=5005.7,5011.7
XS Rating Curve= 0 ,0
Exp/Cntr=0.3,0.1

Type RM Length L Ch R = 1 ,1129    ,584,584,584
BEGIN DESCRIPTION:
Mapping XS e5925541
END DESCRIPTION:
XS GIS Cut Line= 2
      3590231.56     10273997.06      3589577.12     10274026.57
#Sta/Elev= 30
  4542.1  280.29  4561.6  279.37  4581.6  277.79  4601.6  277.29  4651.7  273.65
  4681.7  271.85  4691.7  271.68  4717.9  269.14  4791.8  265.43  4801.8   264.3
  4851.9  262.25  4861.9  262.32  4871.9  261.36  4911.9  260.14    4942  259.78
    4982  259.99    4989  257.69  4991.8  257.19    4995  257.69    5002  258.93
    5012  259.02    5032  260.58  5042.1  260.15  5052.1  260.64  5072.1  264.81
  5092.1  266.81  5132.2  269.63  5162.2   274.8  5192.2  276.49  5197.2   277.2
#Mann= 4 ,-1 , 0
  4542.1      .1       0  4717.9     .16       0    4989     .07       0
    4995     .16       0
Bank Sta=4989,4995
XS Rating Curve= 0 ,0
Exp/Cntr=0.3,0.1

Type RM Length L Ch R = 1 ,545     ,467,467,467
BEGIN DESCRIPTION:
Mapping XS 1da1e0bf
END DESCRIPTION:
XS GIS Cut Line= 4
      3590116.36     10273695.28      3589956.62     10273565.05
      3589576.41     10273729.98      3589500.03     10273922.66
#Sta/Elev= 30
  4648.8  275.47  4754.2  271.62  4789.4  271.53  4818.1  272.48  4870.7  272.42
  4885.5  271.46  4903.4  269.03  4925.2  264.09  4937.9  257.83    4947   256.3
  4955.9  255.98  4984.9  256.67  4990.6  255.55  4998.5  255.39  5001.3  254.89
  5004.5  255.39  5008.3  256.89  5013.8  257.05  5077.8  256.36  5107.6  257.22
  5131.1  256.78  5183.5  258.21  5272.9  259.15  5314.2  260.69  5373.4  265.34
    5411  269.43  5443.2  271.38    5453  272.72  5464.7  275.24  5476.6  276.15
#Mann= 4 ,-1 , 0
  4648.8     .16       0  4998.5     .07       0  5004.5     .16       0
  5373.4      .1       0
Bank Sta=4998.5,5004.5
XS Rating Curve= 0 ,0
Exp/Cntr=0.3,0.1

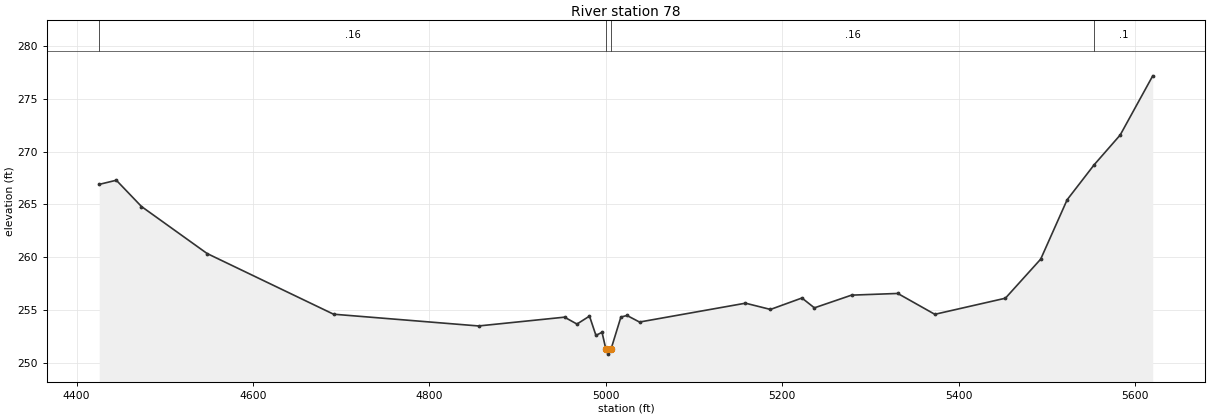
Type RM Length L Ch R = 1 ,78      ,0,0,0
BEGIN DESCRIPTION:
UNT04918 IN WICK 1.0
END DESCRIPTION:
XS GIS Cut Line= 4
      3590132.95     10273435.59      3589740.62     10273255.04
      3589415.96     10273600.53      3589422.86     10273888.57
#Sta/Elev= 30
  4425.7   266.9  4445.1  267.29  4473.6  264.81    4548  260.37  4691.3  254.64
  4855.7  253.53  4953.1  254.36  4967.2  253.71  4981.4  254.46  4988.7  252.64
  4995.6  252.93  4999.9  251.37  5002.6  250.87  5005.9  251.37    5017  254.37
  5023.9  254.52  5038.1   253.9  5158.2  255.68  5186.5  255.09  5222.2  256.17
  5236.3  255.24  5278.4  256.44  5330.8   256.6  5372.8  254.63  5452.8  256.15
  5492.8  259.84  5522.8  265.45  5553.4  268.75  5582.9  271.56  5619.8  277.15
#Mann= 4 ,-1 , 0
  4425.7     .16       0  4999.9     .07       0  5005.9     .16       0
  5553.4      .1       0
Bank Sta=4999.9,5005.9
XS Rating Curve= 0 ,0
Exp/Cntr=0.3,0.1

Chan Stop Cuts=-1
Use User Specified Reach Order=0
Composite Channel Slope=5