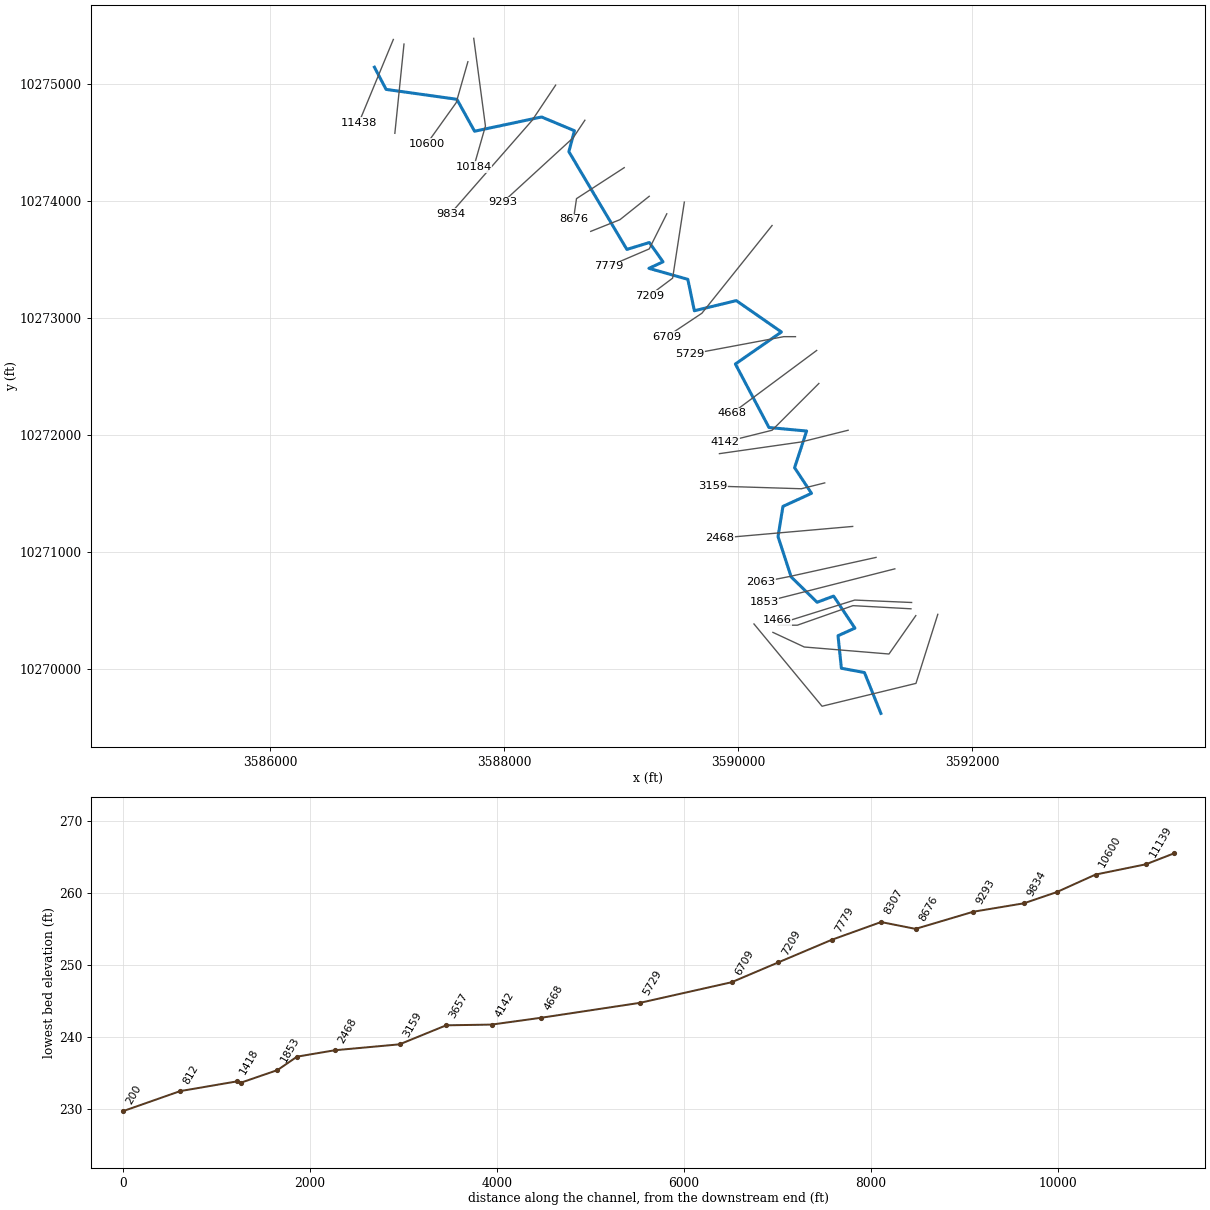
--- ROBERTSON BRANCH.prj (project) ---

Proj Title=ROBERTSON BRANCH Base Level Engineering
Current Plan=p01
Default Exp/Contr=0.3,0.1
English Units
Geom File=g01
Flow File=f01
Plan File=p01
BEGIN DESCRIPTION:
ROBERTSON BRANCH
END DESCRIPTION:

--- ROBERTSON BRANCH.p01 (plan) ---

Plan Title=Multiple Run
Short Identifier=Multiple
Geom File=g01
Flow File=f01
Subcritical Flow
K Sum by GR= 0
Std Step Tol= 0.01
Critical Tol= 0.01
Num of Std Step Trials= 20
Max Error Tol= 0.3
Flow Tol Ratio= 0.001
Split Flow NTrial= 30
Split Flow Tol= 0.02
Split Flow Ratio= 0.02
Log Output Level= 0
Friction Slope Method= 1
Unsteady Friction Slope Method= 2
Unsteady Bridges Friction Slope Method= 1
Parabolic Critical Depth
Global Vel Dist=  1 , 1 , 1
Global Log Level= 0
CheckData=True
Encroach Param= -1, 0, 0, 0
BEGIN DESCRIPTION:
Multiple Run
END DESCRIPTION:

--- ROBERTSON BRANCH.f01 (steady flow) ---

Flow Title=Multiple
Number of Profiles=7
Profile Names=10-year,25-year,50-year,1pct_min,100-year,1pct_plu,500-year
River Rch & RM= ROBERTSON BRANCH,Reach-1,11438
     659     889    1077     956    1292    1748    1863
River Rch & RM= ROBERTSON BRANCH,Reach-1,6709
     841    1148    1401    1250    1691    2286    2469
Boundary for River Rch & Prof#=ROBERTSON BRANCH,Reach-1,1
Up Type=0
Dn Type=3
Dn Slope=0.005
Boundary for River Rch & Prof#=ROBERTSON BRANCH,Reach-1,2
Up Type=0
Dn Type=3
Dn Slope=0.005
Boundary for River Rch & Prof#=ROBERTSON BRANCH,Reach-1,3
Up Type=0
Dn Type=3
Dn Slope=0.005
Boundary for River Rch & Prof#=ROBERTSON BRANCH,Reach-1,4
Up Type=0
Dn Type=3
Dn Slope=0.005
Boundary for River Rch & Prof#=ROBERTSON BRANCH,Reach-1,5
Up Type=0
Dn Type=3
Dn Slope=0.005
Boundary for River Rch & Prof#=ROBERTSON BRANCH,Reach-1,6
Up Type=0
Dn Type=3
Dn Slope=0.005
Boundary for River Rch & Prof#=ROBERTSON BRANCH,Reach-1,7
Up Type=0
Dn Type=3
Dn Slope=0.005

--- ROBERTSON BRANCH.g01 (geometry) ---

Geom Title=Existing Conditions

River Reach=ROBERTSON BRANCH,Reach-1
Reach XY= 30
      3586893.18     10275144.86      3586993.02     10274955.16
      3587597.93     10274870.61      3587749.16     10274597.58
      3588321.98     10274719.35      3588602.91     10274602.00
      3588555.22     10274423.20      3589050.91     10273587.39
      3589243.06     10273646.10      3589360.08     10273481.42
      3589239.74     10273425.66      3589572.11     10273331.64
      3589627.94     10273063.08      3589986.41     10273149.75
      3590371.93     10272881.47      3589978.43     10272607.94
      3590265.68     10272064.99      3590587.50     10272034.89
      3590484.45     10271721.53      3590629.30     10271502.50
      3590385.06     10271390.78      3590343.13     10271132.46
      3590455.37     10270788.05      3590677.19     10270571.23
      3590817.97     10270624.16      3591000.17     10270350.36
      3590855.86     10270285.24      3590884.65     10270007.29
      3591081.60     10269970.70      3591222.11     10269621.64

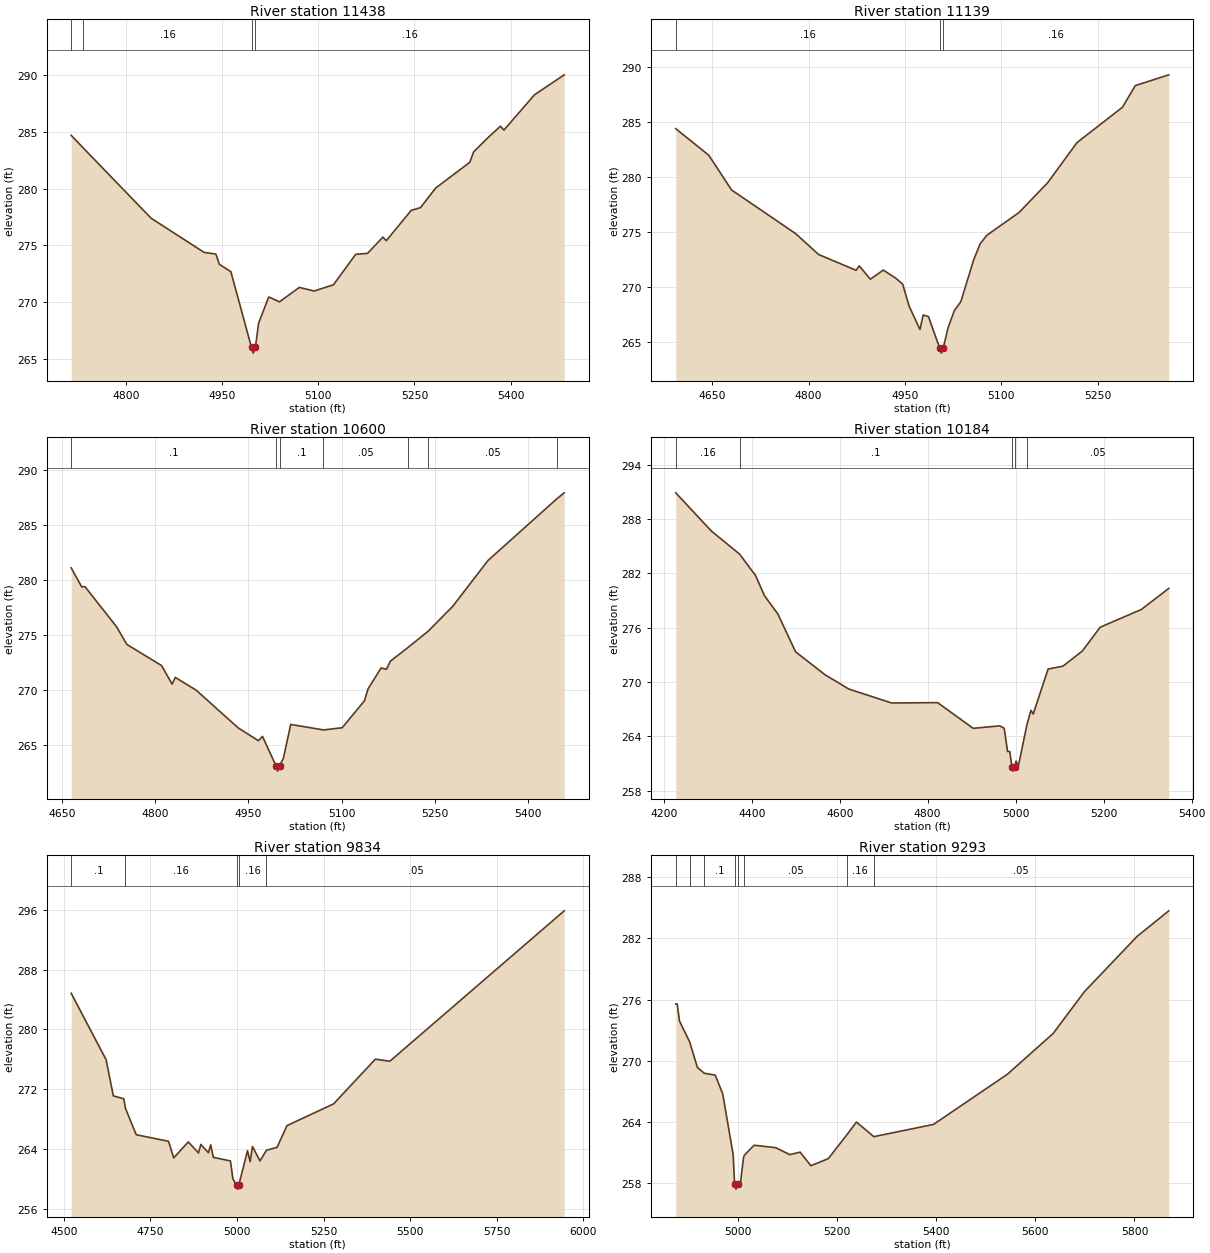
Type RM Length L Ch R = 1,11438,299,299,299
BEGIN DESCRIPTION:
ROBERTSON BRANCH 18.0
END DESCRIPTION:
XS GIS Cut Line= 2
      3587054.83     10275381.92      3586760.57     10274671.01
#Sta/Elev= 30
  4714.4  284.68  4733.4  283.56  4839.2  277.39  4921.7  274.39  4940.2  274.24
  4945.6  273.34  4963.6  272.69  4995.8  266.03  4998.5  265.53  5001.8  266.03
  5006.9  268.16  5022.7  270.47  5039.4  270.04  5070.5  271.31  5093.5  270.99
  5123.7  271.54  5158.4  274.22  5176.9  274.30  5200.8  275.73  5206.2  275.42
  5245.0  278.08  5259.4  278.32  5283.3  280.05  5336.5  282.31  5342.4  283.22
  5365.8  284.53  5384.3  285.48  5389.7  285.14  5437.5  288.25  5483.8  290.00
#Mann=4,-1,0
  4714.4     0.1       0  4733.4    0.16       0  4995.8    0.07       0
  5001.8    0.16       0
Bank Sta=4995.8,5001.8
Exp/Cntr=0.3,0.1

Type RM Length L Ch R = 1,11139,539,539,539
BEGIN DESCRIPTION:
Mapping XS baf70f7f
END DESCRIPTION:
XS GIS Cut Line= 2
      3587145.97     10275342.82      3587067.85     10274579.81
#Sta/Elev= 30
  4593.4  284.39  4644.8  281.98  4680.2  278.83  4779.6  274.88  4815.7  272.97
  4873.9  271.54  4878.9  271.94  4896.2  270.73  4916.3  271.56  4936.4  270.79
  4946.4  270.28  4956.5  268.28  4973.3  266.17  4978.3  267.48  4986.6  267.33
  5003.7  264.52  5006.5  264.02  5009.7  264.52  5016.8  266.28  5026.8  267.88
  5036.9  268.69  5057.0  272.51  5067.0  273.95  5077.6  274.73  5127.4  276.78
  5172.0  279.49  5217.8  283.14  5288.2  286.33  5308.3  288.30  5360.4  289.28
#Mann=3,-1,0
  4593.4    0.16       0  5003.7    0.07       0  5009.7    0.16       0
Bank Sta=5003.7,5009.7
Exp/Cntr=0.3,0.1

Type RM Length L Ch R = 1,10600,416,416,416
BEGIN DESCRIPTION:
ROBERTSON BRANCH 17.0
END DESCRIPTION:
XS GIS Cut Line= 3
      3587692.11     10275191.66      3587592.11     10274841.64
      3587342.13     10274491.68
#Sta/Elev= 30
  4664.6  281.09  4681.5  279.36  4686.7  279.39  4737.4  275.75  4754.3  274.12
  4810.2  272.20  4827.1  270.51  4832.3  271.12  4866.1  269.95  4933.7  266.52
  4966.2  265.36  4972.7  265.75  4994.4  263.09  4997.2  262.59  5000.4  263.09
  5006.5  263.79  5018.2  266.84  5070.9  266.34  5101.1  266.54  5136.8  268.98
  5142.9  270.09  5163.8  271.98  5172.4  271.86  5178.6  272.59  5207.7  273.87
  5239.9  275.34  5279.3  277.60  5335.9  281.76  5447.1  287.39  5458.7  287.92
#Mann=7,-1,0
  4664.6     0.1       0  4994.4    0.07       0  5000.4     0.1       0
  5070.9    0.05       0  5207.7     0.1       0  5239.9    0.05       0
  5447.1     0.1       0
Bank Sta=4994.4,5000.4
Exp/Cntr=0.3,0.1

Type RM Length L Ch R = 1,10184,350,350,350
BEGIN DESCRIPTION:
ROBERTSON BRANCH 16.0
END DESCRIPTION:
XS GIS Cut Line= 3
      3587742.11     10275391.60      3587842.11     10274641.64
      3587742.10     10274291.64
#Sta/Elev= 30
  4227.4  290.90  4308.1  286.69  4372.7  284.12  4408.9  281.75  4429.1  279.53
  4459.4  277.52  4499.7  273.34  4566.6  270.80  4620.8  269.22  4717.9  267.68
  4822.6  267.72  4903.3  264.88  4963.8  265.15  4973.9  264.89  4981.5  262.32
  4986.6  262.32  4991.4  260.65  4994.1  260.15  4997.4  260.65  5000.9  261.27
  5006.1  260.71  5025.4  265.24  5034.7  266.87  5039.9  266.46  5073.7  271.43
  5107.5  271.75  5151.7  273.43  5192.0  276.05  5285.6  278.01  5348.0  280.34
#Mann=5,-1,0
  4227.4    0.16       0  4372.7     0.1       0  4991.4    0.07       0
  4997.4     0.1       0  5025.4    0.05       0
Bank Sta=4991.4,4997.4
Exp/Cntr=0.3,0.1

Type RM Length L Ch R = 1,9834,541,541,541
BEGIN DESCRIPTION:
ROBERTSON BRANCH 15.0
END DESCRIPTION:
XS GIS Cut Line= 3
      3588442.12     10274991.67      3588242.11     10274691.64
      3587542.11     10273891.64
#Sta/Elev= 30
  4521.3  284.85  4622.0  275.96  4643.0  271.10  4673.1  270.71  4678.0  269.43
  4709.1  265.89  4802.3  265.01  4817.3  262.79  4859.4  264.93  4889.0  263.45
  4895.6  264.59  4917.5  263.48  4924.1  264.54  4931.7  262.86  4981.1  262.38
  4988.2  259.99  4999.0  259.10  5001.7  258.60  5005.0  259.10  5030.4  263.74
  5038.0  262.28  5044.7  264.32  5066.5  262.38  5085.0  263.81  5115.8  264.20
  5144.3  267.11  5279.1  270.03  5399.6  276.02  5441.4  275.74  5944.9  295.90
#Mann=5,-1,0
  4521.3     0.1       0  4678.0    0.16       0  4999.0    0.07       0
  5005.0    0.16       0  5085.0    0.05       0
Bank Sta=4999,5005
Exp/Cntr=0.3,0.1

Type RM Length L Ch R = 1,9293,617,617,617
BEGIN DESCRIPTION:
ROBERTSON BRANCH 14.0
END DESCRIPTION:
XS GIS Cut Line= 3
      3588692.12     10274691.66      3588592.11     10274541.64
      3587992.14     10273991.67
#Sta/Elev= 30
  4875.0  275.56  4878.0  275.56  4882.5  273.90  4903.0  271.86  4918.6  269.35
  4932.5  268.78  4954.6  268.60  4969.7  266.76  4990.7  260.82  4993.7  257.93
  4996.5  257.43  4999.7  257.93  5005.7  258.13  5011.7  260.55  5013.6  260.76
  5032.8  261.73  5076.6  261.49  5104.9  260.81  5125.9  261.05  5147.5  259.72
  5182.6  260.42  5219.4  262.71  5239.4  264.00  5274.4  262.57  5394.8  263.77
  5543.7  268.68  5635.9  272.67  5699.4  276.79  5805.4  282.19  5869.2  284.69
#Mann=8,-1,0
  4875.0     0.1       0  4903.0    0.16       0  4932.5     0.1       0
  4993.7    0.07       0  4999.7     0.1       0  5013.6    0.05       0
  5219.4    0.16       0  5274.4    0.05       0
Bank Sta=4993.7,4999.7
Exp/Cntr=0.3,0.1

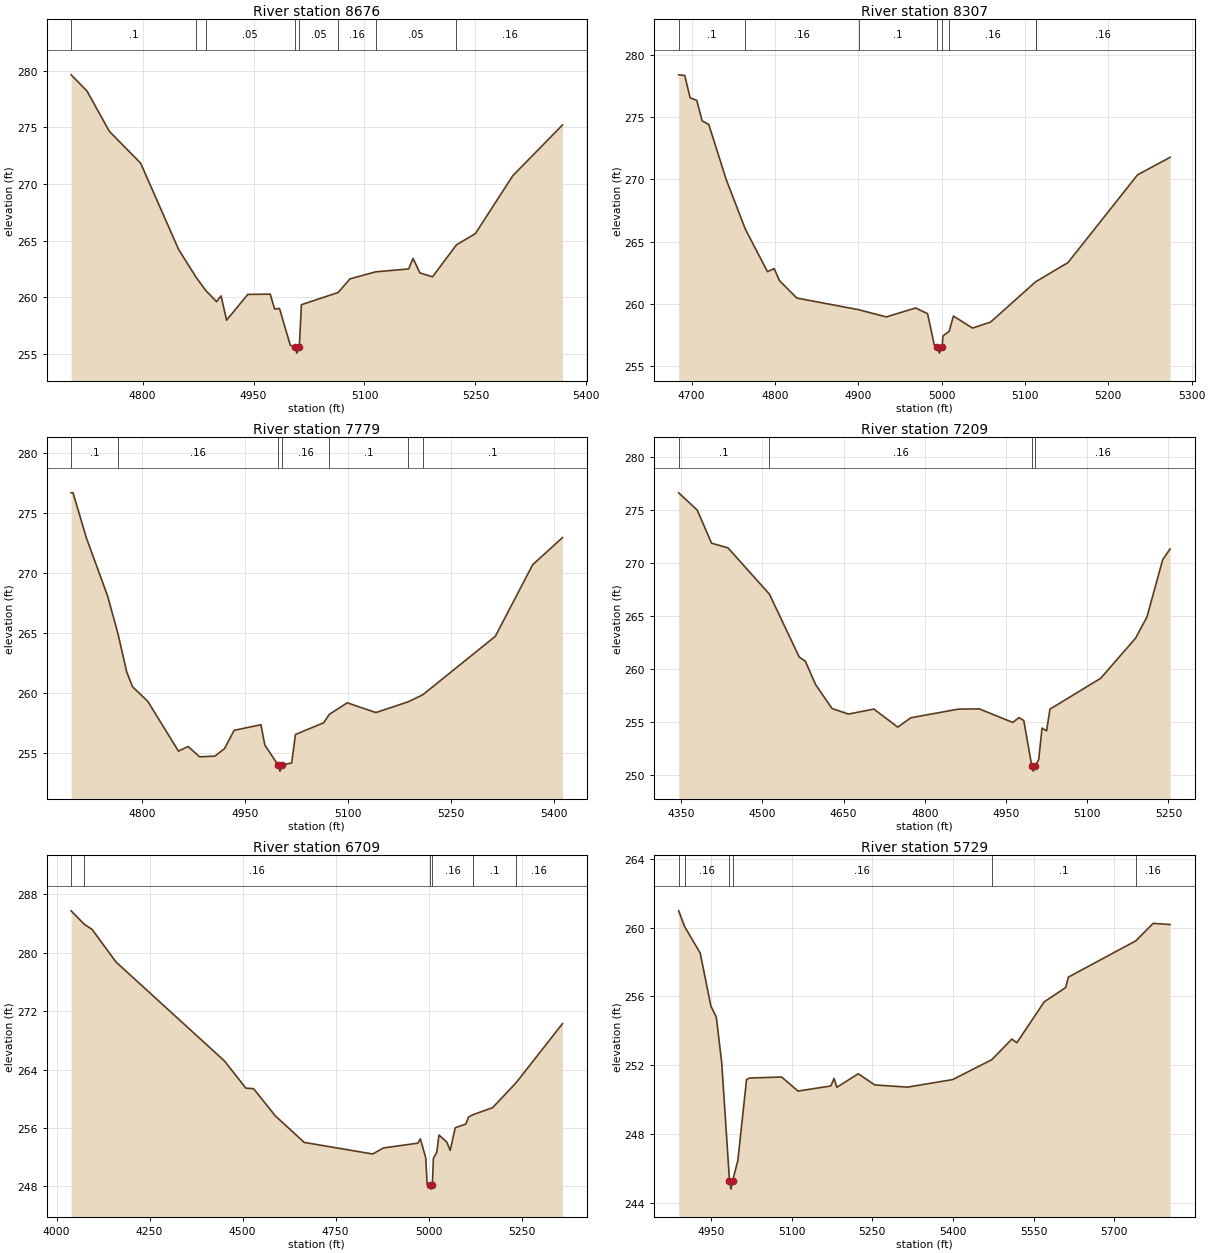
Type RM Length L Ch R = 1,8676,369,369,369
BEGIN DESCRIPTION:
ROBERTSON BRANCH 13.0
END DESCRIPTION:
XS GIS Cut Line= 3
      3589028.48     10274286.19      3588620.47     10274021.42
      3588594.66     10273845.09
#Sta/Elev= 30
  4703.2  279.64  4724.7  278.21  4755.0  274.64  4797.2  271.84  4848.6  264.21
  4872.4  261.74  4885.3  260.58  4900.0  259.60  4906.0  260.11  4913.5  257.96
  4942.2  260.24  4972.5  260.26  4978.5  258.94  4985.0  259.00  4999.6  255.76
  5005.8  255.55  5008.5  255.05  5011.8  255.55  5014.7  259.33  5064.5  260.41
  5080.3  261.61  5114.9  262.23  5159.7  262.49  5165.7  263.42  5174.9  262.14
  5192.0  261.79  5224.4  264.62  5250.0  265.61  5300.5  270.72  5367.8  275.21
#Mann=8,-1,0
  4703.2     0.1       0  4872.4    0.16       0  4885.3    0.05       0
  5005.8   0.035       0  5011.8    0.05       0  5064.5    0.16       0
  5114.9    0.05       0  5224.4    0.16       0
Bank Sta=5005.8,5011.8
Exp/Cntr=0.3,0.1

Type RM Length L Ch R = 1,8307,528,528,528
BEGIN DESCRIPTION:
ROBERTSON BRANCH 12.0
END DESCRIPTION:
XS GIS Cut Line= 3
      3589242.14     10274041.67      3588992.11     10273841.64
      3588742.07     10273741.63
#Sta/Elev= 30
  4684.6  278.44  4691.9  278.39  4698.3  276.59  4706.3  276.38  4712.7  274.73
  4720.7  274.44  4741.5  270.02  4764.6  265.99  4791.1  262.57  4799.1  262.82
  4805.5  261.85  4826.3  260.44  4900.6  259.50  4933.6  258.92  4968.8  259.64
  4983.2  259.18  4991.2  256.67  4994.6  256.50  4997.4  256.00  5000.6  256.50
  5001.6  257.38  5009.1  257.76  5014.2  258.99  5037.1  258.02  5058.7  258.50
  5113.3  261.78  5113.8  261.79  5151.6  263.30  5235.0  270.37  5274.1  271.79
#Mann=8,-1,0
  4684.6     0.1       0  4764.6    0.16       0  4900.6     0.1       0
  4994.6    0.07       0  5000.6     0.1       0  5009.1    0.16       0
  5113.3     0.1       0  5113.8    0.16       0
Bank Sta=4994.6,5000.6
Exp/Cntr=0.3,0.1

Type RM Length L Ch R = 1,7779,570,570,570
BEGIN DESCRIPTION:
ROBERTSON BRANCH 11.0
END DESCRIPTION:
XS GIS Cut Line= 3
      3589392.11     10273891.66      3589242.11     10273591.64
      3588892.12     10273441.65
#Sta/Elev= 30
  4696.1  276.67  4698.9  276.67  4718.5  272.90  4749.2  268.11  4764.3  264.98
  4777.2  261.77  4785.6  260.55  4807.9  259.33  4852.6  255.19  4866.6  255.58
  4883.4  254.72  4905.7  254.78  4919.7  255.40  4933.7  256.92  4972.8  257.39
  4978.4  255.71  4997.8  254.03  5000.5  253.53  5003.8  254.03  5017.6  254.21
  5023.1  256.58  5064.2  257.55  5072.4  258.25  5098.6  259.21  5140.3  258.40
  5187.2  259.29  5208.7  259.88  5314.4  264.74  5368.8  270.69  5412.3  272.95
#Mann=7,-1,0
  4696.1     0.1       0  4764.3    0.16       0  4997.8    0.07       0
  5003.8    0.16       0  5072.4     0.1       0  5187.2    0.16       0
  5208.7     0.1       0
Bank Sta=4997.8,5003.8
Exp/Cntr=0.3,0.1

Type RM Length L Ch R = 1,7209,500,500,500
BEGIN DESCRIPTION:
ROBERTSON BRANCH 10.0
END DESCRIPTION:
XS GIS Cut Line= 3
      3589542.11     10273991.68      3589442.11     10273341.64
      3589242.10     10273191.64
#Sta/Elev= 30
  4345.3  276.59  4379.5  274.97  4406.0  271.85  4436.4  271.41  4513.0  267.05
  4567.9  261.14  4579.3  260.74  4598.3  258.54  4628.6  256.29  4659.0  255.77
  4705.8  256.24  4750.0  254.54  4774.1  255.42  4861.3  256.23  4900.5  256.26
  4962.5  254.98  4973.9  255.44  4982.8  255.16  4997.5  250.90  5000.2  250.40
  5003.5  250.90  5010.3  251.47  5016.5  254.45  5024.9  254.19  5031.1  256.23
  5124.9  259.14  5189.4  262.92  5210.3  264.91  5239.4  270.30  5253.0  271.31
#Mann=4,-1,0
  4345.3     0.1       0  4513.0    0.16       0  4997.5    0.07       0
  5003.5    0.16       0
Bank Sta=4997.5,5003.5
Exp/Cntr=0.3,0.1

Type RM Length L Ch R = 1,6709,980,980,980
BEGIN DESCRIPTION:
ROBERTSON BRANCH 9.0
END DESCRIPTION:
XS GIS Cut Line= 3
      3590292.11     10273791.65      3589692.11     10273041.64
      3589392.13     10272841.66
#Sta/Elev= 30
  4039.0  285.76  4074.4  283.92  4095.8  283.19  4159.9  278.74  4451.2  265.20
  4508.8  261.47  4529.6  261.40  4587.3  257.71  4665.7  254.04  4849.8  252.45
  4878.6  253.28  4971.5  253.94  4977.9  254.53  4992.3  251.95  4996.3  248.21
  5004.0  248.14  5006.7  247.64  5010.0  248.14  5013.0  251.87  5022.0  252.66
  5028.0  255.05  5049.1  254.07  5058.1  252.95  5071.6  256.05  5100.1  256.55
  5107.6  257.52  5119.9  257.85  5172.2  258.80  5235.4  262.22  5360.0  270.31
#Mann=6,-1,0
  4039.0     0.1       0  4074.4    0.16       0  5004.0    0.07       0
  5010.0    0.16       0  5119.9     0.1       0  5235.4    0.16       0
Bank Sta=5004,5010
Exp/Cntr=0.3,0.1

Type RM Length L Ch R = 1,5729,1061,1061,1061
BEGIN DESCRIPTION:
ROBERTSON BRANCH 8.0
END DESCRIPTION:
XS GIS Cut Line= 3
      3590492.06     10272841.64      3590392.11     10272841.64
      3589592.10     10272691.64
#Sta/Elev= 30
  4890.1  260.99  4901.2  260.07  4930.1  258.53  4950.1  255.43  4960.1  254.80
  4970.1  252.15  4984.6  245.28  4987.3  244.78  4990.6  245.28  5000.2  246.46
  5016.3  251.16  5021.4  251.25  5081.6  251.31  5112.1  250.49  5173.2  250.79
  5179.1  251.23  5184.2  250.71  5224.1  251.50  5254.6  250.85  5315.6  250.72
  5399.6  251.16  5472.5  252.32  5509.8  253.52  5519.1  253.31  5570.0  255.69
  5609.8  256.52  5614.9  257.13  5740.2  259.24  5772.6  260.26  5804.0  260.19
#Mann=6,-1,0
  4890.1    0.05       0  4901.2    0.16       0  4984.6    0.07       0
  4990.6    0.16       0  5472.5     0.1       0  5740.2    0.16       0
Bank Sta=4984.6,4990.6
Exp/Cntr=0.3,0.1

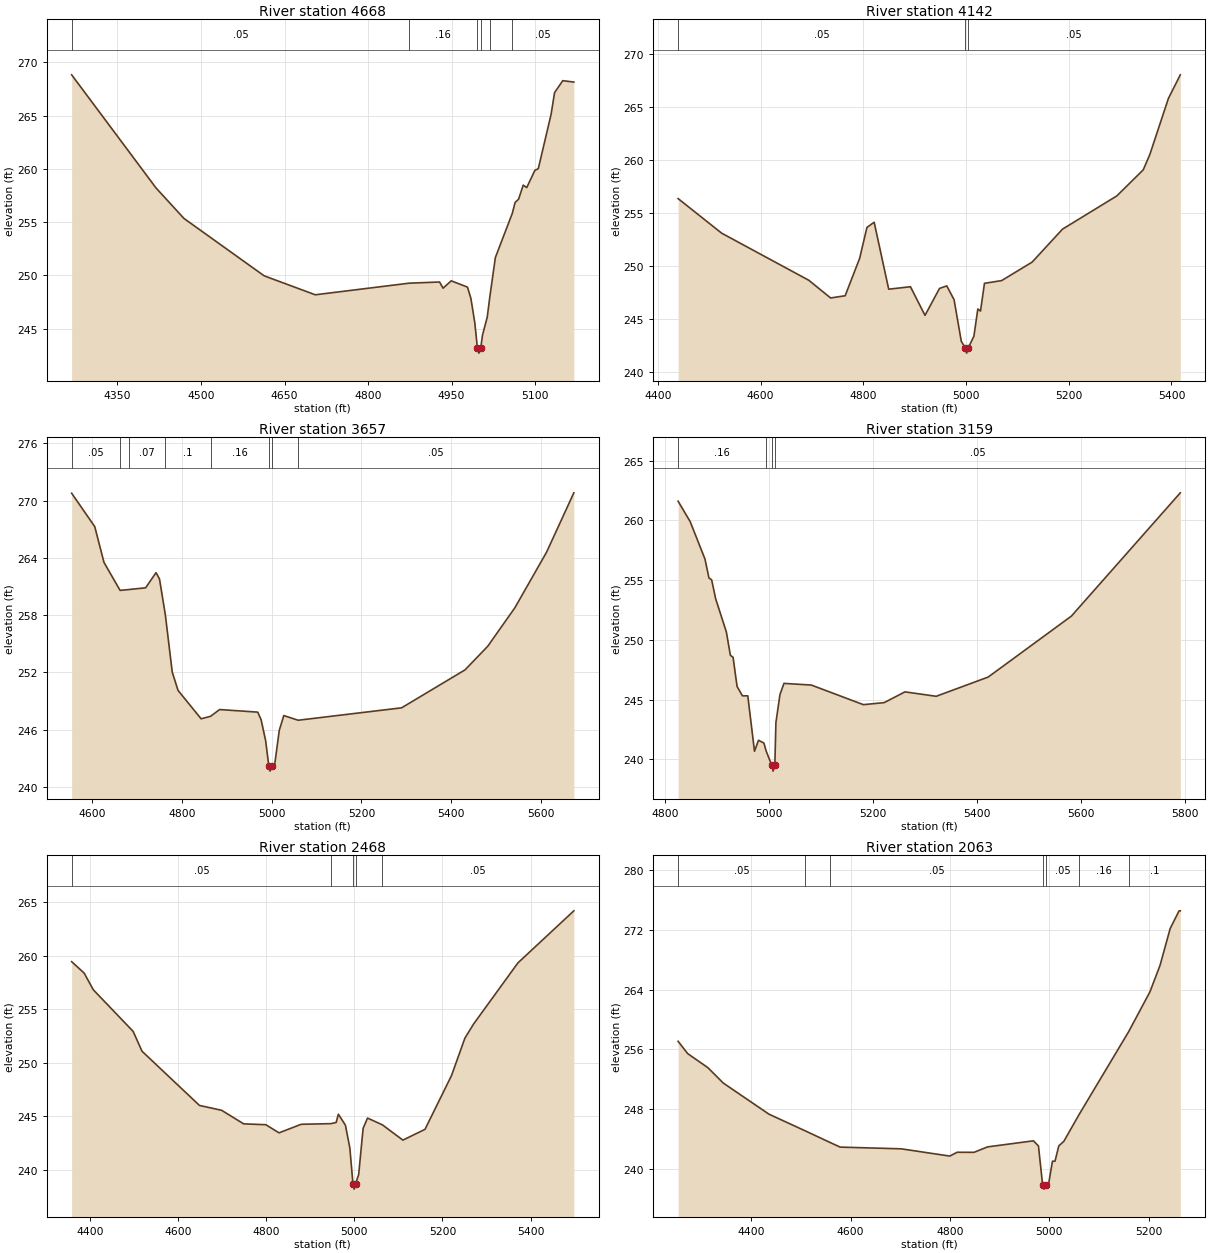
Type RM Length L Ch R = 1,4668,526,526,526
BEGIN DESCRIPTION:
ROBERTSON BRANCH 7.0
END DESCRIPTION:
XS GIS Cut Line= 2
      3590673.38     10272723.65      3589949.35     10272186.04
#Sta/Elev= 30
  4267.7  268.84  4419.3  258.21  4469.4  255.35  4613.4  249.96  4705.2  248.18
  4873.8  249.27  4928.4  249.38  4934.7  248.80  4949.3  249.49  4978.5  248.90
  4984.7  247.83  4991.7  245.53  4996.3  243.20  4999.1  242.70  5002.3  243.20
  5005.6  244.42  5014.0  246.08  5018.6  247.97  5028.6  251.68  5059.0  255.83
  5064.0  256.85  5070.3  257.16  5078.6  258.48  5084.9  258.25  5099.5  259.86
  5105.7  260.03  5128.7  265.14  5134.9  267.17  5149.6  268.29  5169.5  268.16
#Mann=6,-1,0
  4267.7    0.05       0  4873.8    0.16       0  4996.3    0.07       0
  5002.3    0.16       0  5018.6     0.1       0  5059.0    0.05       0
Bank Sta=4996.3,5002.3
Exp/Cntr=0.3,0.1

Type RM Length L Ch R = 1,4142,485,485,485
BEGIN DESCRIPTION:
ROBERTSON BRANCH 6.0
END DESCRIPTION:
XS GIS Cut Line= 3
      3590692.10     10272441.63      3590292.11     10272041.64
      3589892.09     10271941.64
#Sta/Elev= 30
  4439.2  256.33  4524.0  253.07  4693.7  248.63  4736.2  246.96  4764.5  247.17
  4792.7  250.69  4806.9  253.61  4821.0  254.10  4849.3  247.79  4891.7  248.02
  4920.0  245.32  4948.3  247.86  4962.4  248.10  4976.6  246.80  4990.7  242.87
  4998.3  242.26  5001.1  241.76  5004.3  242.26  5015.2  243.35  5022.9  245.92
  5028.1  245.73  5035.8  248.34  5069.3  248.60  5128.6  250.34  5187.8  253.45
  5293.5  256.58  5345.0  259.04  5357.9  260.49  5394.0  265.77  5417.2  268.00
#Mann=3,-1,0
  4439.2    0.05       0  4998.3    0.03       0  5004.3    0.05       0
Bank Sta=4998.3,5004.3
Exp/Cntr=0.3,0.1

Type RM Length L Ch R = 1,3657,498,498,498
BEGIN DESCRIPTION:
ROBERTSON BRANCH 5.0
END DESCRIPTION:
XS GIS Cut Line= 3
      3590942.08     10272041.64      3590542.11     10271941.64
      3589842.10     10271841.64
#Sta/Elev= 30
  4554.0  270.77  4605.5  267.27  4626.1  263.52  4662.0  260.59  4681.7  260.68
  4718.9  260.86  4742.1  262.45  4749.8  261.79  4762.8  258.05  4778.2  252.04
  4791.1  250.12  4842.6  247.14  4863.6  247.40  4883.8  248.11  4968.8  247.84
  4976.4  247.03  4986.5  244.83  4993.6  242.16  4996.3  241.66  4999.6  242.16
  5006.7  242.39  5016.8  245.93  5026.9  247.48  5058.9  246.99  5289.5  248.29
  5431.0  252.27  5481.5  254.74  5542.1  258.78  5612.8  264.61  5673.4  270.81
#Mann=8,-1,0
  4554.0    0.05       0  4662.0     0.1       0  4681.7    0.07       0
  4762.8     0.1       0  4863.6    0.16       0  4993.6    0.07       0
  4999.6    0.16       0  5058.9    0.05       0
Bank Sta=4993.6,4999.6
Exp/Cntr=0.3,0.1

Type RM Length L Ch R = 1,3159,691,691,691
BEGIN DESCRIPTION:
ROBERTSON BRANCH 4.0
END DESCRIPTION:
XS GIS Cut Line= 3
      3590742.13     10271591.65      3590542.11     10271541.64
      3589782.86     10271565.20
#Sta/Elev= 30
  4825.3  261.60  4848.5  259.89  4876.9  256.77  4884.6  255.18  4889.8  255.02
  4897.5  253.44  4918.1  250.66  4925.8  248.71  4931.0  248.54  4938.7  246.10
  4949.0  245.32  4959.3  245.32  4972.2  240.68  4979.9  241.60  4990.3  241.37
  4994.8  240.68  5005.3  239.52  5008.0  239.02  5011.3  239.52  5013.4  243.09
  5021.2  245.43  5028.9  246.36  5081.5  246.22  5181.6  244.58  5221.6  244.75
  5261.6  245.65  5321.6  245.28  5421.7  246.89  5581.7  251.99  5791.1  262.30
#Mann=4,-1,0
  4825.3    0.16       0  4994.8    0.05       0  5005.3    0.03       0
  5011.3    0.05       0
Bank Sta=5005.3,5011.3
Exp/Cntr=0.3,0.1

Type RM Length L Ch R = 1,2468,405,405,405
BEGIN DESCRIPTION:
Mapping XS a2b4b6e2
END DESCRIPTION:
XS GIS Cut Line= 2
      3590981.14     10271219.51      3589845.61     10271119.82
#Sta/Elev= 30
  4358.3  259.46  4386.7  258.39  4407.5  256.83  4497.9  252.94  4518.0  251.09
  4648.5  246.02  4698.6  245.57  4748.8  244.30  4799.0  244.22  4829.1  243.46
  4879.3  244.26  4947.1  244.32  4958.7  244.43  4963.7  245.20  4979.7  244.18
  4989.8  242.04  4996.8  238.70  4999.5  238.20  5002.8  238.70  5009.8  239.56
  5019.9  243.88  5029.9  244.84  5063.6  244.21  5110.2  242.78  5160.4  243.79
  5220.6  248.82  5250.8  252.30  5270.8  253.64  5371.2  259.34  5498.2  264.21
#Mann=5,-1,0
  4358.3    0.05       0  4947.1    0.16       0  4996.8    0.07       0
  5002.8    0.16       0  5063.6    0.05       0
Bank Sta=4996.8,5002.8
Exp/Cntr=0.3,0.1

Type RM Length L Ch R = 1,2063,210,210,210
BEGIN DESCRIPTION:
ROBERTSON BRANCH 3.0
END DESCRIPTION:
XS GIS Cut Line= 3
      3591180.87     10270954.76      3590442.11     10270791.64
      3590192.12     10270741.64
#Sta/Elev= 30
  4252.5  257.08  4271.7  255.44  4312.7  253.54  4343.4  251.50  4435.6  247.33
  4509.0  245.09  4558.9  243.54  4578.9  242.93  4701.8  242.70  4799.7  241.73
  4814.5  242.24  4848.5  242.23  4875.9  242.96  4968.1  243.77  4978.3  243.08
  4986.8  237.81  4989.5  237.31  4992.8  237.81  4998.8  238.04  5006.5  241.04
  5011.6  241.04  5019.3  243.10  5029.5  243.71  5060.1  247.28  5160.0  258.37
  5202.8  263.69  5223.2  267.24  5243.6  272.16  5261.5  274.53  5264.0  274.53
#Mann=7,-1,0
  4252.5    0.05       0  4509.0    0.16       0  4558.9    0.05       0
  4986.8    0.03       0  4992.8    0.05       0  5060.1    0.16       0
  5160.0     0.1       0
Bank Sta=4986.8,4992.8
Exp/Cntr=0.3,0.1

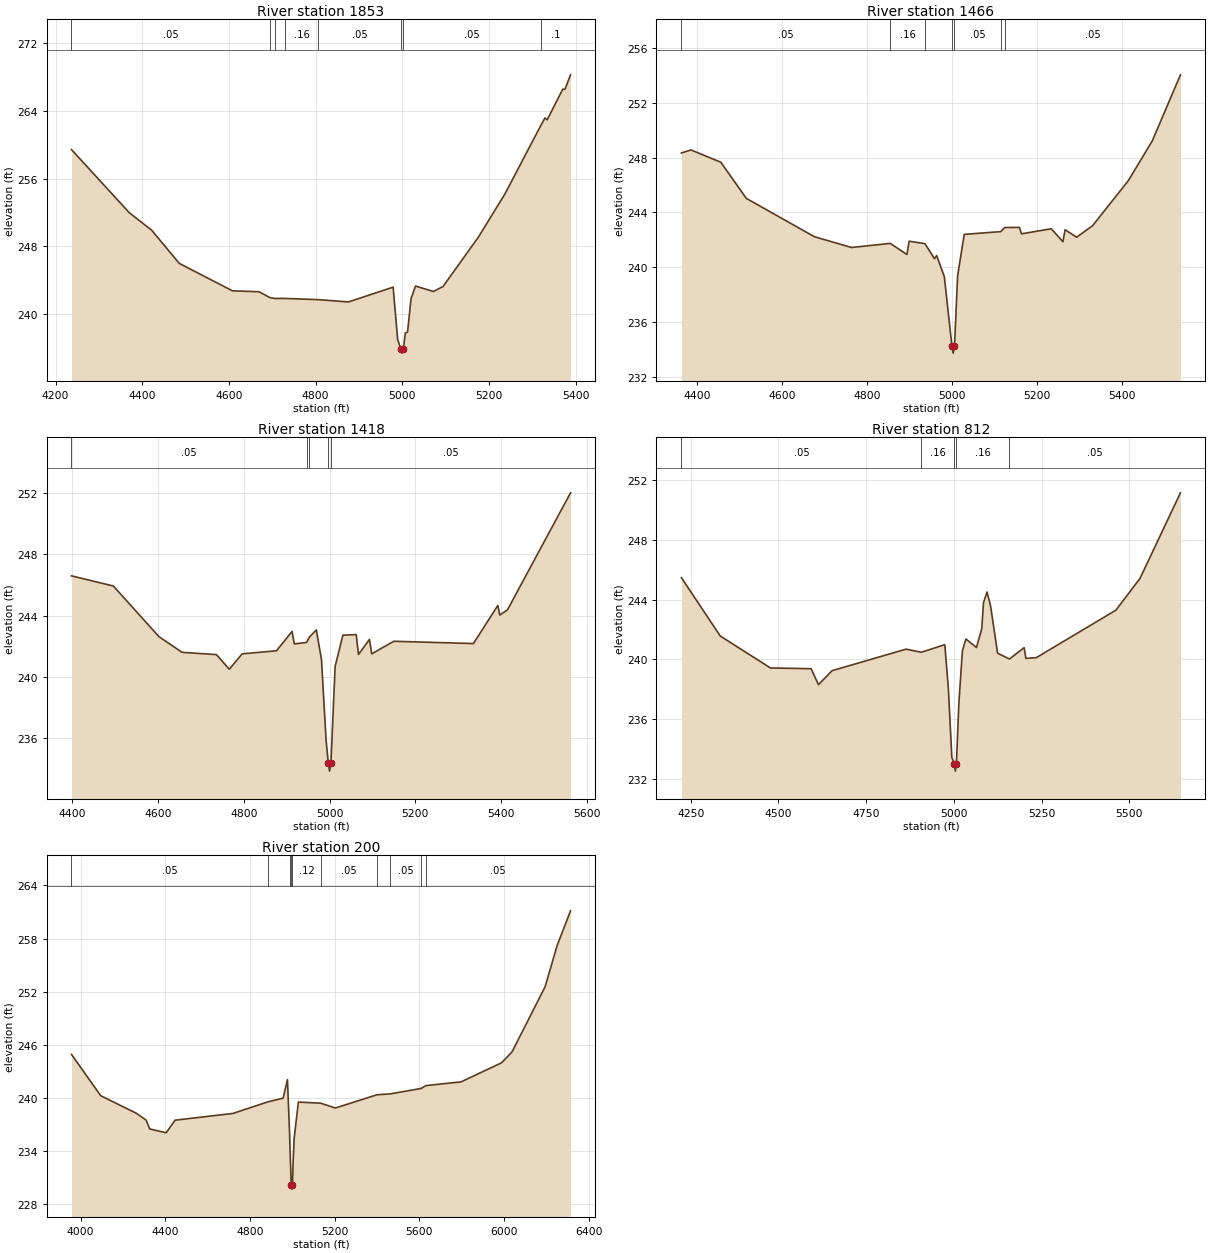
Type RM Length L Ch R = 1,1853,387,387,387
BEGIN DESCRIPTION:
Mapping XS 7a1aa013
END DESCRIPTION:
XS GIS Cut Line= 2
      3591341.41     10270857.09      3590225.45     10270573.23
#Sta/Elev= 30
  4236.8  259.41  4370.2  251.98  4421.8  249.92  4485.5  246.01  4608.2  242.78
  4669.5  242.67  4694.6  241.98  4705.3  241.88  4730.3  241.88  4806.1  241.74
  4875.8  241.47  4979.0  243.21  4989.3  237.08  4996.6  235.94  4999.4  235.44
  5002.6  235.94  5007.1  237.82  5012.2  237.91  5020.3  241.86  5030.6  243.34
  5071.9  242.70  5094.1  243.29  5175.9  249.12  5237.0  254.20  5320.5  262.33
  5329.3  263.14  5334.4  262.92  5370.2  266.52  5375.4  266.52  5388.3  268.22
#Mann=8,-1,0
  4236.8    0.05       0  4694.6    0.16       0  4705.3    0.05       0
  4730.3    0.16       0  4806.1    0.05       0  4996.6    0.03       0
  5002.6    0.05       0  5320.5     0.1       0
Bank Sta=4996.6,5002.6
Exp/Cntr=0.3,0.1

Type RM Length L Ch R = 1,1466,48,48,48
BEGIN DESCRIPTION:
Mapping XS 83201785
END DESCRIPTION:
XS GIS Cut Line= 4
      3591484.89     10270569.45      3590998.55     10270590.20
      3590458.18     10270420.93      3590335.75     10270418.78
#Sta/Elev= 30
  4362.6  248.34  4385.4  248.56  4455.5  247.66  4515.5  245.02  4675.7  242.22
  4763.4  241.43  4854.5  241.73  4893.8  240.92  4899.0  241.89  4936.3  241.71
  4958.7  240.61  4963.9  240.84  4981.9  239.30  4999.8  234.21  5002.6  233.71
  5005.8  234.21  5013.3  239.38  5028.8  242.39  5114.7  242.59  5124.3  242.89
  5158.6  242.90  5163.8  242.43  5233.9  242.80  5261.2  241.85  5266.4  242.73
  5293.6  242.18  5331.3  243.03  5415.6  246.33  5471.7  249.22  5538.1  254.05
#Mann=7,-1,0
  4362.6    0.05       0  4854.5    0.16       0  4936.3    0.05       0
  4999.8    0.03       0  5005.8    0.05       0  5114.7    0.16       0
  5124.3    0.05       0
Bank Sta=4999.8,5005.8
Exp/Cntr=0.3,0.1

Type RM Length L Ch R = 1,1418,606,606,606
BEGIN DESCRIPTION:
Mapping XS 3f6a94ed
END DESCRIPTION:
XS GIS Cut Line= 4
      3591479.53     10270515.52      3590983.35     10270542.46
      3590508.09     10270375.36      3590345.08     10270375.36
#Sta/Elev= 30
  4398.2  246.59  4495.8  245.93  4602.2  242.63  4656.0  241.61  4736.1  241.46
  4766.2  240.51  4796.2  241.51  4876.3  241.71  4912.5  242.97  4917.8  242.16
  4946.4  242.25  4952.9  242.60  4969.1  243.07  4981.2  241.13  4991.8  235.91
  4997.1  234.37  4999.9  233.87  5003.1  234.37  5013.0  240.69  5031.1  242.73
  5062.1  242.76  5067.4  241.47  5093.0  242.45  5098.3  241.51  5149.7  242.33
  5335.5  242.18  5392.2  244.66  5397.0  244.04  5414.9  244.38  5561.9  252.00
#Mann=5,-1,0
  4398.2    0.05       0  4946.4    0.16       0  4952.9    0.05       0
  4997.1    0.03       0  5003.1    0.05       0
Bank Sta=4997.1,5003.1
Exp/Cntr=0.3,0.1

Type RM Length L Ch R = 1,812,612,612,612
BEGIN DESCRIPTION:
Mapping XS 3e125268
END DESCRIPTION:
XS GIS Cut Line= 4
      3591520.67     10270457.19      3591291.51     10270129.06
      3590567.55     10270188.96      3590299.31     10270313.96
#Sta/Elev= 30
  4223.3  245.48  4334.0  241.57  4477.1  239.43  4593.1  239.38  4614.0  238.31
  4653.0  239.25  4863.8  240.69  4907.0  240.48  4974.1  240.99  4984.2  238.09
  4994.2  233.44  5001.2  233.02  5004.0  232.52  5007.2  233.02  5014.3  237.11
  5024.3  240.57  5034.3  241.37  5064.4  240.80  5079.4  242.05  5084.5  243.81
  5094.5  244.52  5104.6  243.59  5124.6  240.42  5158.4  240.03  5200.3  240.79
  5205.3  240.07  5235.0  240.12  5461.8  243.30  5530.4  245.42  5645.9  251.16
#Mann=5,-1,0
  4223.3    0.05       0  4907.0    0.16       0  5001.2    0.07       0
  5007.2    0.16       0  5158.4    0.05       0
Bank Sta=5001.2,5007.2
Exp/Cntr=0.3,0.1

Type RM Length L Ch R = 1,200,0,0,0
BEGIN DESCRIPTION:
ROBERTSON BRANCH 1.0
END DESCRIPTION:
XS GIS Cut Line= 4
      3591708.73     10270468.26      3591522.11     10269878.01
      3590719.16     10269682.70      3590137.56     10270385.82
#Sta/Elev= 30
  3956.6  244.93  4094.7  240.27  4261.5  238.31  4309.6  237.51  4326.1  236.52
  4404.0  236.09  4446.0  237.51  4719.7  238.27  4886.1  239.59  4956.4  239.99
  4977.0  242.08  4986.7  236.25  4994.6  230.23  4997.4  229.73  5000.6  230.23
  5003.6  232.77  5008.8  235.50  5028.5  239.55  5133.4  239.43  5203.4  238.88
  5400.6  240.38  5463.5  240.48  5608.7  241.09  5631.0  241.41  5797.0  241.83
  5988.4  243.98  6037.9  245.21  6194.2  252.56  6251.6  257.24  6314.5  261.13
#Mann=10,-1,0
  3956.6    0.05       0  4886.1    0.16       0  4986.7    0.12       0
  4994.6    0.07       0  5000.6    0.12       0  5133.4    0.05       0
  5400.6    0.16       0  5463.5    0.05       0  5608.7    0.16       0
  5631.0    0.05       0
Bank Sta=4994.6,5000.6
Exp/Cntr=0.3,0.1

Chan Stop Cuts=-1