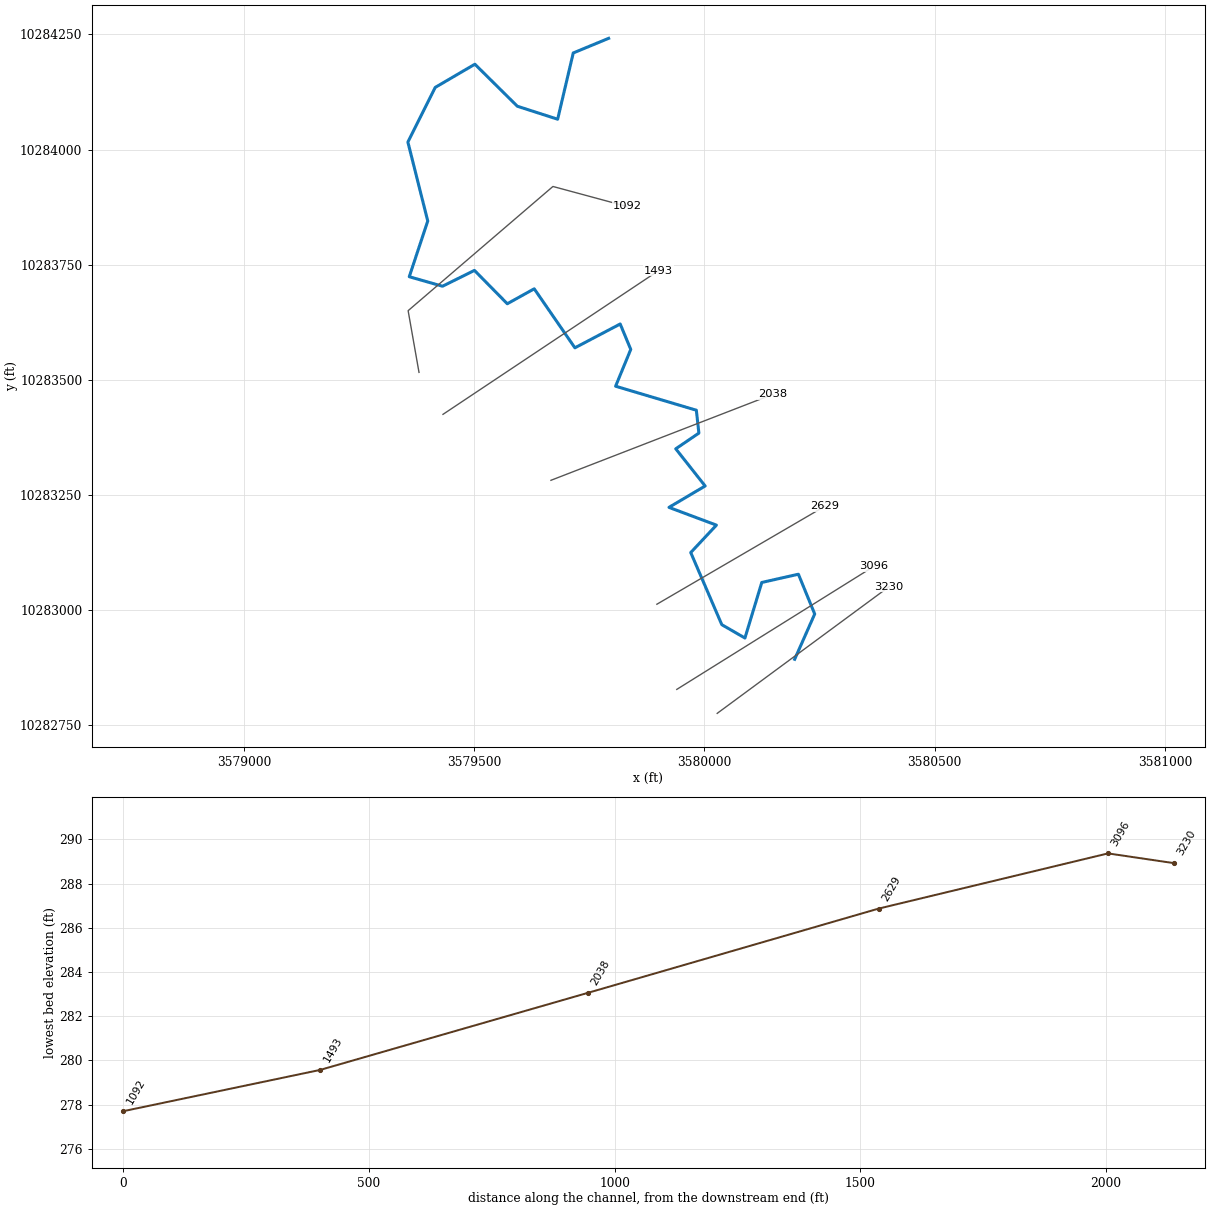
--- SANDCREEKTRIB11.prj (project) ---

Proj Title=SAND CREEK TRIB 11
Current Plan=p01
Default Exp/Contr=0.3,0.1
English Units
Geom File=g01
Flow File=f01
Plan File=p01
Y Axis Title=Elevation
X Axis Title(PF)=Main Channel Distance
X Axis Title(XS)=Station
BEGIN DESCRIPTION:
UNT04786 IN WICK
END DESCRIPTION:
DSS Export Rating Curves= 0
DSS Export Rating Curve Sorted= 0
DSS Export Volume Flow Curves= 0
DXF OffsetX= 0
DXF OffsetY= 0
DXF ScaleX= 1
DXF ScaleY= 10

--- SANDCREEKTRIB11.p01 (plan) ---

Plan Title=Multiple Run
Short Identifier=Multiple
Geom File=g01
Flow File=f01
Subcritical Flow
K Sum by GR= 0
Std Step Tol= 0.01
Critical Tol= 0.01
Num of Std Step Trials= 20
Max Error Tol= 0.3
Flow Tol Ratio= 0.001
Split Flow NTrial= 30
Split Flow Tol= 0.02
Split Flow Ratio= 0.02
Log Output Level= 0
Friction Slope Method= 1
Unsteady Friction Slope Method= 2
Unsteady Bridges Friction Slope Method= 1
Parabolic Critical Depth
Global Vel Dist=  1 , 1 , 1
Global Log Level= 0
CheckData=True
Encroach Param= -1, 0, 0, 0
BEGIN DESCRIPTION:
Multiple Run
END DESCRIPTION:

--- SANDCREEKTRIB11.f01 (steady flow) ---

Flow Title=Multiple
Program Version=4.10
Number of Profiles= 7
Profile Names=10-year,25-year,50-year,1pct_min,100-year,1pct_plu,500-year
River Rch & RM=UNT04786 IN WICK,Reach-1         ,3230
     208     263     304     259     350     474     465
River Rch & RM=SANDCREEKTRIB11,Reach-1         ,3230
     208     263     304     259     350     474     465
Boundary for River Rch & Prof#=SANDCREEKTRIB11,Reach-1         , 1
Up Type= 0
Dn Type= 3
Dn Slope=0.005
Boundary for River Rch & Prof#=SANDCREEKTRIB11,Reach-1         , 2
Up Type= 0
Dn Type= 3
Dn Slope=0.005
Boundary for River Rch & Prof#=SANDCREEKTRIB11,Reach-1         , 3
Up Type= 0
Dn Type= 3
Dn Slope=0.005
Boundary for River Rch & Prof#=SANDCREEKTRIB11,Reach-1         , 4
Up Type= 0
Dn Type= 3
Dn Slope=0.005
Boundary for River Rch & Prof#=SANDCREEKTRIB11,Reach-1         , 5
Up Type= 0
Dn Type= 3
Dn Slope=0.005
Boundary for River Rch & Prof#=SANDCREEKTRIB11,Reach-1         , 6
Up Type= 0
Dn Type= 3
Dn Slope=0.005
Boundary for River Rch & Prof#=SANDCREEKTRIB11,Reach-1         , 7
Up Type= 0
Dn Type= 3
Dn Slope=0.005
DSS Import GetInterval= 0
DSS Import GetPeak= 0
DSS Import FillOption= 0

--- SANDCREEKTRIB11.g01 (geometry) ---

Geom Title=Existing Conditions
Program Version=4.10

River Reach=SANDCREEKTRIB11 ,Reach-1
Reach XY= 30
      3580196.09     10282893.35      3580239.59     10282991.63
       3580204.2     10283078.04      3580124.68     10283060.12
       3580088.1     10282939.47      3580037.84     10282968.52
      3579970.44     10283125.09      3580026.18     10283184.63
      3579923.13     10283223.18      3580001.69     10283269.62
      3579937.89     10283350.35      3579988.12     10283384.46
      3579982.59     10283434.12      3579807.26     10283486.27
      3579840.18     10283566.18      3579817.26     10283621.37
      3579718.91     10283569.64      3579630.57     10283697.78
      3579572.11     10283665.29      3579500.77     10283737.76
      3579431.48     10283703.38      3579359.25     10283724.05
      3579399.37     10283844.97      3579356.23     10284016.39
      3579415.64      10284135.1      3579501.74     10284185.45
      3579593.86     10284094.23      3579681.43     10284066.04
      3579715.31     10284209.86      3579792.11     10284241.64

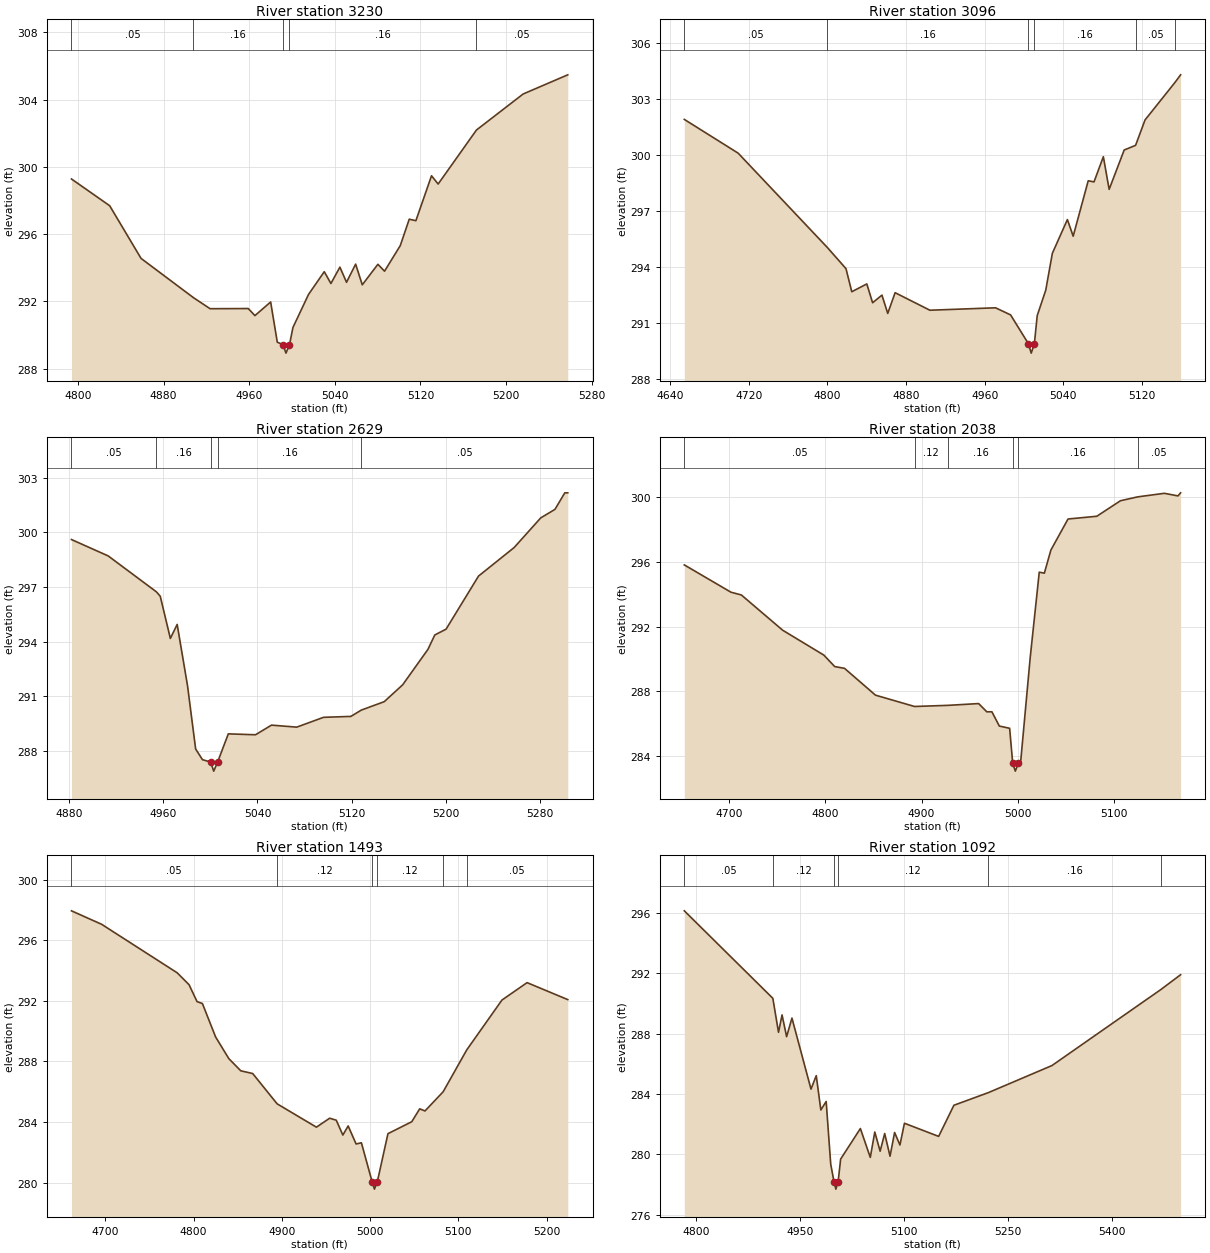
Type RM Length L Ch R = 1 ,3230    ,134,134,134
BEGIN DESCRIPTION:
UNT04786 IN WICK 4.0
END DESCRIPTION:
XS GIS Cut Line= 2
      3580027.84     10282775.88      3580401.08     10283051.04
#Sta/Elev= 30
    4794  299.28  4829.7  297.69    4859  294.56  4907.9  292.23  4923.5  291.57
  4959.2  291.58  4965.4  291.16  4980.1  291.97  4986.3  289.58  4991.7  289.43
  4994.4  288.93  4997.7  289.43  5000.9  290.45  5015.5  292.42  5030.2  293.77
  5036.4  293.07  5044.8  294.04    5051  293.14  5059.5  294.22  5065.7  292.99
  5080.3  294.21  5086.5   293.8  5101.2  295.32  5109.6  296.89  5115.8   296.8
  5130.4  299.47  5136.6  298.98  5172.4  302.19    5216  304.33  5257.7  305.47
#Mann= 5 ,-1 , 0
    4794     .05       0  4907.9     .16       0  4991.7     .07       0
  4997.7     .16       0  5172.4     .05       0
Bank Sta=4991.7,4997.7
XS Rating Curve= 0 ,0
Exp/Cntr=0.3,0.1

Type RM Length L Ch R = 1 ,3096    ,467,467,467
BEGIN DESCRIPTION:
Mapping XS aedaae04
END DESCRIPTION:
XS GIS Cut Line= 2
      3579940.11     10282827.93       3580368.5     10283095.35
#Sta/Elev= 30
  4654.4   301.9  4709.2  300.09    4800  295.03  4818.9   293.9  4824.8  292.66
  4840.1  293.08    4846  292.07  4855.5  292.48  4861.4   291.5  4868.9  292.61
  4904.3  291.67  4971.1   291.8  4986.4  291.42  5004.6  289.87  5007.4  289.37
  5010.6  289.87  5013.5  291.38  5022.2  292.75  5028.9  294.72  5044.2  296.53
  5050.1  295.64  5065.4  298.61  5071.3  298.55  5080.8   299.9  5086.7  298.15
    5102  300.26  5113.6  300.51  5123.2  301.87  5153.8  303.89  5159.4  304.29
#Mann= 6 ,-1 , 0
  4654.4     .05       0    4800     .16       0  5004.6     .07       0
  5010.6     .16       0  5113.6     .05       0  5153.8      .1       0
Bank Sta=5004.6,5010.6
XS Rating Curve= 0 ,0
Exp/Cntr=0.3,0.1

Type RM Length L Ch R = 1 ,2629    ,591,591,591
BEGIN DESCRIPTION:
Mapping XS a8222a40
END DESCRIPTION:
XS GIS Cut Line= 2
      3579896.89     10283012.87      3580261.49     10283225.55
#Sta/Elev= 30
  4881.8  299.61    4913  298.71  4954.1  296.73  4957.3  296.49  4965.9  294.17
  4971.7  294.94  4980.5  291.57  4987.4  288.09  4993.2   287.5  5000.1  287.37
  5002.8  286.87  5006.1  287.37  5015.2  288.92  5038.3  288.87  5051.9   289.4
  5073.4  289.29  5096.2  289.83  5119.4  289.88  5128.4  290.23  5147.8  290.69
  5163.5  291.62    5185  293.57  5190.8  294.36  5200.4  294.68    5228   297.6
  5258.3  299.17  5280.9   300.8    5293  301.27  5301.4  302.18  5303.9  302.18
#Mann= 5 ,-1 , 0
  4881.8     .05       0  4954.1     .16       0  5000.1     .07       0
  5006.1     .16       0  5128.4     .05       0
Bank Sta=5000.1,5006.1
XS Rating Curve= 0 ,0
Exp/Cntr=0.3,0.1

Type RM Length L Ch R = 1 ,2038    ,545,545,545
BEGIN DESCRIPTION:
UNT04786 IN WICK 3.0
END DESCRIPTION:
XS GIS Cut Line= 2
      3579666.85     10283281.96      3580147.82     10283468.29
#Sta/Elev= 30
  4653.4  295.82  4701.9  294.13  4712.7  293.96  4755.6  291.78  4798.4  290.24
  4809.7  289.53  4819.9  289.42  4852.1  287.76  4892.7  287.06  4927.5  287.13
  4959.3  287.24  4967.8  286.73  4973.1  286.73  4980.8  285.85  4991.5  285.71
  4994.7  283.56  4997.4  283.06  5000.7  283.56  5003.1  283.72  5012.9  290.09
  5022.3  295.37  5027.6  295.31  5034.4  296.74  5052.2  298.66  5082.1  298.83
  5106.7  299.79  5124.6  300.03  5152.3  300.25  5166.5  300.09  5169.2  300.28
#Mann= 6 ,-1 , 0
  4653.4     .05       0  4892.7     .12       0  4927.5     .16       0
  4994.7     .07       0  5000.7     .16       0  5124.6     .05       0
Bank Sta=4994.7,5000.7
XS Rating Curve= 0 ,0
Exp/Cntr=0.3,0.1

Type RM Length L Ch R = 1 ,1493    ,401,401,401
BEGIN DESCRIPTION:
UNT04786 IN WICK 2.0
END DESCRIPTION:
XS GIS Cut Line= 2
      3579432.44     10283425.17      3579900.47     10283737.19
#Sta/Elev= 30
  4661.5  297.94  4695.7  297.05  4781.3  293.85  4794.8  293.06  4803.8  291.95
  4809.9  291.82  4824.9  289.61  4839.9  288.18  4853.4  287.38  4866.9   287.2
  4894.6   285.2  4939.1  283.66  4954.1  284.25  4961.6  284.12  4969.1  283.14
  4975.1  283.74  4984.1  282.55  4990.1  282.63  5002.2  280.07  5004.9  279.57
  5008.2  280.07  5020.2  283.23  5047.2  284.02  5056.2  284.87  5062.2  284.73
  5082.8     286  5109.5  288.76  5149.4  292.05  5177.9   293.2    5224  292.08
#Mann= 6 ,-1 , 0
  4661.5     .05       0  4894.6     .12       0  5002.2     .07       0
  5008.2     .12       0  5082.8     .16       0  5109.5     .05       0
Bank Sta=5002.2,5008.2
XS Rating Curve= 0 ,0
Exp/Cntr=0.3,0.1

Type RM Length L Ch R = 1 ,1092    ,0,0,0
BEGIN DESCRIPTION:
UNT04786 IN WICK 1.0
END DESCRIPTION:
XS GIS Cut Line= 4
      3579380.39     10283516.31      3579356.76     10283650.28
      3579671.19     10283919.98      3579831.64     10283876.61
#Sta/Elev= 30
  4782.7  296.12  4910.5  290.33  4918.7  288.08  4923.8  289.23  4930.4  287.79
  4938.1  289.02  4965.6  284.32  4973.2  285.21  4979.8  282.94  4987.5   283.5
  4994.1  279.34  4998.8   278.2  5001.5   277.7  5004.8   278.2  5008.4  279.69
  5036.9  281.71  5051.2   279.8  5057.7  281.48  5065.4  280.21    5072  281.38
  5079.7  279.88  5086.3  281.45    5094  280.62  5100.5  282.06  5149.9  281.19
  5171.9  283.25  5221.8  284.09  5313.5  285.88  5470.4   290.9  5499.2  291.89
#Mann= 6 ,-1 , 0
  4782.7     .05       0  4910.5     .12       0  4998.8     .07       0
  5004.8     .12       0  5221.8     .16       0  5470.4     .05       0
Bank Sta=4998.8,5004.8
XS Rating Curve= 0 ,0
Exp/Cntr=0.3,0.1

Chan Stop Cuts=-1
Use User Specified Reach Order=0
Composite Channel Slope=5