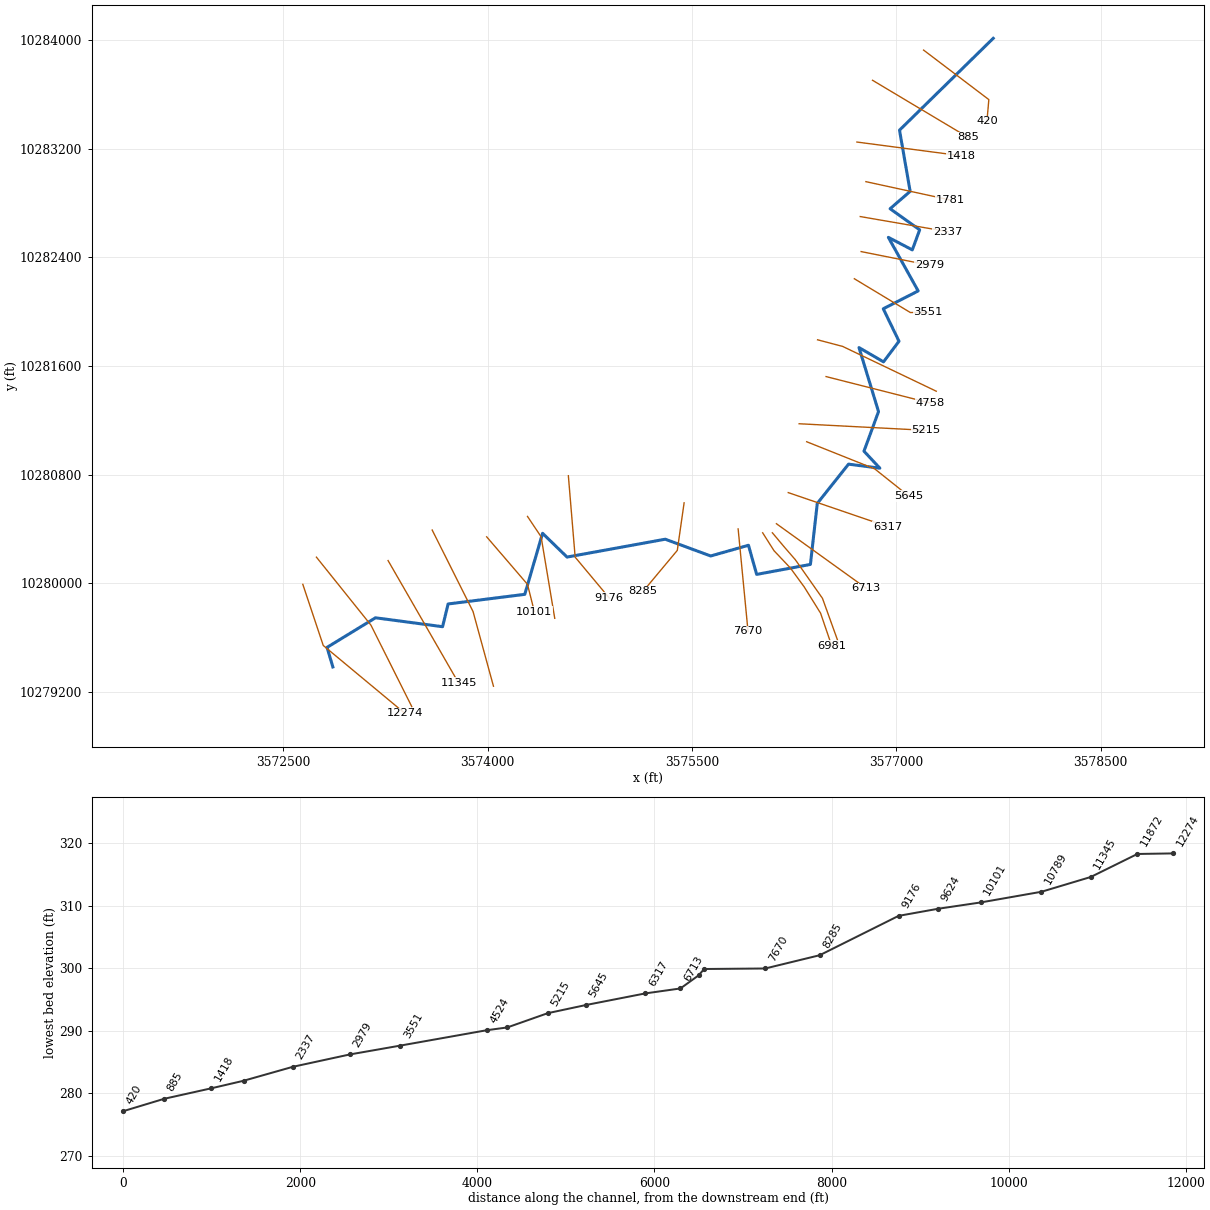
--- SANDCREEKTRIB13.prj (project) ---

Proj Title=SAND CREEK TRIB 13
Current Plan=p01
Default Exp/Contr=0.3,0.1
English Units
Geom File=g01
Flow File=f01
Plan File=p01
Y Axis Title=Elevation
X Axis Title(PF)=Main Channel Distance
X Axis Title(XS)=Station
BEGIN DESCRIPTION:
UNT0459 IN WICK
END DESCRIPTION:
DSS Export Rating Curves= 0
DSS Export Rating Curve Sorted= 0
DSS Export Volume Flow Curves= 0
DXF OffsetX= 0
DXF OffsetY= 0
DXF ScaleX= 1
DXF ScaleY= 10

--- SANDCREEKTRIB13.p01 (plan) ---

Plan Title=Multiple Run
Short Identifier=Multiple
Geom File=g01
Flow File=f01
Subcritical Flow
K Sum by GR= 0
Std Step Tol= 0.01
Critical Tol= 0.01
Num of Std Step Trials= 20
Max Error Tol= 0.3
Flow Tol Ratio= 0.001
Split Flow NTrial= 30
Split Flow Tol= 0.02
Split Flow Ratio= 0.02
Log Output Level= 0
Friction Slope Method= 1
Unsteady Friction Slope Method= 2
Unsteady Bridges Friction Slope Method= 1
Parabolic Critical Depth
Global Vel Dist=  1 , 1 , 1
Global Log Level= 0
CheckData=True
Encroach Param= -1, 0, 0, 0
BEGIN DESCRIPTION:
Multiple Run
END DESCRIPTION:

--- SANDCREEKTRIB13.f01 (steady flow) ---

Flow Title=Multiple
Program Version=4.10
Number of Profiles= 7
Profile Names=10-year,25-year,50-year,1pct_min,100-year,1pct_plu,500-year
River Rch & RM=UNT0459 IN WICK,Reach-1         ,12274
     555     745     899     795    1076    1455    1542
River Rch & RM=UNT0459 IN WICK,Reach-1         ,5645
     618     831    1005     889    1203    1627    1728
River Rch & RM=SANDCREEKTRIB13,Reach-1         ,12274
     555     745     899     795    1076    1455    1542
River Rch & RM=SANDCREEKTRIB13,Reach-1         ,5645
     618     831    1005     889    1203    1627    1728
Boundary for River Rch & Prof#=SANDCREEKTRIB13,Reach-1         , 1
Up Type= 0
Dn Type= 3
Dn Slope=0.005
Boundary for River Rch & Prof#=SANDCREEKTRIB13,Reach-1         , 2
Up Type= 0
Dn Type= 3
Dn Slope=0.005
Boundary for River Rch & Prof#=SANDCREEKTRIB13,Reach-1         , 3
Up Type= 0
Dn Type= 3
Dn Slope=0.005
Boundary for River Rch & Prof#=SANDCREEKTRIB13,Reach-1         , 4
Up Type= 0
Dn Type= 3
Dn Slope=0.005
Boundary for River Rch & Prof#=SANDCREEKTRIB13,Reach-1         , 5
Up Type= 0
Dn Type= 3
Dn Slope=0.005
Boundary for River Rch & Prof#=SANDCREEKTRIB13,Reach-1         , 6
Up Type= 0
Dn Type= 3
Dn Slope=0.005
Boundary for River Rch & Prof#=SANDCREEKTRIB13,Reach-1         , 7
Up Type= 0
Dn Type= 3
Dn Slope=0.005
DSS Import GetInterval= 0
DSS Import GetPeak= 0
DSS Import FillOption= 0

--- SANDCREEKTRIB13.g01 (geometry) ---

Geom Title=Existing Conditions
Program Version=4.10

River Reach=SANDCREEKTRIB13 ,Reach-1
Reach XY= 30
      3572862.73     10279383.45      3572819.89     10279527.41
      3573175.72     10279745.43       3573668.3     10279679.76
      3573709.19     10279847.23      3574272.21     10279918.04
      3574402.78     10280367.36      3574582.46     10280192.42
      3575303.55     10280323.94      3575637.57     10280200.33
      3575914.66      10280279.5      3575975.07     10280064.91
      3576369.57     10280138.25      3576420.09     10280587.46
      3576649.63     10280876.53      3576879.48     10280847.02
      3576762.97     10280972.08      3576869.87     10281263.41
      3576726.44     10281734.74      3576906.55     10281629.79
      3577020.21     10281781.36      3576904.66     10282020.55
      3577160.94     10282151.84      3576942.09     10282546.33
       3577117.9     10282454.22      3577172.03     10282601.76
      3576954.86     10282757.11      3577102.11     10282885.12
      3577023.96     10283335.66      3577712.11     10284011.64

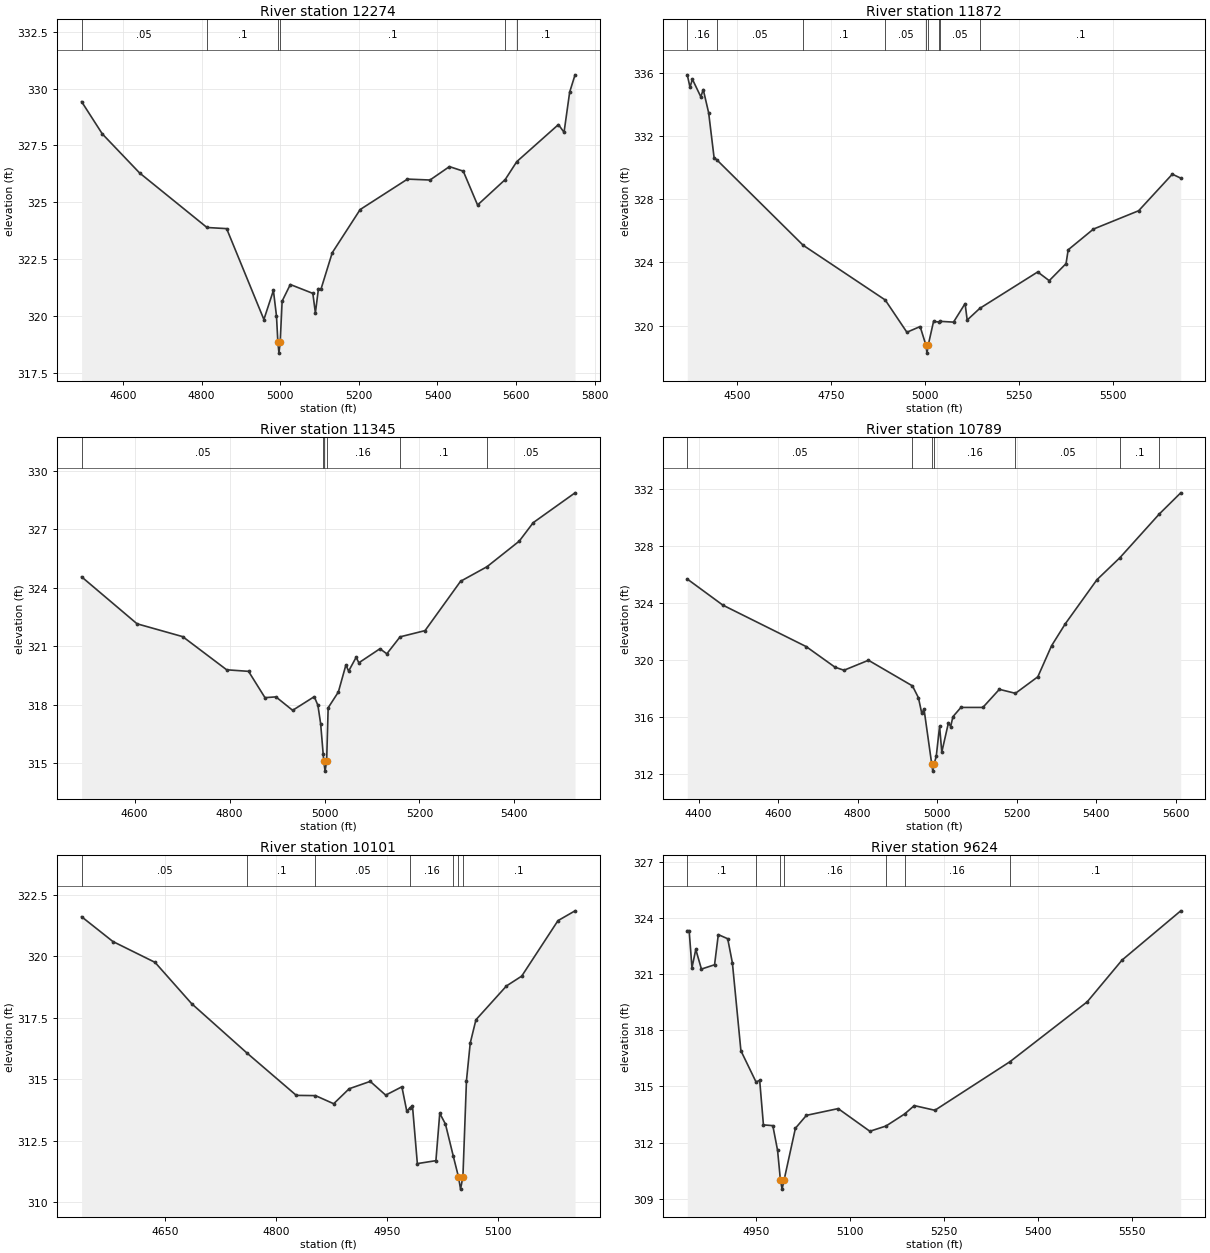
Type RM Length L Ch R = 1 ,12274   ,402,402,402
BEGIN DESCRIPTION:
UNT0459 IN WICK 23.0
END DESCRIPTION:
XS GIS Cut Line= 3
       3572642.1     10279991.66      3572792.11     10279541.64
      3573392.12     10279041.63
#Sta/Elev= 30
  4494.7  329.43  4547.4  328.01  4642.3  326.29  4813.7  323.89  4863.7  323.84
  4958.5  319.84  4982.7  321.12  4990.5     320    4994  318.86  4996.8  318.36
    5000  318.86  5004.9  320.65  5025.7  321.38    5083  320.99  5089.5  320.13
  5097.3   321.2  5103.8  321.18  5132.4  322.78  5203.4  324.68  5323.8  326.02
  5381.1  325.98  5430.5  326.57  5465.7  326.37  5502.1  324.88  5572.4     326
  5601.9  326.79  5707.8  328.42  5722.1  328.08  5736.4  329.85  5750.1  330.61
#Mann= 6 ,-1 , 0
  4494.7     .05       0  4813.7      .1       0    4994     .07       0
    5000      .1       0  5572.4     .05       0  5601.9      .1       0
Bank Sta=4994,5000
XS Rating Curve= 0 ,0
Exp/Cntr=0.3,0.1

Type RM Length L Ch R = 1 ,11872   ,527,527,527
BEGIN DESCRIPTION:
UNT0459 IN WICK 22.0
END DESCRIPTION:
XS GIS Cut Line= 3
      3572742.12     10280191.62      3573142.11     10279691.64
       3573442.1     10279091.64
#Sta/Elev= 30
  4368.1  335.86  4375.3  335.08  4381.7  335.58  4404.1  334.47  4410.5  334.93
  4424.9  333.46  4439.3  330.63  4446.9  330.48  4675.9  325.09    4894  321.63
  4951.6  319.59  4986.8  319.95  5002.2  318.77  5004.9  318.27  5008.2  318.77
  5022.4  320.27  5037.6  320.24  5039.3  320.28  5075.5  320.23  5106.2   321.4
  5111.8  320.36  5145.3   321.1  5299.1   323.4  5329.8  322.85  5374.5  323.93
  5380.1   324.8  5447.2  326.11  5567.4  327.27  5656.8  329.58  5679.2  329.33
#Mann= 9 ,-1 , 0
  4368.1     .16       0  4446.9     .05       0  4675.9      .1       0
    4894     .05       0  5002.2     .03       0  5008.2     .05       0
  5037.6      .1       0  5039.3     .05       0  5145.3      .1       0
Bank Sta=5002.2,5008.2
XS Rating Curve= 0 ,0
Exp/Cntr=0.3,0.1

Type RM Length L Ch R = 1 ,11345   ,556,556,556
BEGIN DESCRIPTION:
UNT0459 IN WICK 21.0
END DESCRIPTION:
XS GIS Cut Line= 2
      3573268.16     10280166.62        3573786.     10279265.29
#Sta/Elev= 30
  4488.3  324.56  4605.1  322.15  4701.4  321.49  4793.9  319.79    4840  319.71
  4874.6  318.36  4897.7   318.4  4932.9  317.71  4978.4  318.41  4986.1  317.97
  4991.9  317.02  4997.2  315.47  4998.5  315.09  5001.2  314.59  5004.5  315.09
  5007.7  317.84  5029.2  318.65  5045.1  320.04  5050.8  319.72  5066.6  320.43
  5072.4  320.15  5116.8  320.87  5131.3  320.61  5159.2  321.48  5211.8   321.8
  5286.6  324.33  5342.4  325.08  5410.2  326.39  5439.7  327.34  5527.8  328.87
#Mann= 6 ,-1 , 0
  4488.3     .05       0  4997.2     .16       0  4998.5     .07       0
  5004.5     .16       0  5159.2      .1       0  5342.4     .05       0
Bank Sta=4998.5,5004.5
XS Rating Curve= 0 ,0
Exp/Cntr=0.3,0.1

Type RM Length L Ch R = 1 ,10789   ,688,688,688
BEGIN DESCRIPTION:
UNT0459 IN WICK 20.0
END DESCRIPTION:
XS GIS Cut Line= 3
      3573592.12     10280391.61      3573892.11     10279791.64
      3574042.11     10279241.62
#Sta/Elev= 30
  4371.5  325.71  4460.9  323.88  4670.5  320.97  4743.2  319.52  4765.6  319.31
  4827.1  320.01  4937.8  318.21  4952.8  317.38  4961.2  316.28  4966.8  316.59
  4986.2  312.73  4988.9  312.23  4992.2  312.73  4997.6  313.27    5006  315.38
  5011.5  313.56  5028.3  315.63  5033.9  315.36  5039.5  316.05  5059.6   316.7
  5114.8   316.7  5156.3  317.97  5196.7  317.69    5253  318.85  5287.6  321.03
  5322.1  322.57  5401.6  325.66  5459.5  327.21  5558.3  330.27  5612.4  331.76
#Mann= 7 ,-1 , 0
  4371.5     .05       0  4937.8     .16       0  4986.2     .07       0
  4992.2     .16       0  5196.7     .05       0  5459.5      .1       0
  5558.3     .05       0
Bank Sta=4986.2,4992.2
XS Rating Curve= 0 ,0
Exp/Cntr=0.3,0.1

Type RM Length L Ch R = 1 ,10101   ,477,477,477
BEGIN DESCRIPTION:
UNT0459 IN WICK 19.0
END DESCRIPTION:
XS GIS Cut Line= 3
       3573992.1     10280341.65      3574292.11     10279991.64
      3574342.09     10279791.69
#Sta/Elev= 30
  4537.6  321.62  4579.9  320.61  4636.9  319.76  4686.3  318.08  4761.4  316.06
  4827.9  314.34  4853.8  314.33  4878.4     314  4899.3  314.61  4927.8  314.91
  4948.7  314.35  4970.6  314.69  4977.2   313.7  4981.7  313.83  4984.9  313.92
  4991.5  311.56  5016.6  311.68  5021.8  313.61  5029.5  313.17  5040.2  311.85
  5047.1  311.02  5049.9  310.52  5053.1  311.02  5057.9  314.94    5063  316.47
  5070.7  317.42    5112   318.8  5132.6   319.2  5181.6  321.46  5204.7  321.86
#Mann= 7 ,-1 , 0
  4537.6     .05       0  4761.4      .1       0  4853.8     .05       0
  4981.7     .16       0  5040.2      .1       0  5047.1     .07       0
  5053.1      .1       0
Bank Sta=5047.1,5053.1
XS Rating Curve= 0 ,0
Exp/Cntr=0.3,0.1

Type RM Length L Ch R = 1 ,9624    ,448,448,448
BEGIN DESCRIPTION:
UNT0459 IN WICK 18.0
END DESCRIPTION:
XS GIS Cut Line= 3
      3574292.09     10280491.67      3574392.11     10280341.64
      3574492.11     10279741.63
#Sta/Elev= 30
  4839.6  323.32  4842.6  323.32  4847.1  321.34  4853.2  322.32  4862.2  321.27
  4883.2   321.5  4889.2  323.11  4904.2  322.89  4911.7   321.6  4925.3  316.91
  4949.5  315.24  4955.3  315.33  4961.3  312.95  4976.3  312.91  4983.9  311.59
  4988.4  310.02  4991.1  309.52  4994.4  310.02  5012.4  312.77    5030  313.46
  5080.7  313.82  5131.4  312.61  5157.2  312.89  5186.8  313.53  5202.4  313.98
  5235.3  313.73  5355.1  316.32  5478.7  319.52  5534.4  321.75  5628.2  324.38
#Mann= 7 ,-1 , 0
  4839.6      .1       0  4949.5     .16       0  4988.4     .07       0
  4994.4     .16       0  5157.2     .05       0  5186.8     .16       0
  5355.1      .1       0
Bank Sta=4988.4,4994.4
XS Rating Curve= 0 ,0
Exp/Cntr=0.3,0.1

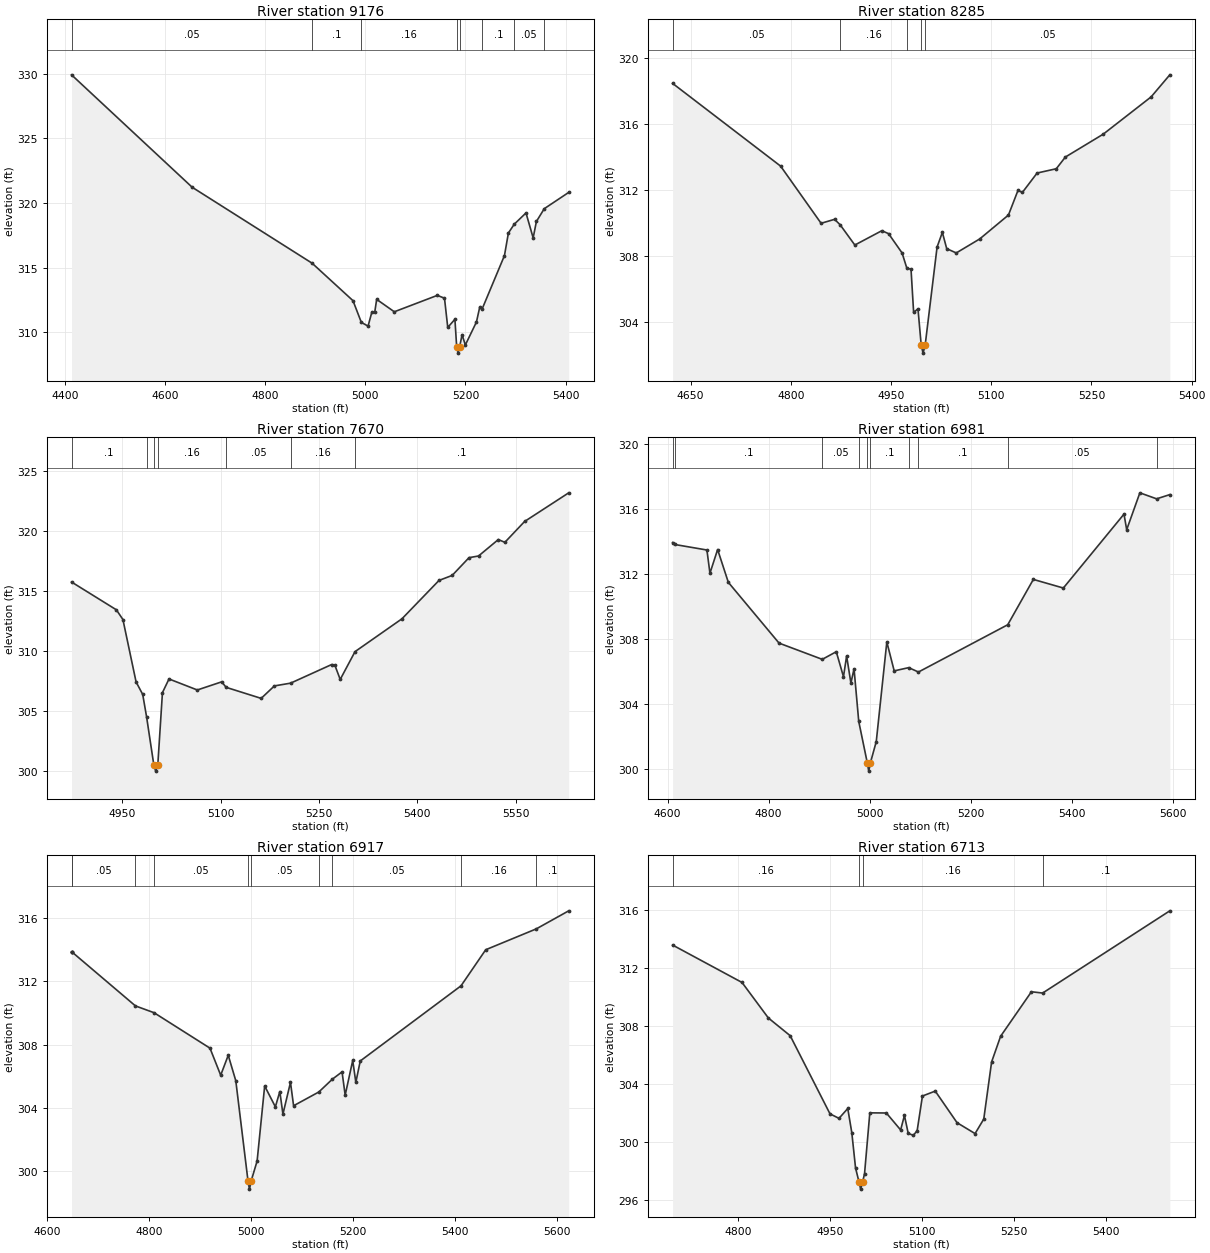
Type RM Length L Ch R = 1 ,9176    ,891,891,891
BEGIN DESCRIPTION:
UNT0459 IN WICK 17.0
END DESCRIPTION:
XS GIS Cut Line= 3
      3574592.11     10280791.62      3574642.11     10280191.64
      3574892.13     10279891.62
#Sta/Elev= 30
  4413.6  329.92  4654.4  321.22  4893.9  315.34  4975.5  312.44  4992.2  310.76
  5005.6  310.47  5013.1  311.54  5018.9  311.54  5022.8  312.54    5058  311.58
  5143.9  312.85  5158.2  312.63  5164.7  310.37    5179     311  5182.5  308.88
  5185.3  308.38  5188.5  308.88  5193.3  309.81  5199.8  309.01    5222  310.79
  5228.5  311.93  5233.6  311.82  5277.9  315.93  5285.8  317.68  5297.5  318.36
  5320.9  319.23  5335.2   317.3  5341.7  318.57  5357.4  319.56  5406.2  320.82
#Mann= 8 ,-1 , 0
  4413.6     .05       0  4893.9      .1       0  4992.2     .16       0
  5182.5     .07       0  5188.5     .16       0  5233.6      .1       0
  5297.5     .05       0  5357.4      .1       0
Bank Sta=5182.5,5188.5
XS Rating Curve= 0 ,0
Exp/Cntr=0.3,0.1

Type RM Length L Ch R = 1 ,8285    ,615,615,615
BEGIN DESCRIPTION:
UNT0459 IN WICK 15.0
END DESCRIPTION:
XS GIS Cut Line= 3
       3575442.1     10280591.63      3575392.11     10280241.64
      3575142.08     10279941.61
#Sta/Elev= 30
  4623.2  318.46  4784.8  313.44  4845.4  309.97  4865.6  310.21  4873.9  309.88
  4895.9  308.65  4936.3  309.52  4946.4  309.34  4966.6  308.17  4973.7  307.25
    4980  307.18  4983.9  304.56  4990.4  304.78  4995.2  302.59    4998  302.09
  5001.2  302.59    5019  308.53  5026.9  309.42  5033.4  308.43  5047.7  308.17
  5082.8  309.02  5125.8  310.47  5140.1  311.97  5146.6  311.84  5168.7  313.02
  5197.4  313.28    5211  313.99  5267.7  315.38  5339.3  317.64  5367.3  318.98
#Mann= 5 ,-1 , 0
  4623.2     .05       0  4873.9     .16       0  4973.7     .05       0
  4995.2     .03       0  5001.2     .05       0
Bank Sta=4995.2,5001.2
XS Rating Curve= 0 ,0
Exp/Cntr=0.3,0.1

Type RM Length L Ch R = 1 ,7670    ,689,689,689
BEGIN DESCRIPTION:
UNT0459 IN WICK 14.0
END DESCRIPTION:
XS GIS Cut Line= 2
       3575838.9      10280399.7      3575911.63     10279644.69
#Sta/Elev= 30
  4872.5  315.75  4940.9  313.43  4950.9  312.62    4971  307.41  4981.1  306.37
    4987   304.5  4998.1  300.47  5000.9  299.97  5004.1  300.47  5011.2  306.52
  5021.2  307.66  5064.4  306.74  5101.6  307.42  5108.4  306.96  5161.8  306.04
    5182  307.08  5206.7  307.31  5269.2  308.86  5274.2  308.81  5282.4  307.62
    5305  309.94  5376.6  312.68  5433.1  315.88  5453.2   316.3  5478.9  317.78
  5493.4  317.92  5523.6  319.29  5533.6  319.06  5563.7   320.8    5631  323.19
#Mann= 7 ,-1 , 0
  4872.5      .1       0    4987     .16       0  4998.1     .07       0
  5004.1     .16       0  5108.4     .05       0  5206.7     .16       0
    5305      .1       0
Bank Sta=4998.1,5004.1
XS Rating Curve= 0 ,0
Exp/Cntr=0.3,0.1

Type RM Length L Ch R = 1 ,6981    ,64,64,64
BEGIN DESCRIPTION:
Mapping XS d36eb9cc
END DESCRIPTION:
XS GIS Cut Line= 6
      3576019.01     10280371.21      3576102.32      10280239.3
      3576222.12     10280112.57      3576324.55     10279971.94
      3576444.34     10279779.23      3576525.94     10279539.64
#Sta/Elev= 30
  4610.1  313.96  4614.3  313.84    4678   313.5    4684  312.07  4699.2  313.53
  4720.4  311.51  4820.8  307.77  4906.4  306.77  4934.1  307.24  4948.4   305.7
  4954.6  306.98  4963.1  305.31  4969.3  306.19  4978.6  302.95  4995.6  300.39
  4998.4  299.89  5001.6  300.39  5013.3  301.71  5034.2  307.84  5048.8  306.06
  5077.5  306.26  5096.8  305.99  5273.6   308.9  5324.3  311.69  5383.7  311.16
  5503.8  315.71  5509.1  314.75  5535.2  317.02  5568.4  316.65  5594.5  316.91
#Mann= 10 ,-1 , 0
  4610.1     .05       0  4614.3      .1       0  4906.4     .05       0
  4978.6      .1       0  4995.6     .07       0  5001.6      .1       0
  5077.5     .05       0  5096.8      .1       0  5273.6     .05       0
  5568.4      .1       0
Bank Sta=4995.6,5001.6
XS Rating Curve= 0 ,0
Exp/Cntr=0.3,0.1

Type RM Length L Ch R = 1 ,6917    ,204,204,204
BEGIN DESCRIPTION:
Mapping XS 8233713d
END DESCRIPTION:
XS GIS Cut Line= 6
      3576090.14     10280371.28      3576180.45     10280263.61
      3576258.57     10280173.33      3576458.23     10279888.61
      3576569.34     10279579.58      3576574.54     10279541.39
#Sta/Elev= 30
  4648.5  313.84  4649.4  313.84  4649.7  313.84  4773.8  310.44  4810.3  310.01
  4919.9  307.77  4940.9  306.06  4955.7  307.32  4970.5  305.71  4994.5  299.36
  4997.3  298.86  5000.5  299.36  5012.3  300.64  5027.1  305.38  5048.1  304.06
  5056.8  305.03  5062.9   303.6  5077.7  305.61  5083.8  304.13  5133.3     305
  5159.8  305.81  5178.8  306.27  5184.9   304.8  5199.7  306.99  5205.8  305.61
  5214.5  306.96    5412  311.71  5460.4  313.99  5559.6  315.31  5623.1  316.45
#Mann= 11 ,-1 , 0
  4648.5     .05       0  4649.4     .16       0  4649.7     .05       0
  4773.8      .1       0  4810.3     .05       0  4994.5     .04       0
  5000.5     .05       0  5133.3      .1       0  5159.8     .05       0
    5412     .16       0  5559.6      .1       0
Bank Sta=4994.5,5000.5
XS Rating Curve= 0 ,0
Exp/Cntr=0.3,0.1

Type RM Length L Ch R = 1 ,6713    ,396,396,396
BEGIN DESCRIPTION:
UNT0459 IN WICK 12.0
END DESCRIPTION:
XS GIS Cut Line= 2
      3576120.17     10280437.91      3576778.48     10279963.23
#Sta/Elev= 30
  4692.7  313.61    4806  311.03    4849  308.58  4884.6  307.36  4949.6  301.97
  4964.3  301.66  4978.6  302.34  4985.2  300.67  4991.3  298.24  4996.9  297.28
  4999.6  296.78  5002.9  297.28    5006  297.85  5014.6  302.04  5041.6  302.03
  5064.9  300.86  5071.1  301.86  5077.3  300.62  5085.8  300.49  5091.9  300.82
  5100.5   303.2  5121.4  303.54    5157  301.36  5186.4  300.61  5200.6  301.61
  5213.4  305.55  5228.1  307.32  5278.4  310.39  5296.7   310.3  5504.3  315.97
#Mann= 4 ,-1 , 0
  4692.7     .16       0  4996.9     .07       0  5002.9     .16       0
  5296.7      .1       0
Bank Sta=4996.9,5002.9
XS Rating Curve= 0 ,0
Exp/Cntr=0.3,0.1

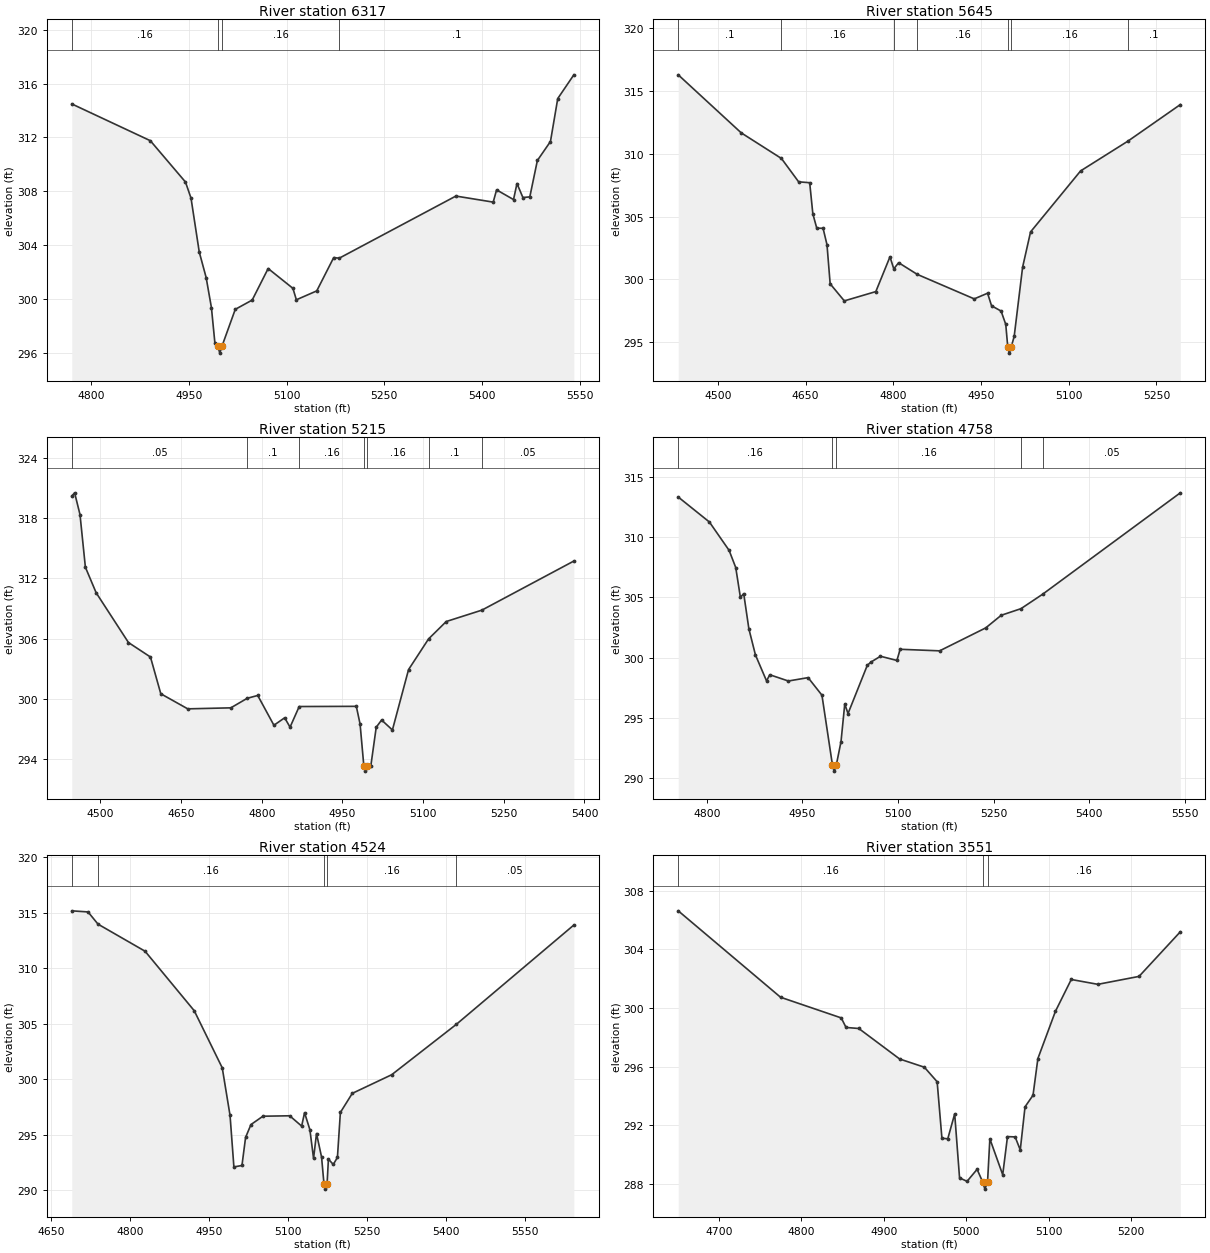
Type RM Length L Ch R = 1 ,6317    ,672,672,672
BEGIN DESCRIPTION:
UNT0459 IN WICK 11.0
END DESCRIPTION:
XS GIS Cut Line= 2
      3576206.94     10280667.09      3576936.08      10280417.1
#Sta/Elev= 30
  4770.1  314.49  4890.7  311.76  4944.7  308.69  4953.2  307.49  4965.8   303.5
  4976.4   301.6  4984.5  299.37  4989.8  296.76  4994.6  296.49  4997.3  295.99
  5000.6  296.49  5021.1  299.24  5047.1  299.93  5071.6  302.27  5109.6   300.8
  5114.9  299.95  5146.2  300.61  5172.2  303.08  5180.8  303.04  5359.8  307.65
  5417.1   307.2  5422.3  308.11  5448.3  307.39  5453.6  308.58  5462.7  307.54
  5473.3  307.59  5484.9  310.29    5505   311.7  5516.2  314.89  5540.9  316.65
#Mann= 4 ,-1 , 0
  4770.1     .16       0  4994.6     .07       0  5000.6     .16       0
  5180.8      .1       0
Bank Sta=4994.6,5000.6
XS Rating Curve= 0 ,0
Exp/Cntr=0.3,0.1

Type RM Length L Ch R = 1 ,5645    ,430,430,430
BEGIN DESCRIPTION:
UNT0459 IN WICK 10.0
END DESCRIPTION:
XS GIS Cut Line= 3
      3576342.15     10281041.62      3576842.11     10280841.64
      3577092.09     10280641.66
#Sta/Elev= 30
  4432.3  316.29    4540  311.67  4608.8  309.63  4638.2  307.77  4657.1   307.7
  4662.5  305.22  4669.2  304.08    4680  304.07  4686.7  302.76  4692.1  299.65
  4716.3  298.29  4770.2  299.03  4794.4   301.8  4800.9  300.84  4809.2  301.33
  4841.1   300.4  4938.5  298.45  4961.3   298.9  4968.1   297.9  4984.4  297.48
  4992.4  296.42  4995.8  294.63  4998.5  294.13  5001.8  294.63  5006.8  295.46
  5021.2  300.97  5034.8  303.78  5120.4  308.64  5201.3  311.01  5290.9  313.92
#Mann= 7 ,-1 , 0
  4432.3      .1       0  4608.8     .16       0  4800.9      .1       0
  4841.1     .16       0  4995.8     .07       0  5001.8     .16       0
  5201.3      .1       0
Bank Sta=4995.8,5001.8
XS Rating Curve= 0 ,0
Exp/Cntr=0.3,0.1

Type RM Length L Ch R = 1 ,5215    ,457,457,457
BEGIN DESCRIPTION:
UNT0459 IN WICK 9.0
END DESCRIPTION:
XS GIS Cut Line= 2
      3576286.84     10281174.03      3577218.98     10281125.52
#Sta/Elev= 30
  4446.9  320.17  4452.2  320.49  4462.2  318.33  4472.2   313.1  4492.2  310.56
  4552.3  305.61  4593.2  304.17  4612.4  300.52  4662.5  299.02  4742.6  299.12
  4773.1  300.07  4792.6  300.35  4822.7  297.39  4842.7  298.13  4852.7   297.2
  4869.7  299.25  4975.9  299.27  4982.9  297.51  4989.9  293.33  4992.7  292.83
  4995.9  293.33  5002.9  293.36  5012.9  297.19  5022.9  297.91    5043  296.92
    5073  302.92  5110.2  305.97  5143.1   307.7  5209.3  308.83  5380.3  313.71
#Mann= 7 ,-1 , 0
  4446.9     .05       0  4773.1      .1       0  4869.7     .16       0
  4989.9     .07       0  4995.9     .16       0  5110.2      .1       0
  5209.3     .05       0
Bank Sta=4989.9,4995.9
XS Rating Curve= 0 ,0
Exp/Cntr=0.3,0.1

Type RM Length L Ch R = 1 ,4758    ,234,234,234
BEGIN DESCRIPTION:
UNT0459 IN WICK 8.0
END DESCRIPTION:
XS GIS Cut Line= 2
      3576484.73     10281521.25       3577247.9     10281326.99
#Sta/Elev= 30
  4755.2  313.36  4804.1  311.28    4835  308.92  4845.4  307.49  4852.7  305.01
  4857.9  305.32    4866  302.39  4876.3  300.22  4893.7  298.06  4898.8  298.57
  4927.9  298.05  4958.9  298.33  4980.6  296.87  4997.1  291.05  4999.9  290.55
  5003.1  291.05  5010.5     293  5016.4  296.14  5021.5  295.34  5051.7  299.35
  5057.3  299.62  5072.4  300.11  5098.2  299.76  5103.3  300.69  5165.2  300.56
  5237.5  302.47  5261.8  303.52  5292.8  304.07  5326.7  305.27  5542.7  313.71
#Mann= 5 ,-1 , 0
  4755.2     .16       0  4997.1     .07       0  5003.1     .16       0
  5292.8      .1       0  5326.7     .05       0
Bank Sta=4997.1,5003.1
XS Rating Curve= 0 ,0
Exp/Cntr=0.3,0.1

Type RM Length L Ch R = 1 ,4524    ,973,973,973
BEGIN DESCRIPTION:
UNT0459 IN WICK 7.0
END DESCRIPTION:
XS GIS Cut Line= 3
      3576422.24     10281792.09      3576606.26     10281743.48
      3577293.78      10281413.6
#Sta/Elev= 30
  4689.1  315.18    4720  315.08  4738.9  313.98  4828.2  311.54  4921.5  306.18
  4974.7  301.03  4989.5  296.74  4996.8   292.1  5012.1  292.23    5019  294.76
  5029.2  295.92  5051.9  296.67  5102.7  296.71  5125.4  295.78  5130.9  296.99
    5141  295.46    5148  292.87  5153.6  295.11  5163.2  292.99  5167.7   290.6
  5170.4   290.1  5173.7   290.6  5176.2  292.81  5185.4  292.32  5193.3  292.96
  5198.9  297.01  5221.5  298.73  5296.3  300.41    5419  304.95    5642   313.9
#Mann= 5 ,-1 , 0
  4689.1      .1       0  4738.9     .16       0  5167.7     .07       0
  5173.7     .16       0    5419     .05       0
Bank Sta=5167.7,5173.7
XS Rating Curve= 0 ,0
Exp/Cntr=0.3,0.1

Type RM Length L Ch R = 1 ,3551    ,572,572,572
BEGIN DESCRIPTION:
UNT0459 IN WICK 6.0
END DESCRIPTION:
XS GIS Cut Line= 3
      3576692.09     10282241.65      3577103.48      10281992.9
      3577232.22     10281994.11
#Sta/Elev= 30
  4650.5  306.62  4774.7  300.73  4848.4  299.32  4854.2  298.67  4869.7   298.6
  4919.3  296.52  4949.3  295.96  4964.8  294.97  4970.6  291.12  4977.7  291.08
  4986.1  292.78    4992  288.42  5001.1  288.18  5013.3     289    5020  288.15
  5022.8  287.65    5026  288.15  5028.8  291.08  5044.4  288.63  5050.2  291.23
  5059.5  291.21  5065.7  290.32  5071.5  293.26  5081.2  294.05  5087.1  296.55
  5108.4  299.77  5127.6  301.94  5159.9  301.61  5209.9  302.15    5260  305.19
#Mann= 3 ,-1 , 0
  4650.5     .16       0    5020     .07       0    5026     .16       0
Bank Sta=5020,5026
XS Rating Curve= 0 ,0
Exp/Cntr=0.3,0.1

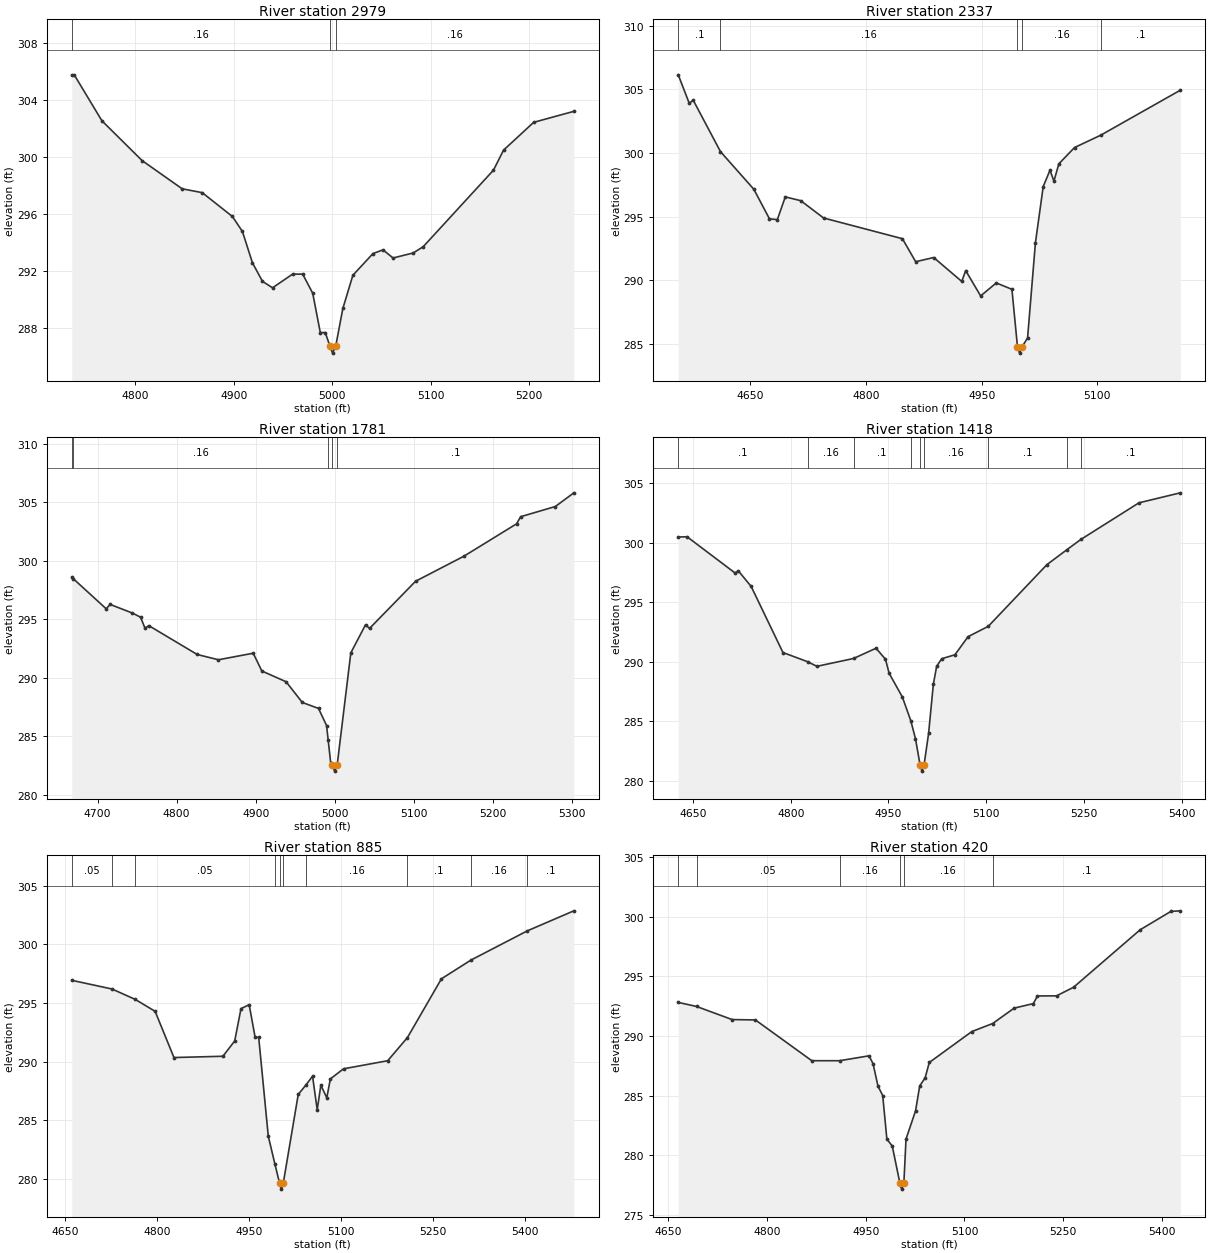
Type RM Length L Ch R = 1 ,2979    ,642,642,642
BEGIN DESCRIPTION:
UNT0459 IN WICK 5.0
END DESCRIPTION:
XS GIS Cut Line= 3
      3576742.14     10282441.64      3576992.11     10282391.64
      3577242.13     10282341.64
#Sta/Elev= 30
  4735.6  305.74  4738.1  305.74  4766.2  302.52    4807  299.73  4847.7  297.75
  4868.1  297.48  4898.7  295.81  4908.9  294.76  4919.1  292.56  4929.3  291.26
  4939.5  290.81  4959.9  291.77  4970.1  291.77  4980.3  290.43    4988  287.67
  4993.1  287.67  4997.7  286.73  5000.5  286.23  5003.7  286.73  5010.9  289.36
  5021.1  291.69  5041.5  293.21  5051.7  293.47  5061.9   292.9  5082.3  293.25
  5092.5  293.69  5163.9  299.06  5174.1  300.46  5204.7  302.41  5245.5  303.18
#Mann= 3 ,-1 , 0
  4735.6     .16       0  4997.7     .07       0  5003.7     .16       0
Bank Sta=4997.7,5003.7
XS Rating Curve= 0 ,0
Exp/Cntr=0.3,0.1

Type RM Length L Ch R = 1 ,2337    ,556,556,556
BEGIN DESCRIPTION:
Mapping XS 9f86b66b
END DESCRIPTION:
XS GIS Cut Line= 2
      3576735.43     10282699.49       3577377.4     10282588.45
#Sta/Elev= 30
  4556.3  306.15  4570.6  303.91  4575.7  304.16  4611.1  300.11  4654.4  297.15
  4674.7  294.82  4684.9  294.76  4695.2  296.55  4715.3  296.25  4744.9  294.89
  4847.2  293.26  4864.4  291.45  4887.8  291.78  4924.2   289.9  4929.3  290.75
  4948.7  288.76    4969  289.78  4989.3  289.28  4996.5  284.76  4999.2  284.26
  5002.5  284.76  5009.6  285.45  5019.8  292.94  5029.9  297.36  5038.7  298.65
  5043.8  297.79  5050.2  299.15  5070.5  300.43  5104.5   301.4  5207.8  304.94
#Mann= 5 ,-1 , 0
  4556.3      .1       0  4611.1     .16       0  4996.5     .07       0
  5002.5     .16       0  5104.5      .1       0
Bank Sta=4996.5,5002.5
XS Rating Curve= 0 ,0
Exp/Cntr=0.3,0.1

Type RM Length L Ch R = 1 ,1781    ,363,363,363
BEGIN DESCRIPTION:
UNT0459 IN WICK 4.0
END DESCRIPTION:
XS GIS Cut Line= 2
      3576777.08     10282956.44      3577397.82      10282821.2
#Sta/Elev= 30
  4667.3   298.6  4669.2  298.48  4710.8  295.91  4715.9  296.28  4744.1  295.54
  4754.3  295.19  4759.9  294.26    4765  294.46    4826     292  4852.9  291.55
  4896.9  292.11  4907.8  290.59  4938.5  289.67    4959   287.9  4979.5  287.39
  4989.7  285.93  4991.7  284.71    4995  282.71  4997.1  282.53  4999.9  282.03
  5003.1  282.53  5020.4  292.14    5039  294.54  5044.1  294.23  5102.3  298.26
  5163.7  300.41  5230.1  303.17  5235.3  303.78  5279.2  304.65  5302.6  305.82
#Mann= 5 ,-1 , 0
  4667.3      .1       0  4669.2     .16       0  4991.7      .1       0
  4997.1     .07       0  5003.1      .1       0
Bank Sta=4997.1,5003.1
XS Rating Curve= 0 ,0
Exp/Cntr=0.3,0.1

Type RM Length L Ch R = 1 ,1418    ,533,533,533
BEGIN DESCRIPTION:
UNT0459 IN WICK 3.0
END DESCRIPTION:
XS GIS Cut Line= 2
      3576711.16      10283248.1      3577475.05     10283147.41
#Sta/Elev= 30
  4627.4  300.49    4641  300.51  4714.6  297.47  4719.6  297.65  4739.3  296.34
  4788.1  290.79  4825.8  290.02  4840.2  289.63  4896.5  290.29  4930.9  291.15
  4945.4  290.23  4951.1  289.04  4971.3  287.06  4984.2  285.08  4991.5  283.55
  4998.6  281.33  5001.3  280.83  5004.6  281.33  5011.6  283.99  5018.9  288.12
    5024  289.64  5031.8  290.27    5052   290.6  5072.2  292.12  5103.2  292.99
  5193.2  298.17  5223.5  299.41  5245.4  300.29  5334.4  303.36  5397.9   304.2
#Mann= 9 ,-1 , 0
  4627.4      .1       0  4825.8     .16       0  4896.5      .1       0
  4984.2     .16       0  4998.6     .07       0  5004.6     .16       0
  5103.2      .1       0  5223.5     .16       0  5245.4      .1       0
Bank Sta=4998.6,5004.6
XS Rating Curve= 0 ,0
Exp/Cntr=0.3,0.1

Type RM Length L Ch R = 1 ,885     ,465,465,465
BEGIN DESCRIPTION:
UNT0459 IN WICK 2.0
END DESCRIPTION:
XS GIS Cut Line= 2
      3576825.71     10283702.96       3577527.1     10283282.82
#Sta/Elev= 30
  4661.4  296.94  4726.9   296.2  4764.5  295.32  4797.1   294.3  4827.8  290.36
  4907.5  290.47  4926.7  291.77    4937  294.53  4950.3  294.86    4960  292.08
  4965.8  292.08  4981.4  283.66  4992.1  281.31  4999.8  279.65  5002.5  279.15
  5005.8  279.65  5030.2  287.22  5042.1  287.98  5053.5  288.77  5061.1  285.91
    5067     288  5076.7  286.93  5082.5  288.54  5103.9   289.4  5175.9  290.09
    5208  292.06  5263.4  297.07  5311.3  298.66  5403.5  301.16    5479  302.86
#Mann= 10 ,-1 , 0
  4661.4     .05       0  4726.9     .16       0  4764.5     .05       0
  4992.1      .1       0  4999.8     .07       0  5005.8      .1       0
  5042.1     .16       0    5208      .1       0  5311.3     .16       0
  5403.5      .1       0
Bank Sta=4999.8,5005.8
XS Rating Curve= 0 ,0
Exp/Cntr=0.3,0.1

Type RM Length L Ch R = 1 ,420     ,0,0,0
BEGIN DESCRIPTION:
UNT0459 IN WICK 1.0
END DESCRIPTION:
XS GIS Cut Line= 3
      3577200.71     10283925.18      3577679.87     10283560.61
      3577665.98     10283400.89
#Sta/Elev= 30
  4665.4  292.82  4693.2  292.48  4747.2  291.38  4782.6  291.35  4868.2  287.93
  4910.5  287.93  4955.1  288.34  4961.3  287.67  4968.7   285.8  4975.9  285.01
  4982.2  281.36  4990.4  280.77    5002  277.66  5004.7  277.16    5008  277.66
  5011.3  281.36  5025.8  283.73  5032.1  285.82  5040.3  286.49  5046.6  287.78
  5111.1  290.37  5142.9  291.05  5175.5  292.34  5204.6  292.72  5210.9  293.36
  5239.9  293.37  5265.7  294.09  5366.8  298.91  5413.4  300.45  5427.8   300.5
#Mann= 6 ,-1 , 0
  4665.4      .1       0  4693.2     .05       0  4910.5     .16       0
    5002     .07       0    5008     .16       0  5142.9      .1       0
Bank Sta=5002,5008
XS Rating Curve= 0 ,0
Exp/Cntr=0.3,0.1

Chan Stop Cuts=-1
Use User Specified Reach Order=0
Composite Channel Slope=5