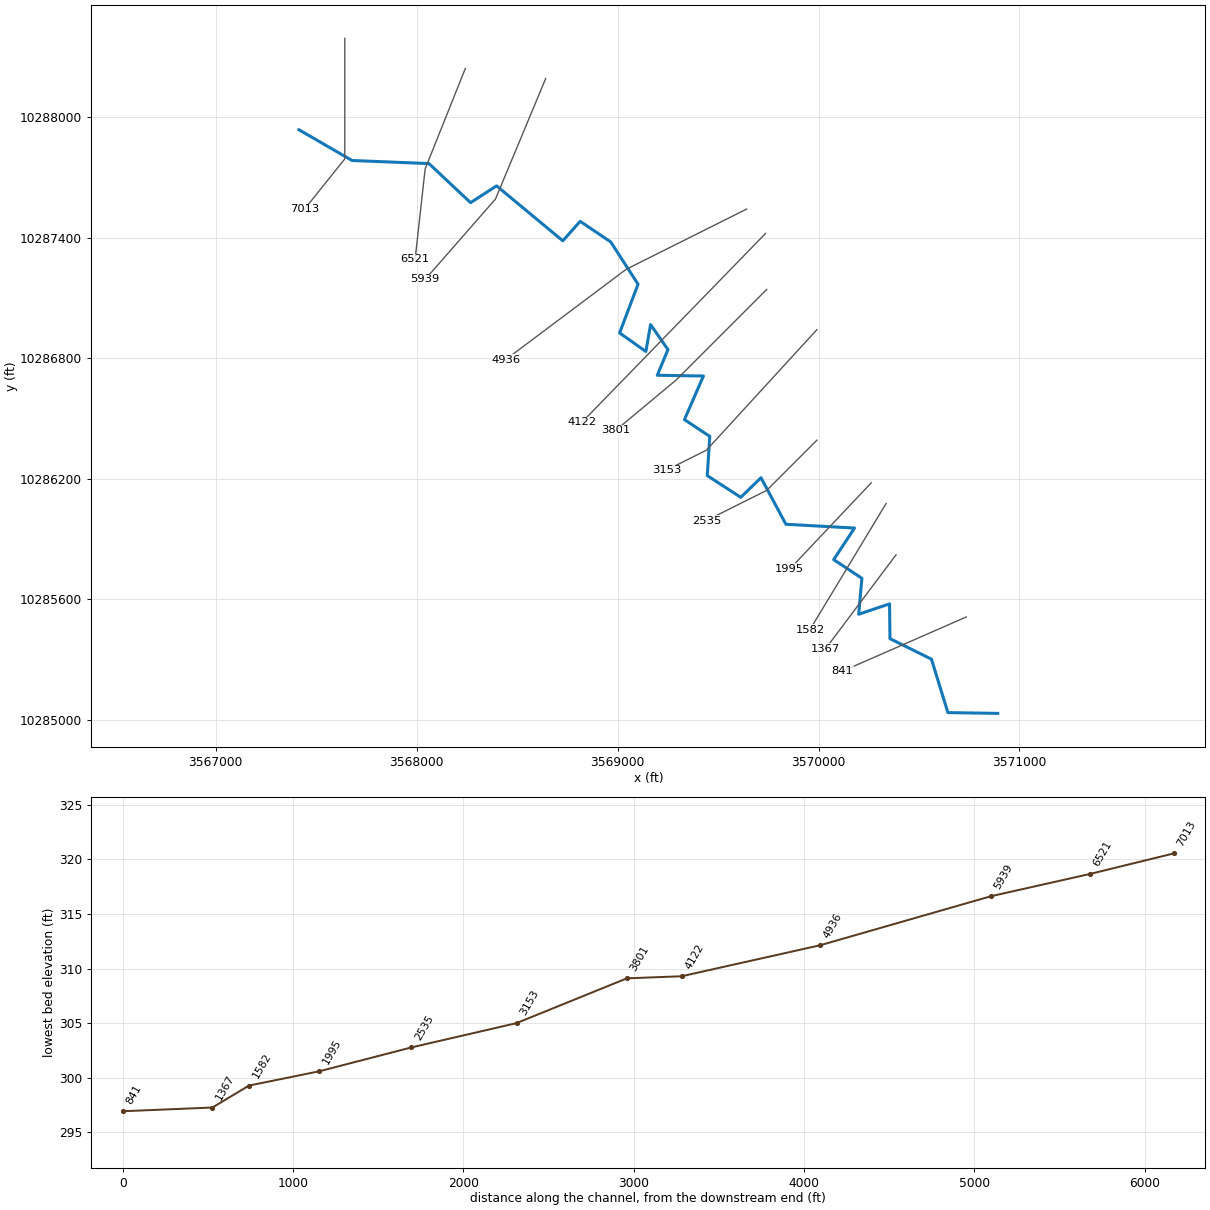
--- SANDCREEKTRIB16.prj (project) ---

Proj Title=SAND CREEK TRIB 16
Current Plan=p01
Default Exp/Contr=0.3,0.1
English Units
Geom File=g01
Flow File=f01
Plan File=p01
Y Axis Title=Elevation
X Axis Title(PF)=Main Channel Distance
X Axis Title(XS)=Station
BEGIN DESCRIPTION:
UNT1439 IN WICK
END DESCRIPTION:
DSS Export Rating Curves= 0
DSS Export Rating Curve Sorted= 0
DSS Export Volume Flow Curves= 0
DXF OffsetX= 0
DXF OffsetY= 0
DXF ScaleX= 1
DXF ScaleY= 10

--- SANDCREEKTRIB16.p01 (plan) ---

Plan Title=Multiple Run
Short Identifier=Multiple
Geom File=g01
Flow File=f01
Subcritical Flow
K Sum by GR= 0
Std Step Tol= 0.01
Critical Tol= 0.01
Num of Std Step Trials= 20
Max Error Tol= 0.3
Flow Tol Ratio= 0.001
Split Flow NTrial= 30
Split Flow Tol= 0.02
Split Flow Ratio= 0.02
Log Output Level= 0
Friction Slope Method= 1
Unsteady Friction Slope Method= 2
Unsteady Bridges Friction Slope Method= 1
Parabolic Critical Depth
Global Vel Dist=  1 , 1 , 1
Global Log Level= 0
CheckData=True
Encroach Param= -1, 0, 0, 0
BEGIN DESCRIPTION:
Multiple Run
END DESCRIPTION:

--- SANDCREEKTRIB16.f01 (steady flow) ---

Flow Title=Multiple
Program Version=4.10
Number of Profiles= 7
Profile Names=10-year,25-year,50-year,1pct_min,100-year,1pct_plu,500-year
River Rch & RM=UNT1439 IN WICK,Reach-1         ,7013
     410     538     640     558     754    1020    1049
River Rch & RM=SANDCREEKTRIB16,Reach-1         ,7013
     410     538     640     558     754    1020    1049
Boundary for River Rch & Prof#=SANDCREEKTRIB16,Reach-1         , 1
Up Type= 0
Dn Type= 3
Dn Slope=0.005
Boundary for River Rch & Prof#=SANDCREEKTRIB16,Reach-1         , 2
Up Type= 0
Dn Type= 3
Dn Slope=0.005
Boundary for River Rch & Prof#=SANDCREEKTRIB16,Reach-1         , 3
Up Type= 0
Dn Type= 3
Dn Slope=0.005
Boundary for River Rch & Prof#=SANDCREEKTRIB16,Reach-1         , 4
Up Type= 0
Dn Type= 3
Dn Slope=0.005
Boundary for River Rch & Prof#=SANDCREEKTRIB16,Reach-1         , 5
Up Type= 0
Dn Type= 3
Dn Slope=0.005
Boundary for River Rch & Prof#=SANDCREEKTRIB16,Reach-1         , 6
Up Type= 0
Dn Type= 3
Dn Slope=0.005
Boundary for River Rch & Prof#=SANDCREEKTRIB16,Reach-1         , 7
Up Type= 0
Dn Type= 3
Dn Slope=0.005
DSS Import GetInterval= 0
DSS Import GetPeak= 0
DSS Import FillOption= 0

--- SANDCREEKTRIB16.g01 (geometry) ---

Geom Title=Existing Conditions
Program Version=4.10

River Reach=SANDCREEKTRIB16 ,Reach-1
Reach XY= 30
      3567413.98     10287936.57      3567678.32     10287783.56
      3568060.97     10287768.19      3568268.34     10287573.52
      3568397.43     10287657.43      3568727.19     10287383.79
      3568813.65     10287480.67      3568965.67      10287378.3
      3569101.79     10287167.71      3569009.93      10286925.4
       3569140.6     10286832.78      3569164.05     10286966.71
      3569250.62      10286842.4       3569197.6     10286714.66
      3569427.17     10286710.76      3569332.75     10286493.86
      3569458.75     10286410.31      3569446.29     10286215.04
      3569612.96     10286107.05      3569713.65     10286204.62
      3569837.65     10285972.98      3570179.19     10285954.03
      3570075.61     10285796.89       3570215.9     10285704.05
      3570199.99      10285525.1      3570353.62     10285576.79
      3570355.68     10285403.49      3570562.21      10285301.5
      3570644.02     10285035.45      3570892.11     10285031.64

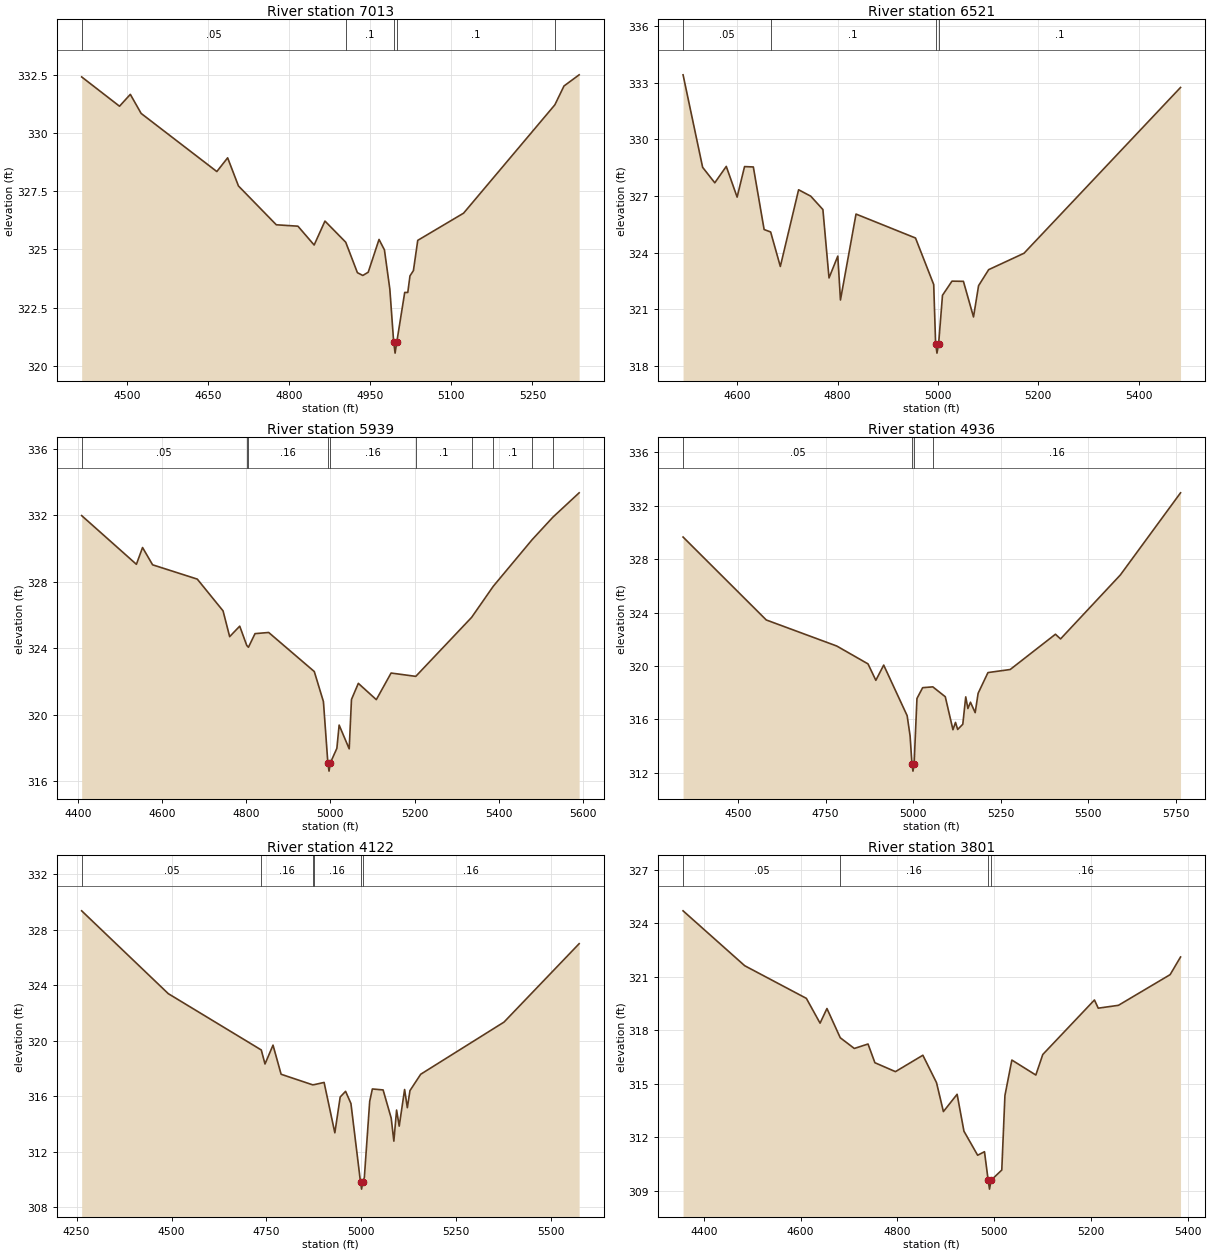
Type RM Length L Ch R = 1 ,7013    ,492,492,492
BEGIN DESCRIPTION:
UNT1439 IN WICK 11.0
END DESCRIPTION:
XS GIS Cut Line= 3
      3567642.11     10288391.62      3567642.11     10287791.64
      3567442.13     10287541.67
#Sta/Elev= 30
  4416.2  332.42  4486.2  331.16  4506.2  331.67  4526.2  330.85  4666.2  328.35
  4686.2  328.94  4706.2  327.73  4776.2  326.06  4816.2     326  4846.2  325.19
  4866.2  326.22  4904.6  325.31  4926.2     324  4936.2  323.88  4946.2  324.02
  4966.2  325.43  4976.2  324.98  4986.2  323.29  4993.2  321.04  4995.9  320.54
  4999.2  321.04  5013.7  323.15  5019.4  323.15  5023.4  323.86  5029.8  324.09
  5037.8  325.39  5122.6  326.56  5291.4  331.22  5308.3  332.03  5336.3  332.51
#Mann= 5 ,-1 , 0
  4416.2     .05       0  4904.6      .1       0  4993.2     .07       0
  4999.2      .1       0  5291.4     .16       0
Bank Sta=4993.2,4999.2
XS Rating Curve= 0 ,0
Exp/Cntr=0.3,0.1

Type RM Length L Ch R = 1 ,6521    ,582,582,582
BEGIN DESCRIPTION:
UNT1439 IN WICK 10.0
END DESCRIPTION:
XS GIS Cut Line= 3
      3568242.09      10288241.6      3568042.11     10287741.64
      3567992.11     10287291.69
#Sta/Elev= 30
  4492.1  333.43  4531.1  328.52  4555.3   327.7  4578.2  328.57  4599.8  326.94
  4614.6  328.56  4632.1  328.54  4653.6  325.22  4666.6  325.09  4685.9  323.26
  4722.3  327.33  4746.5  326.99  4770.7  326.28  4782.9  322.65  4800.4  323.81
  4805.7  321.48  4836.7  326.04  4955.2  324.77  4991.5   322.3  4995.3  319.16
    4998  318.66  5001.3  319.16    5009  321.73  5027.9  322.48  5050.7  322.47
  5070.8  320.58  5080.9  322.24    5101  323.09  5171.4  323.96  5483.3  332.76
#Mann= 4 ,-1 , 0
  4492.1     .05       0  4666.6      .1       0  4995.3     .07       0
  5001.3      .1       0
Bank Sta=4995.3,5001.3
XS Rating Curve= 0 ,0
Exp/Cntr=0.3,0.1

Type RM Length L Ch R = 1 ,5939    ,1003,1003,1003
BEGIN DESCRIPTION:
UNT1439 IN WICK 9.0
END DESCRIPTION:
XS GIS Cut Line= 3
       3568642.1     10288191.64      3568392.11     10287591.64
      3568042.11     10287191.64
#Sta/Elev= 30
  4409.3  331.99  4539.3  329.06  4553.9  330.07  4577.8  329.03  4683.9  328.17
  4745.1  326.26  4760.8  324.71  4784.7  325.34  4801.4  324.18  4805.4  324.07
    4821  324.89  4853.5  324.96  4961.8  322.61  4983.5   320.8    4994  317.12
  4996.8  316.62    5000  317.12  5015.4  317.99  5020.8  319.39  5044.7  317.96
  5050.1  320.93  5066.4   321.9  5109.1  320.92  5144.2  322.52  5202.8  322.32
  5335.5  325.87  5386.9  327.74  5479.1  330.54  5528.3  331.89  5590.8  333.36
#Mann= 10 ,-1 , 0
  4409.3     .05       0  4801.4      .1       0  4805.4     .16       0
    4994     .07       0    5000     .16       0  5202.8      .1       0
  5335.5     .16       0  5386.9      .1       0  5479.1     .16       0
  5528.3      .1       0
Bank Sta=4994,5000
XS Rating Curve= 0 ,0
Exp/Cntr=0.3,0.1

Type RM Length L Ch R = 1 ,4936    ,814,814,814
BEGIN DESCRIPTION:
UNT1439 IN WICK 8.0
END DESCRIPTION:
XS GIS Cut Line= 3
      3569642.08     10287541.63      3569042.11     10287241.64
       3568442.1     10286791.64
#Sta/Elev= 30
    4343  329.66  4580.6  323.45  4781.8   321.5  4871.2  320.16  4893.6  318.93
    4916  320.07    4983  316.28  4991.4  314.77  4996.8  312.63  4999.6  312.13
  5002.8  312.63    5011  317.57  5027.3  318.38  5056.3  318.44  5091.9   317.7
  5113.8  315.23  5121.1  315.78  5127.3  315.25  5141.9  315.64  5150.3  317.69
  5156.5  316.82  5163.8  317.29  5177.3  316.51  5185.7  317.96  5213.8  319.51
  5277.3  319.74  5406.5  322.38  5421.1  322.03  5591.9  326.82  5763.8  332.97
#Mann= 4 ,-1 , 0
    4343     .05       0  4996.8     .03       0  5002.8     .05       0
  5056.3     .16       0
Bank Sta=4996.8,5002.8
XS Rating Curve= 0 ,0
Exp/Cntr=0.3,0.1

Type RM Length L Ch R = 1 ,4122    ,321,321,321
BEGIN DESCRIPTION:
UNT1439 IN WICK 7.0
END DESCRIPTION:
XS GIS Cut Line= 2
      3569736.09     10287420.28      3568822.89     10286481.04
#Sta/Elev= 30
  4263.3  329.35  4491.4  323.38  4736.3  319.32  4746.1  318.31  4767.2  319.67
  4788.5  317.57  4871.3  316.81  4875.6  316.82  4901.7  316.98    4930  313.35
  4944.1  315.93  4958.3  316.34  4972.4  315.46  4997.6  309.79  5000.4  309.29
  5003.6  309.79  5007.7  310.13  5021.8  315.62  5028.8  316.51  5057.1  316.44
  5078.4  314.41  5085.4  312.75  5092.6  314.99  5099.5  313.83  5113.7  316.47
  5120.9  315.16  5127.8  316.39  5156.1  317.57  5375.5  321.33  5573.3  326.98
#Mann= 6 ,-1 , 0
  4263.3     .05       0  4736.3     .16       0  4871.3     .05       0
  4875.6     .16       0  4997.6     .07       0  5003.6     .16       0
Bank Sta=4997.6,5003.6
XS Rating Curve= 0 ,0
Exp/Cntr=0.3,0.1

Type RM Length L Ch R = 1 ,3801    ,648,648,648
BEGIN DESCRIPTION:
UNT1439 IN WICK 6.0
END DESCRIPTION:
XS GIS Cut Line= 3
      3569742.09     10287141.63      3569292.11     10286691.64
       3568992.1     10286441.64
#Sta/Elev= 30
  4357.4  324.71  4484.7  321.63  4611.9   319.8  4640.2  318.41  4654.4  319.23
  4681.9  317.59  4710.9  316.99  4739.2  317.24  4753.4  316.19  4795.8  315.69
  4852.4  316.61  4880.6  315.07  4894.8  313.45  4923.1  314.42  4937.2  312.35
  4965.5     311  4979.6   311.2  4987.2   309.6    4990   309.1  4993.2   309.6
  5015.3  310.17  5021.8  314.35  5036.1  316.34  5085.6   315.5  5099.9  316.65
  5206.6  319.71  5214.4  319.25  5256.1  319.41  5362.8  321.13  5384.3  322.12
#Mann= 4 ,-1 , 0
  4357.4     .05       0  4681.9     .16       0  4987.2     .07       0
  4993.2     .16       0
Bank Sta=4987.2,4993.2
XS Rating Curve= 0 ,0
Exp/Cntr=0.3,0.1

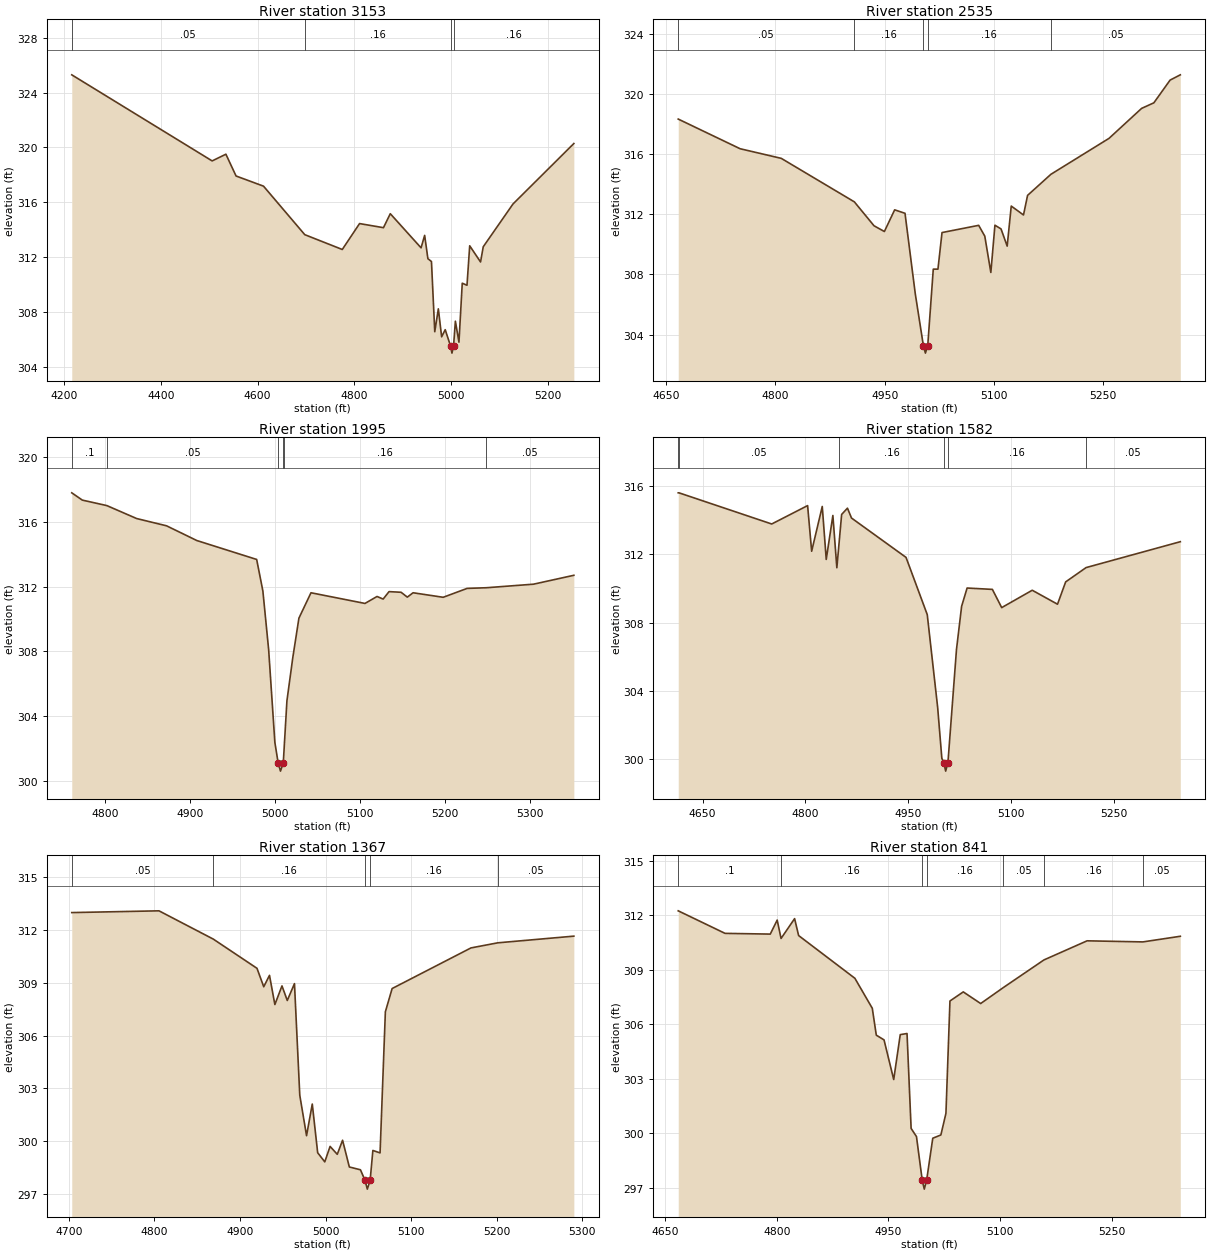
Type RM Length L Ch R = 1 ,3153    ,618,618,618
BEGIN DESCRIPTION:
UNT1439 IN WICK 5.0
END DESCRIPTION:
XS GIS Cut Line= 3
      3569992.11     10286941.64      3569442.11     10286341.64
      3569242.15     10286241.66
#Sta/Elev= 30
  4215.9   325.3    4506  319.02  4534.4  319.51  4555.4  317.92  4612.1  317.18
  4697.4  313.64  4774.9  312.56  4810.6  314.45    4860  314.15  4874.1  315.17
  4937.7  312.68  4945.1  313.59  4951.8  311.89  4959.2  311.68    4966  306.56
  4973.4  308.23  4980.2  306.19  4987.6  306.71  4998.8   305.5  5001.5     305
  5004.8   305.5  5008.6  307.33    5016   305.8  5022.8   310.1  5032.6  309.95
  5038.2  312.83  5060.6  311.65  5066.2  312.76  5127.7  315.88  5253.4  320.29
#Mann= 4 ,-1 , 0
  4215.9     .05       0  4697.4     .16       0  4998.8     .07       0
  5004.8     .16       0
Bank Sta=4998.8,5004.8
XS Rating Curve= 0 ,0
Exp/Cntr=0.3,0.1

Type RM Length L Ch R = 1 ,2535    ,540,540,540
BEGIN DESCRIPTION:
UNT1439 IN WICK 4.0
END DESCRIPTION:
XS GIS Cut Line= 3
      3569992.12     10286391.66      3569742.11     10286141.64
      3569442.09     10285991.64
#Sta/Elev= 30
  4666.7  318.32  4751.6  316.35  4808.1  315.71  4908.4  312.82  4935.4  311.23
  4949.6  310.85  4963.7  312.29  4977.9  312.06    4992  306.71  5003.1  303.27
  5005.9  302.77  5009.1  303.27  5016.7  308.35  5023.1  308.35  5028.7  310.78
    5079  311.26  5087.4  310.54  5095.7  308.13  5101.3  311.27  5109.7  311.02
  5118.1  309.88  5123.7  312.54  5140.5  311.95  5146.1  313.25  5178.1  314.65
  5257.9  317.04  5302.6  319.03  5319.4   319.4  5341.7  320.91  5355.7  321.26
#Mann= 5 ,-1 , 0
  4666.7     .05       0  4908.4     .16       0  5003.1     .07       0
  5009.1     .16       0  5178.1     .05       0
Bank Sta=5003.1,5009.1
XS Rating Curve= 0 ,0
Exp/Cntr=0.3,0.1

Type RM Length L Ch R = 1 ,1995    ,413,413,413
BEGIN DESCRIPTION:
UNT1439 IN WICK 3.0
END DESCRIPTION:
XS GIS Cut Line= 2
      3570262.34     10286179.09      3569856.59     10285749.94
#Sta/Elev= 30
  4760.7   317.8  4773.1  317.35    4802  317.01    4837  316.21  4872.2  315.76
  4907.8  314.85  4978.2  313.68  4985.5  311.73  4992.3   308.1  4999.6  302.37
  5003.5  301.09  5006.2  300.59  5009.5  301.09  5010.1  301.63  5013.8  304.94
  5020.7  307.61  5027.9  310.05  5042.1  311.62  5105.6  310.96  5119.8  311.39
    5127  311.23  5133.9  311.69  5148.1  311.65  5155.4  311.35  5162.2  311.62
  5197.6  311.34  5225.8  311.89  5248.3  311.93  5303.8  312.15  5351.3   312.7
#Mann= 6 ,-1 , 0
  4760.7      .1       0    4802     .05       0  5003.5    .035       0
  5009.5     .05       0  5010.1     .16       0  5248.3     .05       0
Bank Sta=5003.5,5009.5
XS Rating Curve= 0 ,0
Exp/Cntr=0.3,0.1

Type RM Length L Ch R = 1 ,1582    ,215,215,215
BEGIN DESCRIPTION:
Mapping XS 64f7cbab
END DESCRIPTION:
XS GIS Cut Line= 2
      3570336.22     10286075.93      3569957.32     10285448.34
#Sta/Elev= 30
  4614.4  315.62  4615.5  315.62  4750.9  313.79  4803.3  314.87  4809.2  312.19
  4824.7  314.82  4830.5  311.71  4840.2  314.29    4846  311.22  4849.4  312.74
    4853  314.35  4861.5  314.72  4867.4  314.14    4947  311.83    4978  308.47
  4993.2  303.02  4999.3  300.03  5002.2  299.78  5004.9  299.28  5008.2  299.78
  5020.7  306.43  5028.2  308.96  5036.2  310.03  5073.1  309.95  5086.7  308.88
  5131.3   309.9  5168.2  309.08  5180.1  310.39  5209.9  311.23  5347.5  312.75
#Mann= 6 ,-1 , 0
  4614.4      .1       0  4615.5     .05       0  4849.4     .16       0
  5002.2     .07       0  5008.2     .16       0  5209.9     .05       0
Bank Sta=5002.2,5008.2
XS Rating Curve= 0 ,0
Exp/Cntr=0.3,0.1

Type RM Length L Ch R = 1 ,1367    ,526,526,526
BEGIN DESCRIPTION:
UNT1439 IN WICK 2.0
END DESCRIPTION:
XS GIS Cut Line= 2
      3570386.01     10285821.06      3570034.02     10285351.81
#Sta/Elev= 30
  4703.4     313  4805.3   313.1  4868.8  311.49  4919.8  309.83  4927.7  308.78
  4934.4  309.43  4940.7  307.77    4949  308.83  4955.2     308  4963.6  308.96
  4969.8  302.61  4977.7  300.31  4984.4  302.11  4990.7  299.34    4999  298.82
  5005.2   299.7  5013.6  299.25  5019.8  300.05  5027.7  298.53  5040.7  298.37
    5046  297.77  5048.7  297.27    5052  297.77  5055.2  299.47  5063.6  299.33
  5069.8  307.36  5077.7  308.68  5169.8  310.99  5201.1  311.28    5290  311.66
#Mann= 5 ,-1 , 0
  4703.4     .05       0  4868.8     .16       0    5046     .07       0
    5052     .16       0  5201.1     .05       0
Bank Sta=5046,5052
XS Rating Curve= 0 ,0
Exp/Cntr=0.3,0.1

Type RM Length L Ch R = 1 ,841     ,0,0,0
BEGIN DESCRIPTION:
UNT1439 IN WICK 1.0
END DESCRIPTION:
XS GIS Cut Line= 2
      3570735.43     10285511.55      3570117.37     10285240.71
#Sta/Elev= 30
  4667.6  312.24  4730.5     311  4791.3  310.96  4800.6  311.73  4805.8  310.72
    4824  311.81  4829.4  310.88    4905  308.53  4928.4  306.88  4933.8   305.4
  4944.2  305.14  4957.2  302.96    4966  305.43  4975.1  305.49  4980.6  300.27
  4987.8  299.82  4995.5  297.43  4998.3  296.93  5001.5  297.43  5009.7  299.73
  5020.6  299.91  5027.4   301.1  5032.8  307.28  5050.7  307.78  5074.1  307.14
  5104.6  308.02  5159.2  309.54  5217.1  310.59  5292.1  310.53  5342.4  310.84
#Mann= 7 ,-1 , 0
  4667.6      .1       0  4805.8     .16       0  4995.5     .07       0
  5001.5     .16       0  5104.6     .05       0  5159.2     .16       0
  5292.1     .05       0
Bank Sta=4995.5,5001.5
XS Rating Curve= 0 ,0
Exp/Cntr=0.3,0.1

Chan Stop Cuts=-1
Use User Specified Reach Order=0
Composite Channel Slope=5