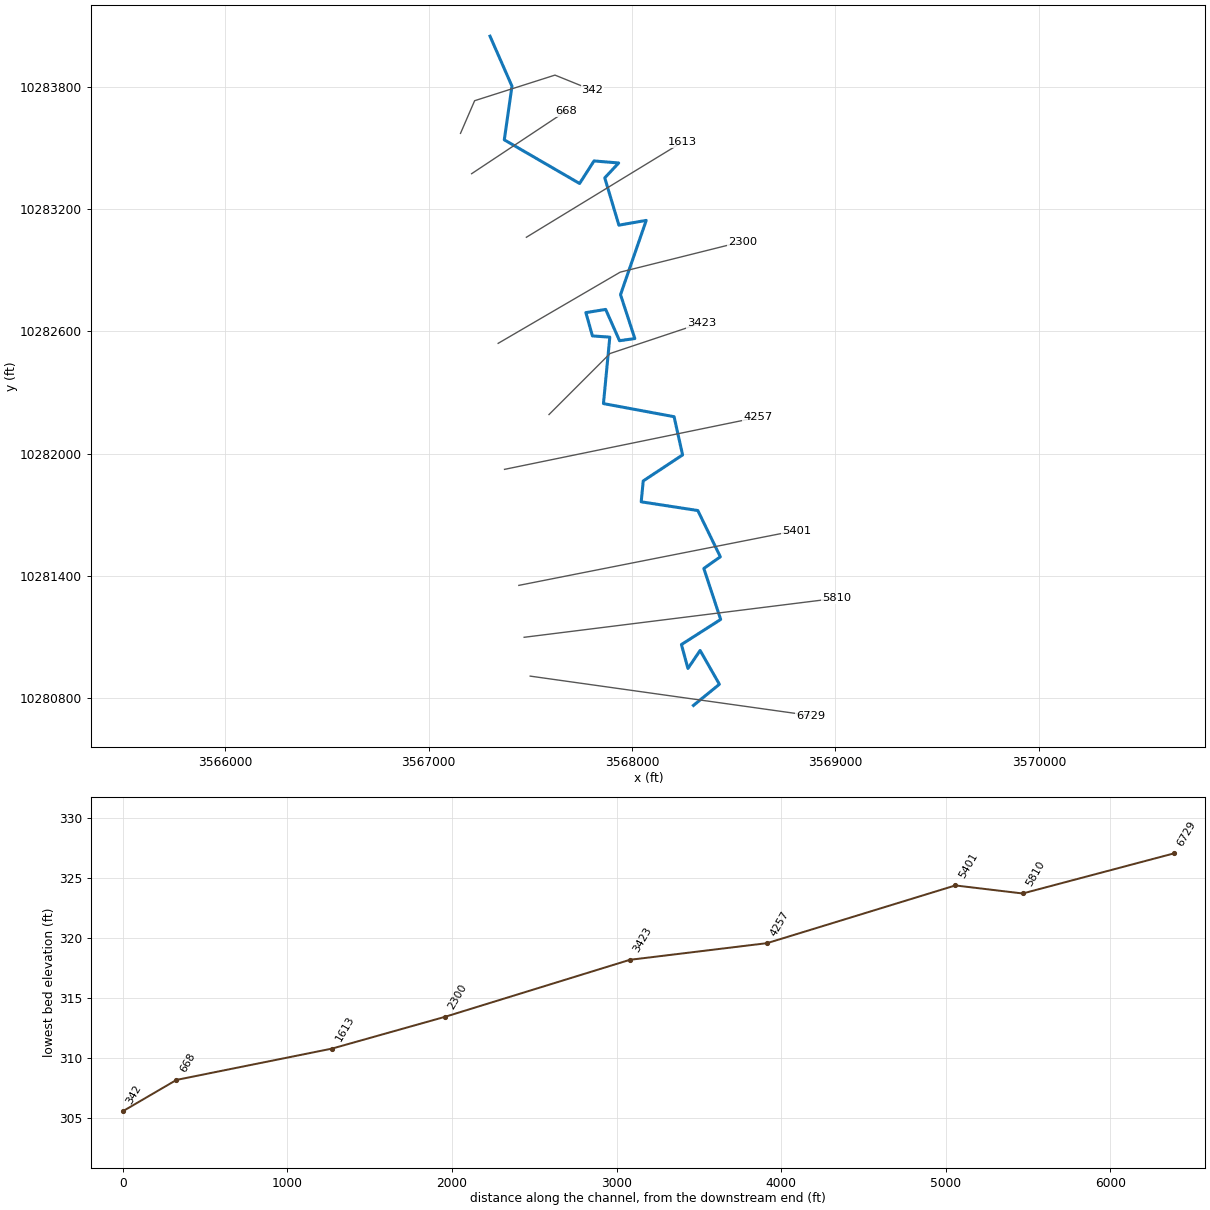
--- SANDCREEKTRIB17.prj (project) ---

Proj Title=SAND CREEK TRIB 17
Current Plan=p01
Default Exp/Contr=0.3,0.1
English Units
Geom File=g01
Flow File=f01
Plan File=p01
Y Axis Title=Elevation
X Axis Title(PF)=Main Channel Distance
X Axis Title(XS)=Station
BEGIN DESCRIPTION:
UNT1438 IN WICK
END DESCRIPTION:
DSS Export Rating Curves= 0
DSS Export Rating Curve Sorted= 0
DSS Export Volume Flow Curves= 0
DXF Filename=UNT1438 IN WICK.
DXF OffsetX= 0
DXF OffsetY= 0
DXF ScaleX= 1
DXF ScaleY= 10

--- SANDCREEKTRIB17.p01 (plan) ---

Plan Title=Multiple Run
Short Identifier=Multiple
Geom File=g01
Flow File=f01
Subcritical Flow
K Sum by GR= 0
Std Step Tol= 0.01
Critical Tol= 0.01
Num of Std Step Trials= 20
Max Error Tol= 0.3
Flow Tol Ratio= 0.001
Split Flow NTrial= 30
Split Flow Tol= 0.02
Split Flow Ratio= 0.02
Log Output Level= 0
Friction Slope Method= 1
Unsteady Friction Slope Method= 2
Unsteady Bridges Friction Slope Method= 1
Parabolic Critical Depth
Global Vel Dist=  1 , 1 , 1
Global Log Level= 0
CheckData=True
Encroach Param= -1, 0, 0, 0
BEGIN DESCRIPTION:
Multiple Run
END DESCRIPTION:

--- SANDCREEKTRIB17.f01 (steady flow) ---

Flow Title=Multiple
Program Version=4.10
Number of Profiles= 7
Profile Names=10-year,25-year,50-year,1pct_min,100-year,1pct_plu,500-year
River Rch & RM=UNT1438 IN WICK,Reach-1         ,6729
     427     562     670     586     792    1072    1110
River Rch & RM=SANDCREEKTRIB17,Reach-1         ,6729
     427     562     670     586     792    1072    1110
Boundary for River Rch & Prof#=SANDCREEKTRIB17,Reach-1         , 1
Up Type= 0
Dn Type= 3
Dn Slope=0.005
Boundary for River Rch & Prof#=SANDCREEKTRIB17,Reach-1         , 2
Up Type= 0
Dn Type= 3
Dn Slope=0.005
Boundary for River Rch & Prof#=SANDCREEKTRIB17,Reach-1         , 3
Up Type= 0
Dn Type= 3
Dn Slope=0.005
Boundary for River Rch & Prof#=SANDCREEKTRIB17,Reach-1         , 4
Up Type= 0
Dn Type= 3
Dn Slope=0.005
Boundary for River Rch & Prof#=SANDCREEKTRIB17,Reach-1         , 5
Up Type= 0
Dn Type= 3
Dn Slope=0.005
Boundary for River Rch & Prof#=SANDCREEKTRIB17,Reach-1         , 6
Up Type= 0
Dn Type= 3
Dn Slope=0.005
Boundary for River Rch & Prof#=SANDCREEKTRIB17,Reach-1         , 7
Up Type= 0
Dn Type= 3
Dn Slope=0.005
DSS Import GetInterval= 0
DSS Import GetPeak= 0
DSS Import FillOption= 0

--- SANDCREEKTRIB17.g01 (geometry) ---

Geom Title=Existing Conditions
Program Version=4.10

River Reach=SANDCREEKTRIB17 ,Reach-1
Reach XY= 30
      3568302.11     10280761.64      3568429.68     10280865.58
      3568334.91     10281031.86      3568275.01     10280943.32
      3568243.04     10281060.91      3568436.02      10281184.3
      3568353.17     10281434.94       3568434.3     10281492.37
      3568323.62      10281719.8      3568045.27     10281762.64
      3568055.38     10281865.29      3568248.71     10281993.14
      3568206.93     10282181.03      3567859.78     10282245.48
      3567890.94     10282572.08      3567805.46     10282578.11
      3567773.43      10282692.7       3567870.7     10282708.45
      3567938.71     10282554.62      3568013.97     10282565.22
      3567943.64     10282780.95      3568070.09     10283146.04
      3567935.62     10283122.62      3567866.17     10283355.19
      3567934.65     10283428.28      3567813.34     10283438.33
      3567742.41     10283327.51      3567372.23     10283542.13
      3567409.97      10283805.9      3567302.11     10284051.64

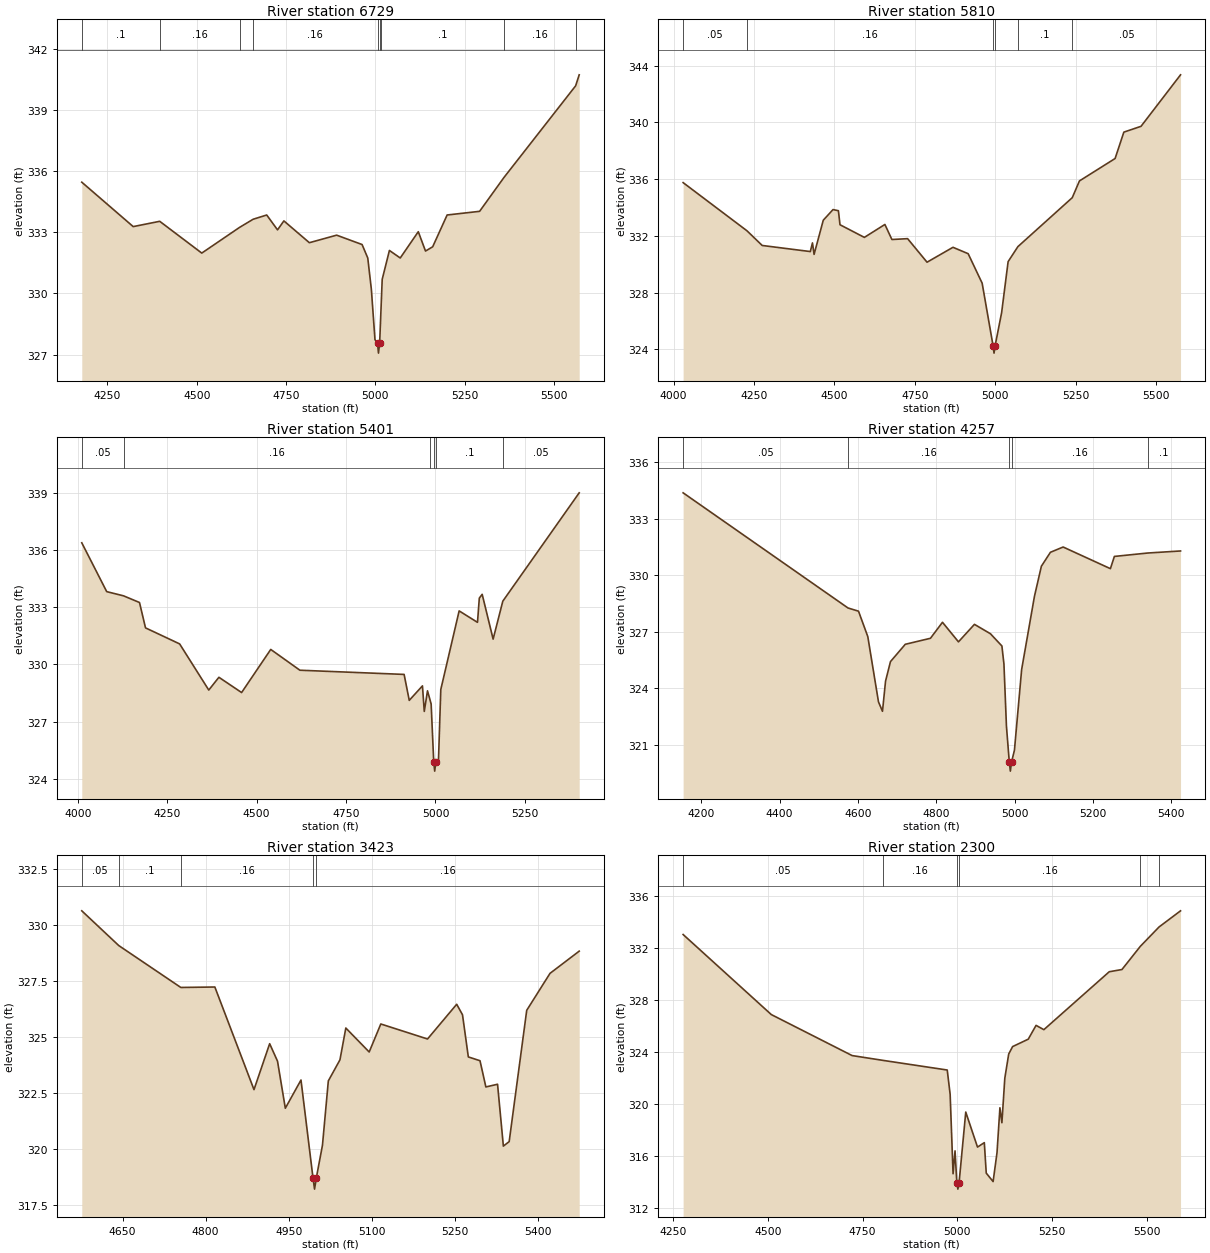
Type RM Length L Ch R = 1 ,6729    ,919,919,919
BEGIN DESCRIPTION:
UNT1438 IN WICK 9.0
END DESCRIPTION:
XS GIS Cut Line= 2
      3567499.62     10280905.73      3568878.07     10280711.99
#Sta/Elev= 30
  4178.3  335.46  4322.2  333.28  4396.4  333.54  4514.1  331.98  4619.7  333.24
  4657.7  333.64  4695.8  333.85  4726.1  333.12  4743.9  333.56  4815.2  332.49
  4891.5  332.86  4962.7   332.4  4978.6  331.74  4988.7   330.2  4998.8  327.73
  5005.9  327.57  5008.6  327.07  5011.9  327.57  5015.6   329.2    5019  330.69
  5039.2  332.11  5069.5  331.74    5120  333.03  5140.2  332.08  5160.3  332.29
  5200.7  333.85  5291.6  334.03  5359.7  335.69  5560.3  340.19  5570.3  340.73
#Mann= 9 ,-1 , 0
  4178.3      .1       0  4396.4     .16       0  4619.7      .1       0
  4657.7     .16       0  5005.9     .07       0  5011.9     .16       0
  5015.6      .1       0  5359.7     .16       0  5560.3      .1       0
Bank Sta=5005.9,5011.9
XS Rating Curve= 0 ,0
Exp/Cntr=0.3,0.1

Type RM Length L Ch R = 1 ,5810    ,409,409,409
BEGIN DESCRIPTION:
UNT1438 IN WICK 8.0
END DESCRIPTION:
XS GIS Cut Line= 2
      3567469.83     10281096.62      3569003.91     10281288.25
#Sta/Elev= 30
  4029.9  335.75  4228.6  332.35  4275.6  331.32  4425.2  330.89  4431.9   331.5
  4436.9  330.69  4465.5   333.1  4495.8  333.85  4512.5  333.77  4517.5  332.78
  4593.2  331.89    4657   332.8  4678.8  331.74  4727.6   331.8    4788  330.14
  4868.6  331.19  4915.8  330.74  4959.3  328.66  4993.4  324.23  4996.2  323.73
  4999.4  324.23  5019.8  326.58    5040  330.18  5070.5  331.24  5239.4  334.69
  5261.7  335.87  5372.5  337.45  5399.7  339.31  5453.1  339.72  5575.9  343.35
#Mann= 6 ,-1 , 0
  4029.9     .05       0  4228.6     .16       0  4993.4     .07       0
  4999.4     .16       0  5070.5      .1       0  5239.4     .05       0
Bank Sta=4993.4,4999.4
XS Rating Curve= 0 ,0
Exp/Cntr=0.3,0.1

Type RM Length L Ch R = 1 ,5401    ,1144,1144,1144
BEGIN DESCRIPTION:
UNT1438 IN WICK 7.0
END DESCRIPTION:
XS GIS Cut Line= 2
      3567443.72     10281351.82      3568808.26     10281621.34
#Sta/Elev= 30
    4011  336.37  4080.7  333.81  4127.7  333.59  4172.4  333.24  4189.2  331.91
  4284.6  331.07  4366.1  328.65  4394.4  329.32  4457.9  328.52  4539.4  330.78
  4620.9  329.69  4912.3  329.47  4926.7  328.11  4963.6  328.87  4968.7  327.53
  4977.7  328.61  4984.1  328.18  4987.9  327.92  4995.1   324.9  4997.8   324.4
  5001.1   324.9  5008.3  324.92  5014.9  328.68  5066.2   332.8  5117.5   332.2
  5122.6  333.47  5130.6  333.67  5161.2  331.32  5188.3  333.31  5401.9  338.99
#Mann= 6 ,-1 , 0
    4011     .05       0  4127.7     .16       0  4984.1      .1       0
  4995.1     .07       0  5001.1      .1       0  5188.3     .05       0
Bank Sta=4995.1,5001.1
XS Rating Curve= 0 ,0
Exp/Cntr=0.3,0.1

Type RM Length L Ch R = 1 ,4257    ,834,834,834
BEGIN DESCRIPTION:
UNT1438 IN WICK 6.0
END DESCRIPTION:
XS GIS Cut Line= 2
      3567373.48     10281922.15      3568617.52     10282177.63
#Sta/Elev= 30
  4153.9  334.38  4574.9  328.26  4601.7  328.09  4625.4  326.74  4652.7  323.27
  4662.9  322.77  4670.7  324.37  4683.3  325.41  4721.1  326.33  4785.4  326.65
  4816.1   327.5  4856.9  326.46  4897.7  327.39  4938.6  326.89  4967.8  326.24
    4973  325.28  4979.4  321.98  4986.6  320.09  4989.4  319.59  4992.6  320.09
  4999.8   320.7  5018.2  324.99  5050.9  328.88  5068.6  330.48  5091.7  331.22
  5124.1   331.5  5244.8  330.35    5255     331  5339.6  331.18  5423.9  331.29
#Mann= 5 ,-1 , 0
  4153.9     .05       0  4574.9     .16       0  4986.6     .07       0
  4992.6     .16       0  5339.6      .1       0
Bank Sta=4986.6,4992.6
XS Rating Curve= 0 ,0
Exp/Cntr=0.3,0.1

Type RM Length L Ch R = 1 ,3423    ,1123,1123,1123
BEGIN DESCRIPTION:
UNT1438 IN WICK 5.0
END DESCRIPTION:
XS GIS Cut Line= 3
      3567592.09     10282191.63      3567892.11     10282491.64
      3568342.08     10282641.63
#Sta/Elev= 30
  4576.2  330.62    4643  329.07  4755.1   327.2  4816.6  327.22  4887.3  322.64
  4915.6  324.69  4929.8  323.91  4943.9  321.81  4972.2  323.07  4993.9   318.7
  4996.7   318.2  4999.9   318.7    5011  320.16  5021.6  323.03  5042.6  323.97
  5053.2  325.39  5095.4  324.32  5116.4  325.57  5200.8   324.9  5253.5  326.45
    5264  325.98  5274.5   324.1  5295.6  323.93  5306.2  322.76  5327.3  322.88
  5337.8  320.12  5348.3  320.32    5380  326.18  5422.1  327.83  5474.8  328.82
#Mann= 5 ,-1 , 0
  4576.2     .05       0    4643      .1       0  4755.1     .16       0
  4993.9     .07       0  4999.9     .16       0
Bank Sta=4993.9,4999.9
XS Rating Curve= 0 ,0
Exp/Cntr=0.3,0.1

Type RM Length L Ch R = 1 ,2300    ,687,687,687
BEGIN DESCRIPTION:
UNT1438 IN WICK 4.0
END DESCRIPTION:
XS GIS Cut Line= 3
      3567342.13     10282541.66      3567942.11     10282891.64
      3568542.15     10283041.65
#Sta/Elev= 30
  4276.2  333.01    4509  326.86  4722.3  323.71    4804  323.34  4973.4   322.6
  4981.1  320.73  4988.8  314.63    4994  316.39  4998.7  313.95  5001.5  313.45
  5004.7  313.95  5022.3  319.37  5053.3  316.68  5071.3  317.02  5076.4  314.68
  5094.5  314.03  5104.8  316.25  5112.5   319.7  5117.7  318.55  5125.4  321.97
  5135.7  323.83    5146   324.4  5187.3  324.97  5207.9  326.03  5228.5   325.7
  5401.1  330.15  5434.6  330.32  5483.1   332.1  5532.6  333.59  5589.3  334.83
#Mann= 6 ,-1 , 0
  4276.2     .05       0    4804     .16       0  4998.7     .07       0
  5004.7     .16       0  5483.1      .1       0  5532.6     .16       0
Bank Sta=4998.7,5004.7
XS Rating Curve= 0 ,0
Exp/Cntr=0.3,0.1

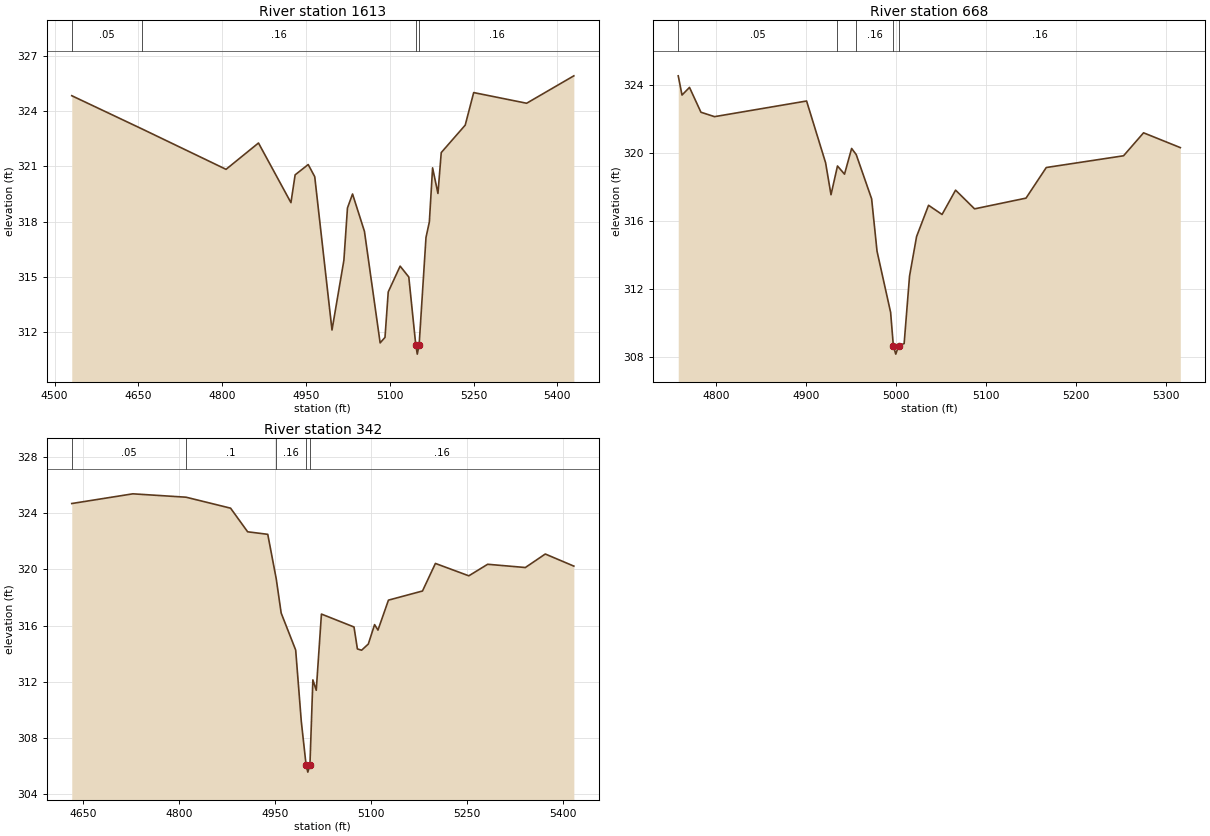
Type RM Length L Ch R = 1 ,1613    ,945,945,945
BEGIN DESCRIPTION:
UNT1438 IN WICK 3.0
END DESCRIPTION:
XS GIS Cut Line= 2
      3567480.77     10283063.12      3568248.11     10283531.32
#Sta/Elev= 30
  4530.6  324.84    4656  323.04  4806.8  320.84  4864.9  322.27    4923  319.03
  4930.5  320.54  4953.9   321.1  4965.6  320.44  4996.5  312.11  5017.8   315.9
  5024.2  318.74  5033.3   319.5  5054.6  317.47  5082.7  311.41  5091.4  311.71
  5097.2  314.18  5118.5  315.58    5134  314.99  5146.5   311.3  5149.2   310.8
  5152.5   311.3  5164.8  317.14  5170.8  317.98  5176.6  320.92  5186.2  319.53
  5192.1  321.75    5235  323.24  5250.2  325.01    5345  324.43  5429.5  325.92
#Mann= 4 ,-1 , 0
  4530.6     .05       0    4656     .16       0  5146.5     .07       0
  5152.5     .16       0
Bank Sta=5146.5,5152.5
XS Rating Curve= 0 ,0
Exp/Cntr=0.3,0.1

Type RM Length L Ch R = 1 ,668     ,326,326,326
BEGIN DESCRIPTION:
UNT1438 IN WICK 2.0
END DESCRIPTION:
XS GIS Cut Line= 2
      3567211.67     10283375.61      3567676.12      10283683.8
#Sta/Elev= 30
  4758.2  324.55  4762.4  323.42  4770.7  323.87  4783.4  322.41  4798.5  322.15
  4900.7  323.07  4921.8  319.44  4927.8  317.56    4935  319.25  4942.8  318.77
  4950.7  320.28  4955.8  319.92  4972.9  317.32  4978.9  314.24    4994  310.64
    4997  308.69  4999.7  308.19    5003  308.69    5009  308.81    5015  312.78
  5022.8   315.1  5036.1  316.94  5051.1   316.4  5066.1  317.83  5087.2  316.73
  5144.3  317.36  5166.8  319.16  5252.6  319.85  5274.8   321.2  5315.6  320.33
#Mann= 5 ,-1 , 0
  4758.2     .05       0    4935      .1       0  4955.8     .16       0
    4997     .07       0    5003     .16       0
Bank Sta=4997,5003
XS Rating Curve= 0 ,0
Exp/Cntr=0.3,0.1

Type RM Length L Ch R = 1 ,342     ,0,0,0
BEGIN DESCRIPTION:
UNT1438 IN WICK 1.0
END DESCRIPTION:
XS GIS Cut Line= 4
      3567157.03     10283573.87      3567226.46     10283734.43
      3567621.42      10283860.3      3567803.51      10283786.6
#Sta/Elev= 30
  4631.7  324.68  4727.3  325.37  4810.6  325.13  4880.3  324.35    4907  322.67
  4938.5  322.49  4951.7  319.34  4959.5  316.89  4982.2  314.26    4991  309.18
  4998.5  306.08  5001.2  305.58  5004.5  306.08  5009.1  312.14  5014.4   311.4
  5022.5  316.82  5073.5   315.9  5078.8  314.34  5085.4  314.25  5095.9  314.69
  5105.7  316.07    5111  315.68  5127.4  317.81  5180.7  318.46  5200.9  320.42
  5253.2  319.54  5282.7  320.36  5341.7  320.13  5372.9  321.09  5417.6  320.23
#Mann= 5 ,-1 , 0
  4631.7     .05       0  4810.6      .1       0  4951.7     .16       0
  4998.5     .07       0  5004.5     .16       0
Bank Sta=4998.5,5004.5
XS Rating Curve= 0 ,0
Exp/Cntr=0.3,0.1

Chan Stop Cuts=-1
Use User Specified Reach Order=0
Composite Channel Slope=5