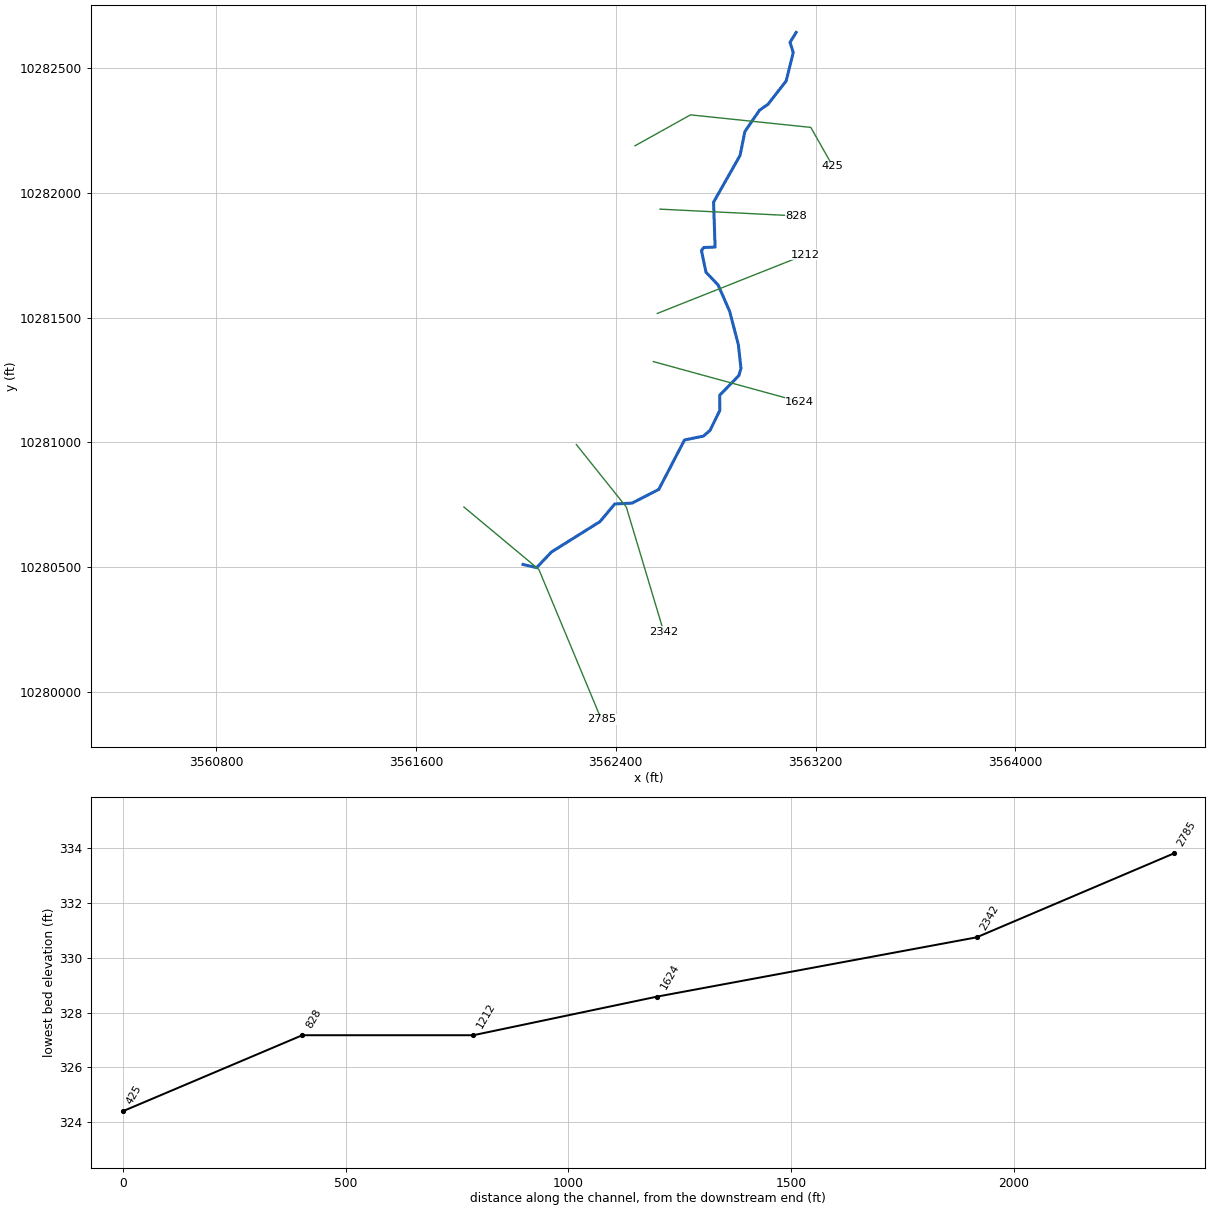
--- SANDCREEKTRIB19.prj (project) ---

Proj Title=SAND CREEK TRIB 19
Current Plan=p01
Default Exp/Contr=0.3,0.1
English Units
Geom File=g01
Flow File=f01
Plan File=p01
Y Axis Title=Elevation
X Axis Title(PF)=Main Channel Distance
X Axis Title(XS)=Station
BEGIN DESCRIPTION:
UNT1437 IN WICK
END DESCRIPTION:
DSS Export Rating Curves= 0
DSS Export Rating Curve Sorted= 0
DSS Export Volume Flow Curves= 0
DXF Filename=UNT1437 IN WICK.
DXF OffsetX= 0
DXF OffsetY= 0
DXF ScaleX= 1
DXF ScaleY= 10

--- SANDCREEKTRIB19.p01 (plan) ---

Plan Title=Multiple Run
Short Identifier=Multiple
Geom File=g01
Flow File=f01
Subcritical Flow
K Sum by GR= 0
Std Step Tol= 0.01
Critical Tol= 0.01
Num of Std Step Trials= 20
Max Error Tol= 0.3
Flow Tol Ratio= 0.001
Split Flow NTrial= 30
Split Flow Tol= 0.02
Split Flow Ratio= 0.02
Log Output Level= 0
Friction Slope Method= 1
Unsteady Friction Slope Method= 2
Unsteady Bridges Friction Slope Method= 1
Parabolic Critical Depth
Global Vel Dist=  1 , 1 , 1
Global Log Level= 0
CheckData=True
Encroach Param= -1, 0, 0, 0
BEGIN DESCRIPTION:
Multiple Run
END DESCRIPTION:

--- SANDCREEKTRIB19.f01 (steady flow) ---

Flow Title=Multiple
Program Version=4.10
Number of Profiles= 7
Profile Names=10-year,25-year,50-year,1pct_min,100-year,1pct_plu,500-year
River Rch & RM=UNT1437 IN WICK,Reach-1         ,2785
     261     331     385     328     444     600     591
River Rch & RM=D CREEK TRIB 19,Reach-1         ,2785
     261     331     385     328     444     600     591
River Rch & RM=SANDCREEKTRIB19,Reach-1         ,2785
     261     331     385     328     444     600     591
Boundary for River Rch & Prof#=SANDCREEKTRIB19,Reach-1         , 1
Up Type= 0
Dn Type= 3
Dn Slope=0.005
Boundary for River Rch & Prof#=SANDCREEKTRIB19,Reach-1         , 2
Up Type= 0
Dn Type= 3
Dn Slope=0.005
Boundary for River Rch & Prof#=SANDCREEKTRIB19,Reach-1         , 3
Up Type= 0
Dn Type= 3
Dn Slope=0.005
Boundary for River Rch & Prof#=SANDCREEKTRIB19,Reach-1         , 4
Up Type= 0
Dn Type= 3
Dn Slope=0.005
Boundary for River Rch & Prof#=SANDCREEKTRIB19,Reach-1         , 5
Up Type= 0
Dn Type= 3
Dn Slope=0.005
Boundary for River Rch & Prof#=SANDCREEKTRIB19,Reach-1         , 6
Up Type= 0
Dn Type= 3
Dn Slope=0.005
Boundary for River Rch & Prof#=SANDCREEKTRIB19,Reach-1         , 7
Up Type= 0
Dn Type= 3
Dn Slope=0.005
DSS Import GetInterval= 0
DSS Import GetPeak= 0
DSS Import FillOption= 0

--- SANDCREEKTRIB19.g01 (geometry) ---

Geom Title=Existing Conditions
Program Version=4.10

River Reach=SANDCREEKTRIB19 ,Reach-1
Reach XY= 30
      3562028.47     10280511.68      3562083.25     10280499.03
       3562142.3      10280561.4      3562336.62     10280683.13
      3562396.02     10280753.79      3562465.18     10280757.21
      3562572.17     10280812.16      3562675.02     10281009.92
      3562750.68     10281025.37      3562777.38     10281048.53
      3562816.59     10281128.57      3562816.17     10281189.37
       3562892.8     10281268.03      3562901.05     10281296.32
      3562890.74     10281391.05       3562855.7     10281525.28
      3562809.69     10281630.31      3562761.08     10281681.53
      3562742.85     10281768.33       3562752.4     10281780.48
      3562797.54     10281782.22      3562791.46     10281961.91
      3562897.44     10282148.86      3562916.68     10282244.47
      3562974.93     10282329.68      3563009.21     10282353.64
      3563081.83     10282446.76      3563110.36      10282560.8
      3563097.57     10282601.92      3563122.11     10282641.64

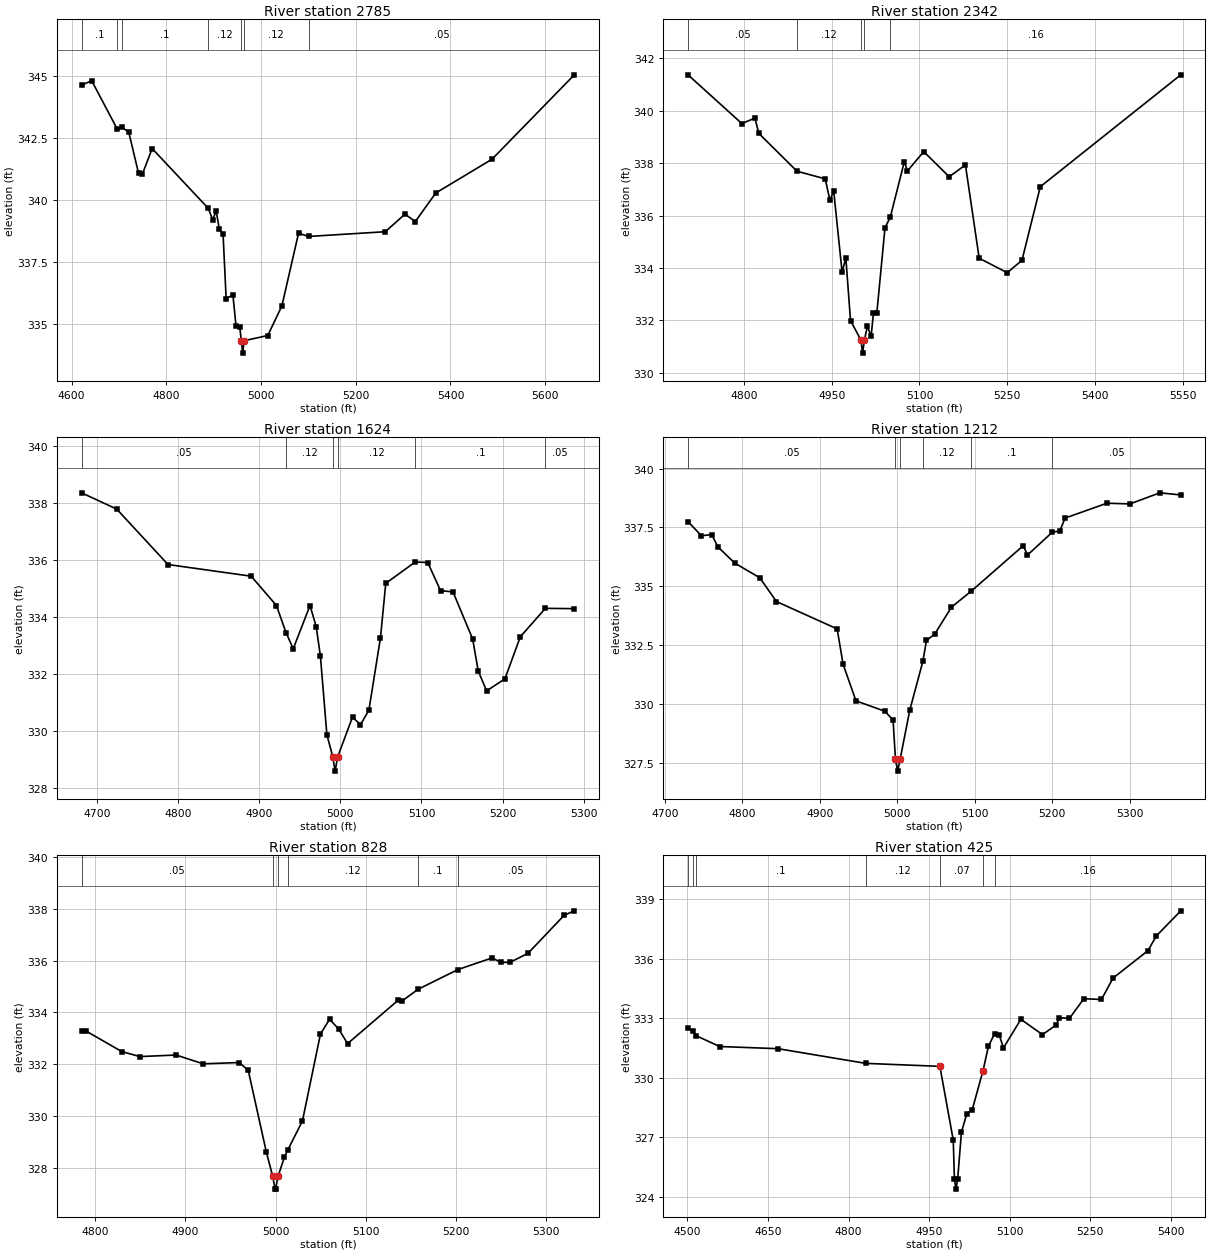
Type RM Length L Ch R = 1 ,2785    ,443,443,443
BEGIN DESCRIPTION:
UNT1437 IN WICK 6.0
END DESCRIPTION:
XS GIS Cut Line= 3
      3561792.09     10280741.66      3562092.11     10280491.64
      3562342.09     10279891.67
#Sta/Elev= 30
    4621  344.62  4642.5  344.79  4696.2  342.85  4706.2  342.91  4720.6  342.73
  4741.4  341.06  4749.2  341.02  4770.1  342.06  4888.7  339.65  4897.6   339.2
  4905.4  339.53    4912   338.8  4919.8  338.62  4926.3  336.02  4940.6  336.16
  4947.1  334.93  4954.9  334.89  4958.4  334.32  4961.2  333.82  4964.4  334.32
  5014.2  334.53    5044  335.72  5079.2  338.65  5100.3  338.52  5262.3  338.71
    5304  339.42  5325.7  339.12    5369  340.27  5487.7  341.63  5661.5  345.03
#Mann= 7 ,-1 , 0
    4621      .1       0  4696.2     .05       0  4706.2      .1       0
  4888.7     .12       0  4958.4     .07       0  4964.4     .12       0
  5100.3     .05       0
Bank Sta=4958.4,4964.4
XS Rating Curve= 0 ,0
Exp/Cntr=0.3,0.1

Type RM Length L Ch R = 1 ,2342    ,718,718,718
BEGIN DESCRIPTION:
UNT1437 IN WICK 5.0
END DESCRIPTION:
XS GIS Cut Line= 3
      3562242.13     10280991.61      3562442.11     10280741.64
       3562592.1     10280241.67
#Sta/Elev= 30
  4704.5  341.37  4796.5  339.51  4818.9  339.72  4825.3  339.14  4890.8  337.69
    4939   337.4    4947  336.58  4953.4  336.95  4967.8  333.84  4974.2  334.39
  4982.2  331.99    5000  331.25  5002.8  330.75    5006  331.25    5011  331.78
  5017.4  331.39  5021.4  332.29  5027.2  332.29  5041.1  335.53  5050.2  335.94
  5074.2  338.06  5079.4   337.7  5107.3  338.44  5150.8  337.48  5178.6  337.93
  5202.1  334.37    5250  333.82  5275.2  334.29  5306.5   337.1  5546.6  341.37
#Mann= 5 ,-1 , 0
  4704.5     .05       0  4890.8     .12       0    5000     .07       0
    5006     .12       0  5050.2     .16       0
Bank Sta=5000,5006
XS Rating Curve= 0 ,0
Exp/Cntr=0.3,0.1

Type RM Length L Ch R = 1 ,1624    ,412,412,412
BEGIN DESCRIPTION:
UNT1437 IN WICK 4.0
END DESCRIPTION:
XS GIS Cut Line= 2
      3562550.39     10281323.73      3563136.38     10281163.11
#Sta/Elev= 30
  4680.9  338.36  4724.2  337.79  4787.5  335.84  4890.1  335.43  4921.2   334.4
    4933  333.45  4941.9  332.88  4962.6   334.4  4970.2  333.66  4975.4  332.63
  4983.4  329.86  4990.7  329.08  4993.5  328.58  4996.7  329.08    5015  330.48
  5024.8  330.21  5035.2  330.72  5049.5  333.27    5056  335.18  5092.4  335.93
  5107.8  335.91  5123.6  334.92  5138.9  334.88  5163.2  333.22    5170   332.1
  5180.4   331.4  5202.9  331.82  5221.9   333.3  5252.8   334.3  5288.5  334.29
#Mann= 6 ,-1 , 0
  4680.9     .05       0    4933     .12       0  4990.7     .07       0
  4996.7     .12       0  5092.4      .1       0  5252.8     .05       0
Bank Sta=4990.7,4996.7
XS Rating Curve= 0 ,0
Exp/Cntr=0.3,0.1

Type RM Length L Ch R = 1 ,1212    ,384,384,384
BEGIN DESCRIPTION:
UNT1437 IN WICK 3.0
END DESCRIPTION:
XS GIS Cut Line= 2
      3562566.06     10281516.46      3563157.27     10281751.18
#Sta/Elev= 30
  4729.9  337.75  4747.2  337.15  4760.4   337.2  4768.7  336.67  4790.2  335.99
  4822.5  335.37  4844.1  334.36  4922.4   333.2  4930.1   331.7  4946.7  330.15
  4983.9  329.71  4994.6  329.34  4997.7  327.67  5000.5  327.17  5003.7  327.67
  5016.2  329.76  5033.1  331.83  5037.7  332.71  5048.4  332.98  5069.9  334.12
  5095.5   334.8  5162.7  336.73  5168.1  336.33  5200.1   337.3  5209.8  337.35
  5216.7   337.9  5270.7  338.53  5300.4   338.5  5338.9  338.97    5366  338.88
#Mann= 6 ,-1 , 0
  4729.9     .05       0  4997.7     .03       0  5003.7     .05       0
  5033.1     .12       0  5095.5      .1       0  5200.1     .05       0
Bank Sta=4997.7,5003.7
XS Rating Curve= 0 ,0
Exp/Cntr=0.3,0.1

Type RM Length L Ch R = 1 ,828     ,403,403,403
BEGIN DESCRIPTION:
UNT1437 IN WICK 2.0
END DESCRIPTION:
XS GIS Cut Line= 2
      3562577.38     10281933.95      3563123.32     10281907.07
#Sta/Elev= 30
  4784.7  333.28  4789.5  333.28  4829.5  332.48  4849.5  332.29  4889.6  332.35
  4919.6  332.01  4959.6  332.06  4969.6  331.76  4989.7   328.6  4996.7  327.67
  4999.4  327.17  4999.9  327.17  5002.7  327.67  5009.7   328.4  5013.7   328.7
  5029.7   329.8  5049.7  333.16  5059.8  333.73  5069.8  333.36  5079.8  332.79
  5135.7  334.46  5140.7  334.45    5158  334.89  5202.1  335.65    5240   336.1
    5250  335.93    5260  335.93    5280  336.28  5320.1  337.75  5331.3  337.92
#Mann= 6 ,-1 , 0
  4784.7     .05       0  4996.7     .03       0  5002.7     .05       0
  5013.7     .12       0    5158      .1       0  5202.1     .05       0
Bank Sta=4996.7,5002.7
XS Rating Curve= 0 ,0
Exp/Cntr=0.3,0.1

Type RM Length L Ch R = 1 ,425     ,0,0,0
BEGIN DESCRIPTION:
UNT1437 IN WICK 1.0
END DESCRIPTION:
XS GIS Cut Line= 4
      3562476.61     10282187.41      3562699.11     10282311.39
       3563180.6     10282261.23      3563268.65     10282105.85
#Sta/Elev= 30
    4501   332.5  4510.3  332.34  4515.6  332.13  4559.9  331.58  4668.5  331.47
  4831.8  330.73  4969.9  330.58  4994.8  326.86    4997  324.89  4999.8  324.39
    5003  324.89  5010.1  327.28  5020.1  328.19  5030.2   328.4  5050.3  330.37
  5060.3  331.59  5071.6  332.22  5080.5  332.15  5088.3  331.51  5120.7  332.95
  5160.9  332.18  5186.8  332.67  5191.8  333.03  5211.2     333    5238  333.99
  5270.7  333.95  5292.3  335.03  5357.2  336.41  5373.1  337.16  5418.4  338.42
#Mann= 7 ,-1 , 0
    4501      .1       0  4510.3     .05       0  4515.6      .1       0
  4831.8     .12       0  4969.9     .07       0  5050.3     .12       0
  5071.6     .16       0
Bank Sta=4969.9,5050.3
XS Rating Curve= 0 ,0
Exp/Cntr=0.3,0.1

Chan Stop Cuts=-1
Use User Specified Reach Order=0
Composite Channel Slope=5