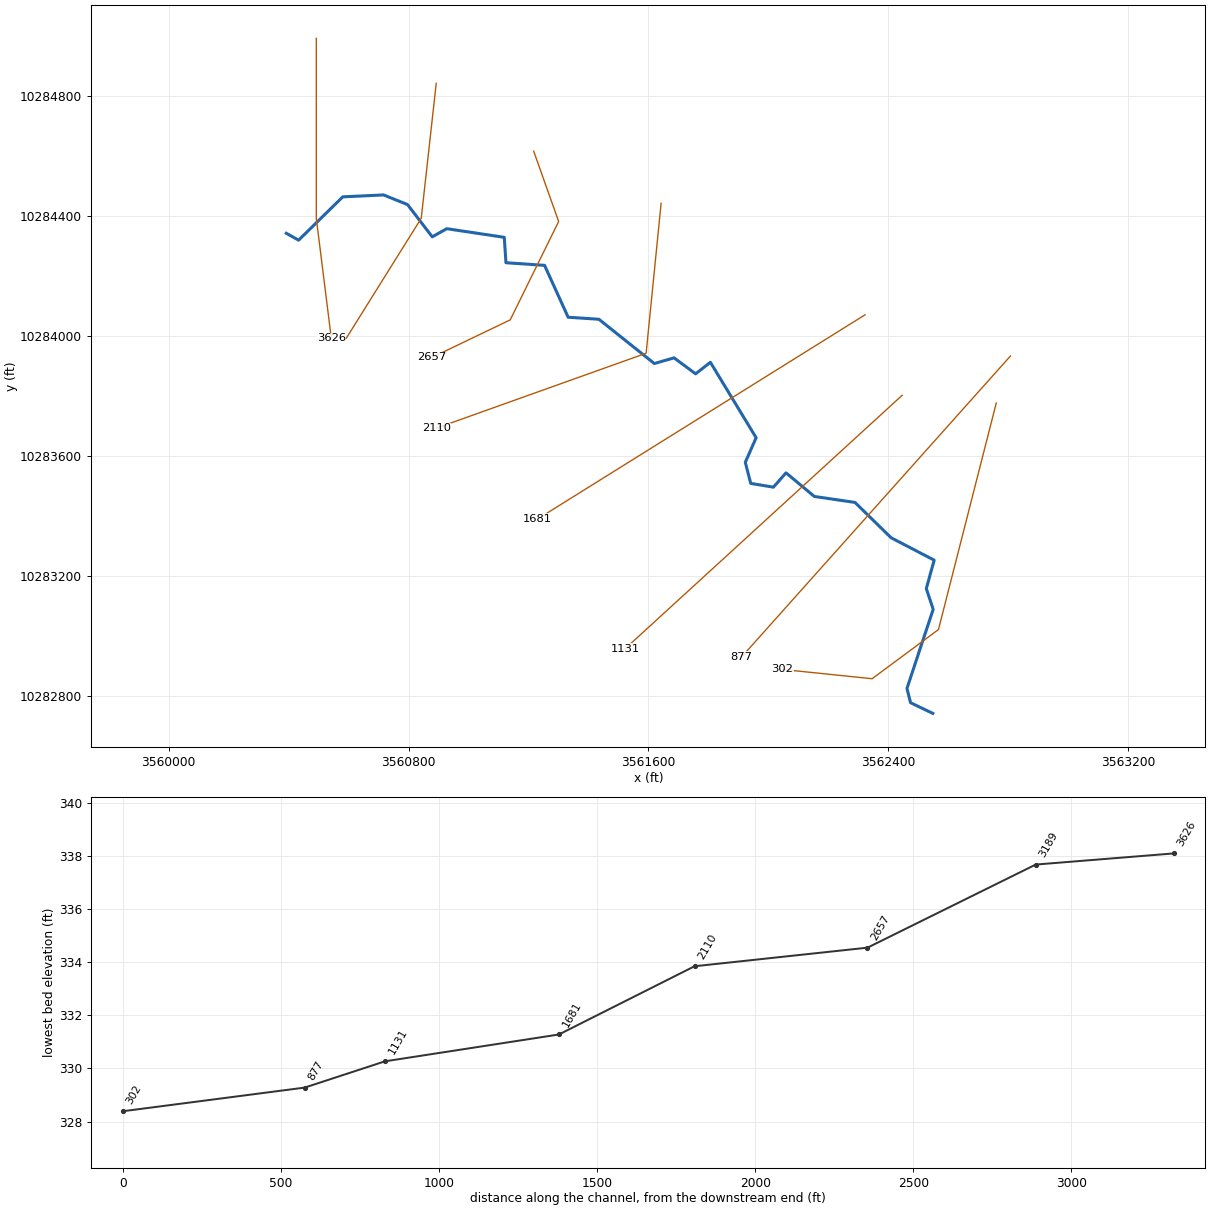
--- SANDCREEKTRIB20.prj (project) ---

Proj Title=SAND CREEK TRIB 20
Current Plan=p01
Default Exp/Contr=0.3,0.1
English Units
Geom File=g01
Flow File=f01
Plan File=p01
Y Axis Title=Elevation
X Axis Title(PF)=Main Channel Distance
X Axis Title(XS)=Station
BEGIN DESCRIPTION:
UNT1436 IN WICK
END DESCRIPTION:
DSS Export Rating Curves= 0
DSS Export Rating Curve Sorted= 0
DSS Export Volume Flow Curves= 0
DXF Filename=UNT1436 IN WICK.
DXF OffsetX= 0
DXF OffsetY= 0
DXF ScaleX= 1
DXF ScaleY= 10

--- SANDCREEKTRIB20.p01 (plan) ---

Plan Title=Multiple Run
Short Identifier=Multiple
Geom File=g01
Flow File=f01
Subcritical Flow
K Sum by GR= 0
Std Step Tol= 0.01
Critical Tol= 0.01
Num of Std Step Trials= 20
Max Error Tol= 0.3
Flow Tol Ratio= 0.001
Split Flow NTrial= 30
Split Flow Tol= 0.02
Split Flow Ratio= 0.02
Log Output Level= 0
Friction Slope Method= 1
Unsteady Friction Slope Method= 2
Unsteady Bridges Friction Slope Method= 1
Parabolic Critical Depth
Global Vel Dist=  1 , 1 , 1
Global Log Level= 0
CheckData=True
Encroach Param= -1, 0, 0, 0
BEGIN DESCRIPTION:
Multiple Run
END DESCRIPTION:

--- SANDCREEKTRIB20.f01 (steady flow) ---

Flow Title=Multiple
Program Version=4.10
Number of Profiles= 7
Profile Names=10-year,25-year,50-year,1pct_min,100-year,1pct_plu,500-year
River Rch & RM=UNT1436 IN WICK,Reach-1         ,3626
     291     375     441     380     514     695     699
River Rch & RM=SANDCREEKTRIB20,Reach-1         ,3626
     291     375     441     380     514     695     699
Boundary for River Rch & Prof#=SANDCREEKTRIB20,Reach-1         , 1
Up Type= 0
Dn Type= 3
Dn Slope=0.005
Boundary for River Rch & Prof#=SANDCREEKTRIB20,Reach-1         , 2
Up Type= 0
Dn Type= 3
Dn Slope=0.005
Boundary for River Rch & Prof#=SANDCREEKTRIB20,Reach-1         , 3
Up Type= 0
Dn Type= 3
Dn Slope=0.005
Boundary for River Rch & Prof#=SANDCREEKTRIB20,Reach-1         , 4
Up Type= 0
Dn Type= 3
Dn Slope=0.005
Boundary for River Rch & Prof#=SANDCREEKTRIB20,Reach-1         , 5
Up Type= 0
Dn Type= 3
Dn Slope=0.005
Boundary for River Rch & Prof#=SANDCREEKTRIB20,Reach-1         , 6
Up Type= 0
Dn Type= 3
Dn Slope=0.005
Boundary for River Rch & Prof#=SANDCREEKTRIB20,Reach-1         , 7
Up Type= 0
Dn Type= 3
Dn Slope=0.005
DSS Import GetInterval= 0
DSS Import GetPeak= 0
DSS Import FillOption= 0

--- SANDCREEKTRIB20.g01 (geometry) ---

Geom Title=Existing Conditions
Program Version=4.10

River Reach=SANDCREEKTRIB20 ,Reach-1
Reach XY= 30
      3560392.07     10284341.57      3560433.19     10284318.76
      3560580.49     10284463.17      3560716.35     10284469.51
      3560796.29      10284437.4      3560878.81     10284329.77
      3560927.27     10284356.87      3561119.02     10284328.16
      3561124.64      10284243.5      3561253.41     10284234.67
      3561332.02     10284061.67      3561434.51     10284054.99
      3561619.58     10283907.26      3561685.33     10283926.21
       3561757.1     10283872.95      3561806.44     10283911.48
      3561958.97     10283659.91      3561922.85     10283577.87
      3561940.95     10283507.66      3562016.74     10283495.07
      3562058.67     10283542.96      3562153.06     10283464.04
       3562288.5     10283444.26      3562409.27     10283326.34
       3562552.8     10283251.74      3562526.54     10283156.86
      3562549.52     10283087.75      3562461.97     10282823.78
      3562473.95     10282776.38      3562548.12     10282740.79

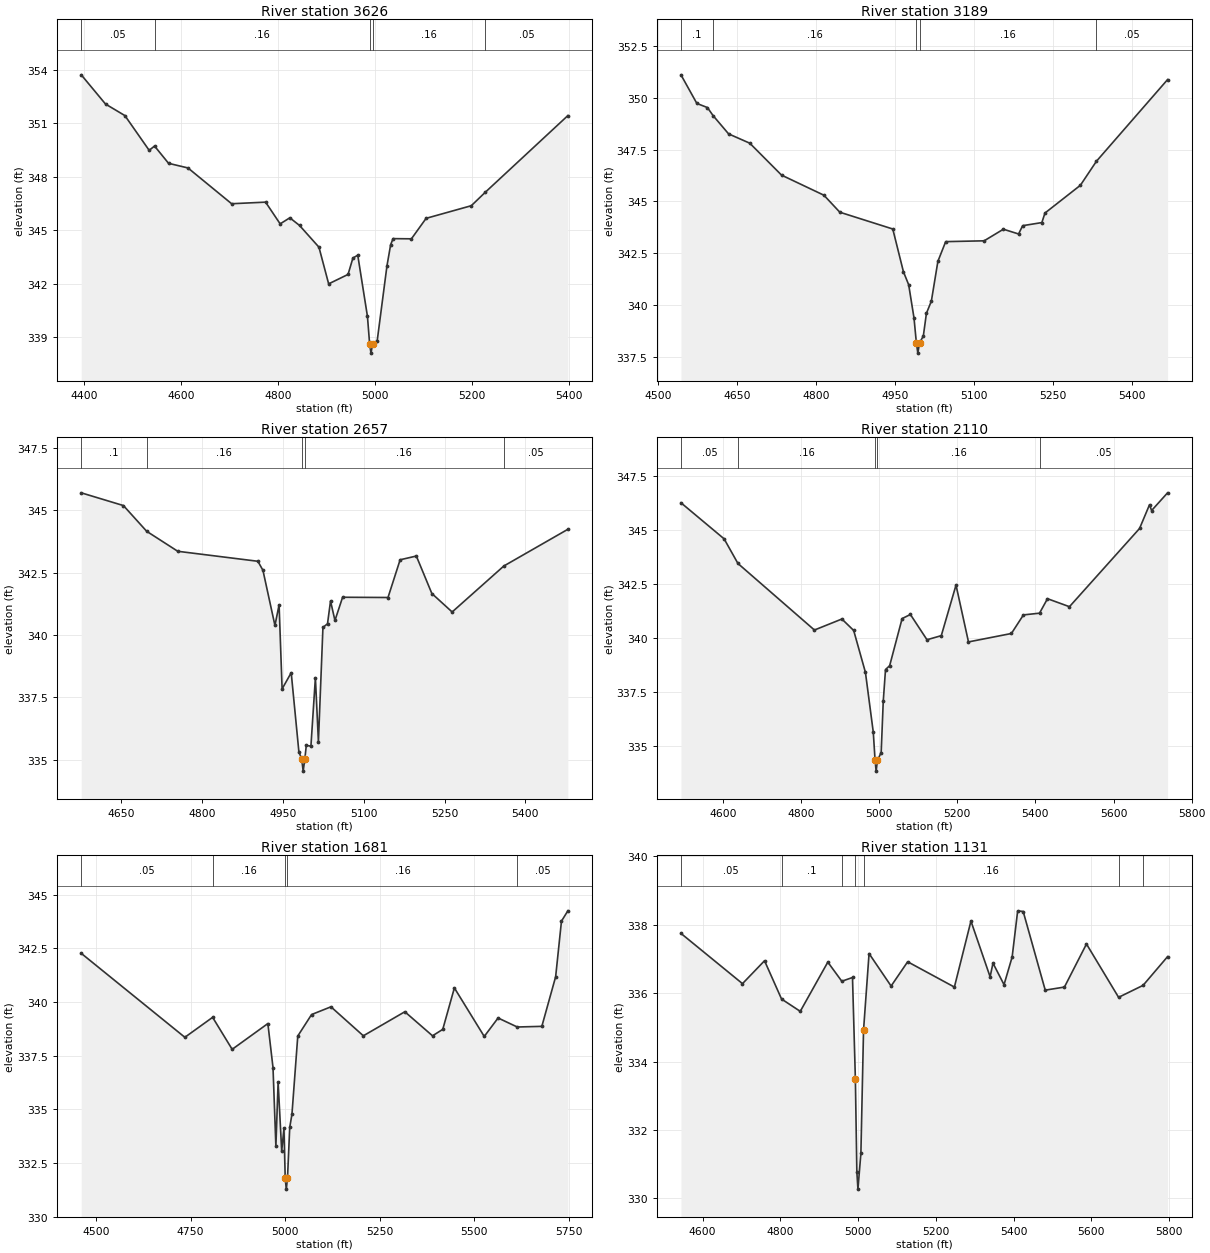
Type RM Length L Ch R = 1 ,3626    ,437,437,437
BEGIN DESCRIPTION:
UNT1436 IN WICK 7.0
END DESCRIPTION:
XS GIS Cut Line= 3
      3560492.11     10284991.66      3560492.11     10284391.64
       3560542.1     10283991.67
#Sta/Elev= 30
  4394.9  353.73  4444.9  352.09  4484.9  351.44  4534.9  349.49    4546  349.73
  4574.9  348.76  4614.9   348.5  4704.9  346.49  4774.9  346.58  4804.9  345.36
  4824.9   345.7  4844.9  345.27  4884.9  344.05  4904.9  341.99  4944.9  342.52
  4954.9  343.44  4964.9   343.6  4984.9  340.16  4989.4   338.6  4992.2   338.1
  4995.4   338.6    5005   338.8  5025.1     343  5032.7  344.19  5037.7  344.53
  5075.5  344.52  5105.8  345.67    5199  346.38    5228  347.14    5398  351.44
#Mann= 5 ,-1 , 0
  4394.9     .05       0    4546     .16       0  4989.4     .07       0
  4995.4     .16       0    5228     .05       0
Bank Sta=4989.4,4995.4
XS Rating Curve= 0 ,0
Exp/Cntr=0.3,0.1

Type RM Length L Ch R = 1 ,3189    ,532,532,532
BEGIN DESCRIPTION:
UNT1436 IN WICK 6.0
END DESCRIPTION:
XS GIS Cut Line= 3
       3560892.1     10284841.62      3560842.11     10284391.64
      3560592.13     10283991.68
#Sta/Elev= 30
    4544  351.11  4574.2  349.73  4594.3  349.53  4605.1  349.14  4634.5  348.26
  4674.8  347.81  4735.1  346.27  4815.6   345.3  4845.8  344.48  4946.4  343.67
  4966.6  341.61  4976.6  340.98  4986.7  339.38  4991.2  338.18    4994  337.68
  4997.2  338.18  5004.4   338.5  5010.3   339.6  5019.7  340.19  5032.1  342.11
  5046.9  343.06    5120   343.1  5156.5  343.66  5185.4  343.43  5193.1  343.83
  5229.6  343.98  5235.5  344.44  5302.8  345.78  5333.3  346.94  5468.4  350.88
#Mann= 5 ,-1 , 0
    4544      .1       0  4605.1     .16       0  4991.2     .07       0
  4997.2     .16       0  5333.3     .05       0
Bank Sta=4991.2,4997.2
XS Rating Curve= 0 ,0
Exp/Cntr=0.3,0.1

Type RM Length L Ch R = 1 ,2657    ,547,547,547
BEGIN DESCRIPTION:
UNT1436 IN WICK 5.0
END DESCRIPTION:
XS GIS Cut Line= 4
      3561217.04     10284615.44      3561300.39     10284381.02
      3561138.93      10284052.9      3560878.47     10283927.88
#Sta/Elev= 30
  4575.6  345.69  4653.9  345.18  4697.1  344.15  4754.8  343.35  4903.5  342.95
  4912.9  342.59  4935.2  340.38  4942.9  341.21  4948.5  337.84  4965.4  338.49
  4979.7  335.31  4984.8  335.05  4987.6  334.55  4990.8  335.05  4993.4  335.58
    5002  335.55  5010.3  338.29  5015.9  335.73  5024.3   340.3  5032.8  340.45
  5038.4  341.36  5046.6  340.58  5060.8  341.51  5145.1   341.5  5167.6  343.01
  5197.7  343.16  5226.5  341.66  5264.2  340.92  5360.1  342.76    5479  344.23
#Mann= 5 ,-1 , 0
  4575.6      .1       0  4697.1     .16       0  4984.8     .07       0
  4990.8     .16       0  5360.1     .05       0
Bank Sta=4984.8,4990.8
XS Rating Curve= 0 ,0
Exp/Cntr=0.3,0.1

Type RM Length L Ch R = 1 ,2110    ,429,429,429
BEGIN DESCRIPTION:
UNT1436 IN WICK 4.0
END DESCRIPTION:
XS GIS Cut Line= 3
       3561642.1     10284441.61      3561592.11     10283941.64
      3560892.07     10283691.63
#Sta/Elev= 30
  4492.5  346.27    4603   344.6  4638.4  343.46  4834.2  340.38  4904.5  340.89
  4934.7  340.36  4964.8  338.42  4984.9  335.65  4989.5  334.35  4992.2  333.85
  4995.5  334.35  5005.1  334.71  5010.4  337.08  5016.2  338.55  5026.8  338.73
  5058.7  340.91  5079.9   341.1  5122.4  339.93    5159  340.12  5196.7  342.46
  5228.6  339.83  5338.5  340.22  5369.3  341.08  5410.5  341.16  5430.9  341.83
  5487.1  341.46  5666.6  345.08  5692.1  346.18  5697.4  345.91  5738.3  346.73
#Mann= 5 ,-1 , 0
  4492.5     .05       0  4638.4     .16       0  4989.5     .07       0
  4995.5     .16       0  5410.5     .05       0
Bank Sta=4989.5,4995.5
XS Rating Curve= 0 ,0
Exp/Cntr=0.3,0.1

Type RM Length L Ch R = 1 ,1681    ,550,550,550
BEGIN DESCRIPTION:
UNT1436 IN WICK 3.0
END DESCRIPTION:
XS GIS Cut Line= 2
      3562322.41     10284069.89      3561230.44     10283389.12
#Sta/Elev= 30
  4460.8  342.26  4734.8  338.35  4808.2  339.28  4859.9  337.79  4954.3  338.99
  4967.9  336.94  4975.5  333.27  4981.4  336.27  4990.9  333.05  4996.8  334.11
  5000.2  331.78    5003  331.28  5006.2  331.78  5012.1  334.15    5018  334.77
  5033.4  338.41  5069.9  339.41  5121.1  339.77  5206.8  338.42  5316.5  339.54
  5389.7  338.42  5416.8  338.72  5447.5  340.65  5526.5  338.39  5563.1  339.25
  5613.8  338.83  5678.8  338.86  5715.3  341.17  5730.7  343.76  5747.6  344.24
#Mann= 5 ,-1 , 0
  4460.8     .05       0  4808.2     .16       0  5000.2     .07       0
  5006.2     .16       0  5613.8     .05       0
Bank Sta=5000.2,5006.2
XS Rating Curve= 0 ,0
Exp/Cntr=0.3,0.1

Type RM Length L Ch R = 1 ,1131    ,254,254,254
BEGIN DESCRIPTION:
UNT1436 IN WICK 2.0
END DESCRIPTION:
XS GIS Cut Line= 2
      3562446.07     10283801.46      3561522.35     10282956.63
#Sta/Elev= 30
  4544.3  337.75  4702.6  336.28  4759.3  336.95  4803.1  335.83  4851.2  335.47
  4922.1  336.91  4958.1  336.35  4985.6  336.46    4993  333.49  4996.8  330.77
  4999.6  330.27  5007.2  331.32    5014  334.92  5028.2  337.16  5084.9  336.21
  5127.5  336.92  5247.7  336.18  5290.3  338.11  5339.6  336.48    5347  336.88
  5375.4  336.25  5396.3  337.06  5410.5  338.41  5424.7  338.39  5481.4  336.09
  5530.8  336.18  5587.5  337.44  5670.1  335.88  5733.1  336.23  5796.1  337.07
#Mann= 7 ,-1 , 0
  4544.3     .05       0  4803.1      .1       0  4958.1     .16       0
    4993     .07       0    5014     .16       0  5670.1     .05       0
  5733.1      .1       0
Bank Sta=4993,5014
XS Rating Curve= 0 ,0
Exp/Cntr=0.3,0.1

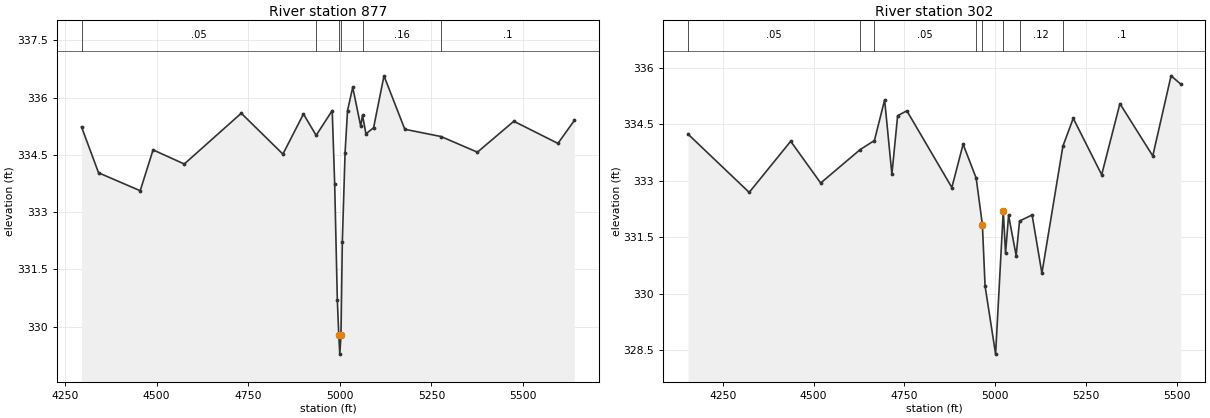
Type RM Length L Ch R = 1 ,877     ,575,575,575
BEGIN DESCRIPTION:
Mapping XS bdd85a51
END DESCRIPTION:
XS GIS Cut Line= 2
      3562807.04      10283932.3      3561910.95     10282929.28
#Sta/Elev= 30
  4295.1  335.23  4341.5  334.03  4455.2  333.56  4490.3  334.63  4575.5  334.26
    4731  335.59  4844.7  334.52  4900.8  335.57  4935.4  335.01  4979.3  335.66
    4986  333.74  4993.3  330.69  4997.2  329.78    5000  329.28  5003.2  329.78
  5006.9  332.23  5014.4  334.56  5021.1  335.66  5035.3  336.27  5057.1  335.25
    5062  335.54  5071.3  335.05  5092.2  335.21  5120.6  336.57  5177.4  335.17
  5276.2  334.98  5375.6  334.57    5475  335.38  5595.4   334.8  5640.1   335.4
#Mann= 6 ,-1 , 0
  4295.1     .05       0  4935.4      .1       0  4997.2     .07       0
  5003.2      .1       0    5062     .16       0  5276.2      .1       0
Bank Sta=4997.2,5003.2
XS Rating Curve= 0 ,0
Exp/Cntr=0.3,0.1

Type RM Length L Ch R = 1 ,302     ,0,0,0
BEGIN DESCRIPTION:
UNT1436 IN WICK 1.0
END DESCRIPTION:
XS GIS Cut Line= 4
      3562759.88     10283775.58      3562567.18      10283020.4
      3562345.83     10282856.34      3562045.43     10282887.41
#Sta/Elev= 30
  4154.1  334.24  4322.6  332.69  4436.8  334.05  4519.4  332.94  4628.3  333.83
  4667.4  334.07  4695.5  335.15  4715.5  333.17  4731.3  334.73  4756.7  334.86
  4880.6  332.82  4911.6  333.97  4947.6  333.07  4964.7  331.83  4972.1   330.2
  5001.1  328.39  5022.2   332.2  5028.5  331.07  5036.8  332.08  5057.7  331.01
    5067  331.93  5101.6  332.09  5128.6  330.54  5186.4  333.92  5214.9  334.66
  5293.2  333.16  5343.4  335.05  5433.9  333.66  5484.2  335.79    5511  335.57
#Mann= 8 ,-1 , 0
  4154.1     .05       0  4628.3     .16       0  4667.4     .05       0
  4947.6     .12       0  4964.7     .07       0  5022.2     .12       0
    5067     .12       0  5186.4      .1       0
Bank Sta=4964.7,5022.2
XS Rating Curve= 0 ,0
Exp/Cntr=0.3,0.1

Chan Stop Cuts=-1
Use User Specified Reach Order=0
Composite Channel Slope=5