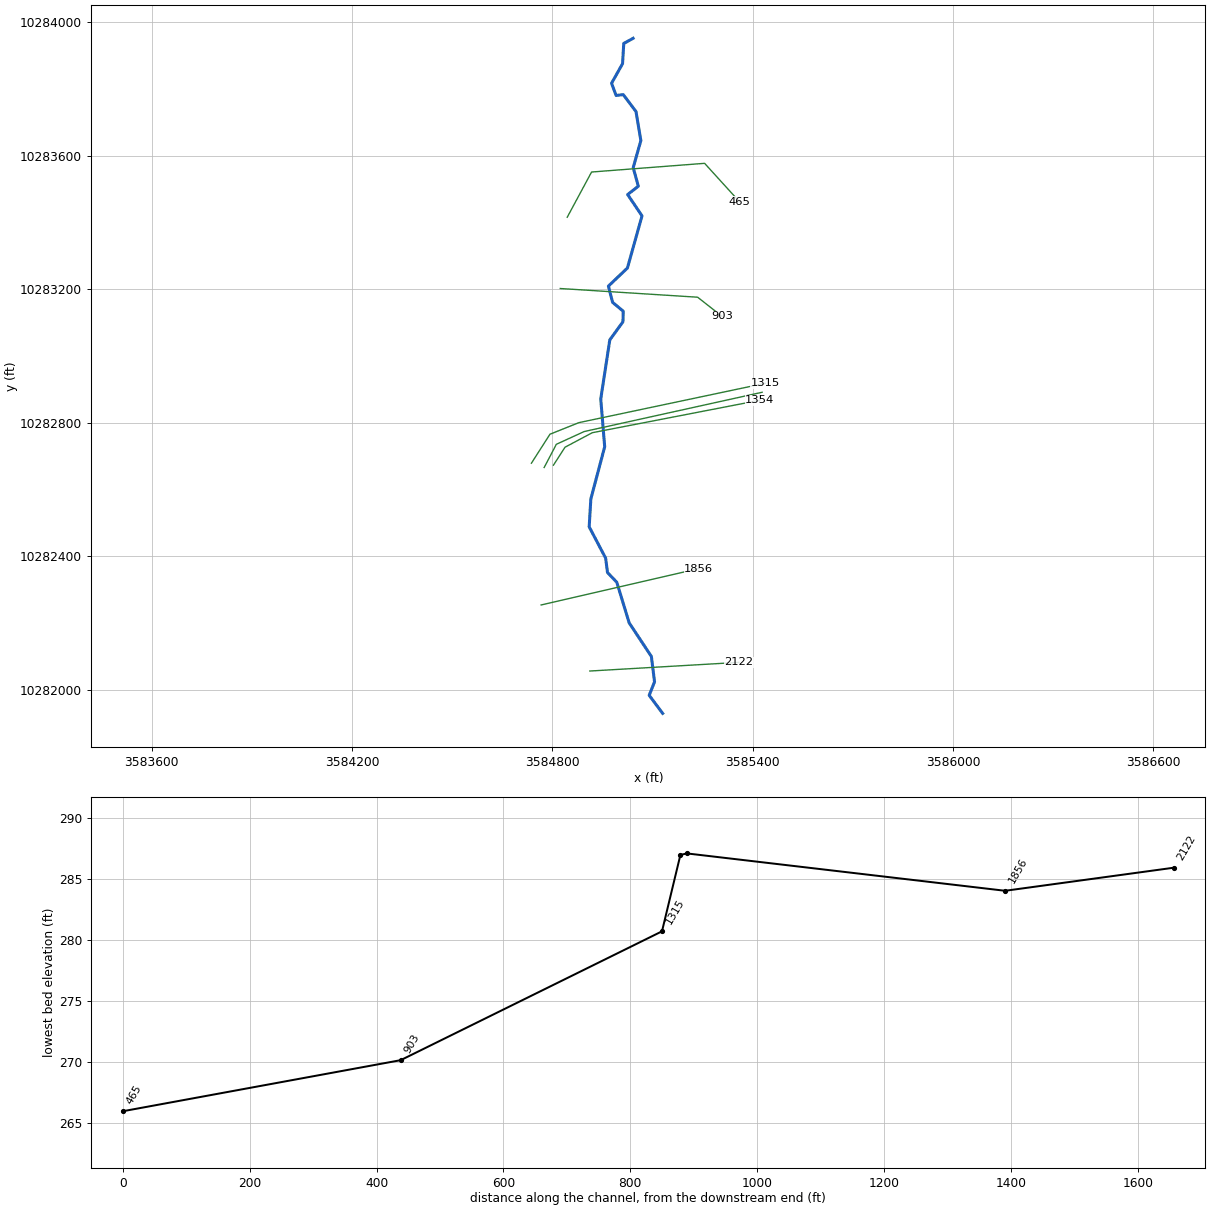
--- SANDCREEKTRIB5.prj (project) ---

Proj Title=SAND CREEK TRIB 5
Current Plan=p01
Default Exp/Contr=0.3,0.1
English Units
Geom File=g01
Flow File=f01
Plan File=p01
Y Axis Title=Elevation
X Axis Title(PF)=Main Channel Distance
X Axis Title(XS)=Station
BEGIN DESCRIPTION:
UNT105 IN WICK
END DESCRIPTION:
DSS Export Rating Curves= 0
DSS Export Rating Curve Sorted= 0
DSS Export Volume Flow Curves= 0
DXF OffsetX= 0
DXF OffsetY= 0
DXF ScaleX= 1
DXF ScaleY= 10

--- SANDCREEKTRIB5.p01 (plan) ---

Plan Title=Multiple Run
Short Identifier=Multiple
Geom File=g01
Flow File=f01
Subcritical Flow
K Sum by GR= 0
Std Step Tol= 0.01
Critical Tol= 0.01
Num of Std Step Trials= 20
Max Error Tol= 0.3
Flow Tol Ratio= 0.001
Split Flow NTrial= 30
Split Flow Tol= 0.02
Split Flow Ratio= 0.02
Log Output Level= 0
Friction Slope Method= 1
Unsteady Friction Slope Method= 2
Unsteady Bridges Friction Slope Method= 1
Parabolic Critical Depth
Global Vel Dist=  1 , 1 , 1
Global Log Level= 0
CheckData=True
Encroach Param= -1, 0, 0, 0
BEGIN DESCRIPTION:
Multiple Run
END DESCRIPTION:

--- SANDCREEKTRIB5.f01 (steady flow) ---

Flow Title=Multiple
Program Version=4.10
Number of Profiles= 7
Profile Names=10-year,25-year,50-year,1pct_min,100-year,1pct_plu,500-year
River Rch & RM=UNT105 IN WICK,Reach-1         ,2122
     124     151     171     143     194     262     248
River Rch & RM=SANDCREEKTRIB5,Reach-1         ,2122
     124     151     171     143     194     262     248
Boundary for River Rch & Prof#=SANDCREEKTRIB5,Reach-1         , 1
Up Type= 0
Dn Type= 3
Dn Slope=0.005
Boundary for River Rch & Prof#=SANDCREEKTRIB5,Reach-1         , 2
Up Type= 0
Dn Type= 3
Dn Slope=0.005
Boundary for River Rch & Prof#=SANDCREEKTRIB5,Reach-1         , 3
Up Type= 0
Dn Type= 3
Dn Slope=0.005
Boundary for River Rch & Prof#=SANDCREEKTRIB5,Reach-1         , 4
Up Type= 0
Dn Type= 3
Dn Slope=0.005
Boundary for River Rch & Prof#=SANDCREEKTRIB5,Reach-1         , 5
Up Type= 0
Dn Type= 3
Dn Slope=0.005
Boundary for River Rch & Prof#=SANDCREEKTRIB5,Reach-1         , 6
Up Type= 0
Dn Type= 3
Dn Slope=0.005
Boundary for River Rch & Prof#=SANDCREEKTRIB5,Reach-1         , 7
Up Type= 0
Dn Type= 3
Dn Slope=0.005
DSS Import GetInterval= 0
DSS Import GetPeak= 0
DSS Import FillOption= 0

--- SANDCREEKTRIB5.g01 (geometry) ---

Geom Title=Existing Conditions
Program Version=4.10

River Reach=SANDCREEKTRIB5  ,Reach-1
Reach XY= 30
      3585130.61     10281929.54      3585090.33     10281983.71
       3585106.3     10282023.99      3585096.83     10282100.22
      3585030.45     10282200.34      3584993.17     10282322.37
      3584965.39     10282351.54      3584959.83      10282394.6
      3584910.53     10282488.35      3584915.53     10282571.99
      3584956.99     10282728.16      3584945.19     10282871.21
      3584972.27     10283048.29      3585011.71     10283102.62
      3585012.52     10283134.23      3584980.61     10283160.79
      3584968.11     10283209.41      3585025.05     10283263.57
       3585068.8     10283419.82      3585025.74     10283483.71
      3585057.69     10283508.71      3585042.41     10283564.27
      3585065.33     10283645.52      3585050.74     10283732.32
      3585012.55     10283783.02      3584991.23     10283780.49
      3584977.54     10283816.97       3585010.5     10283875.68
      3585014.11     10283936.33      3585042.11     10283951.64

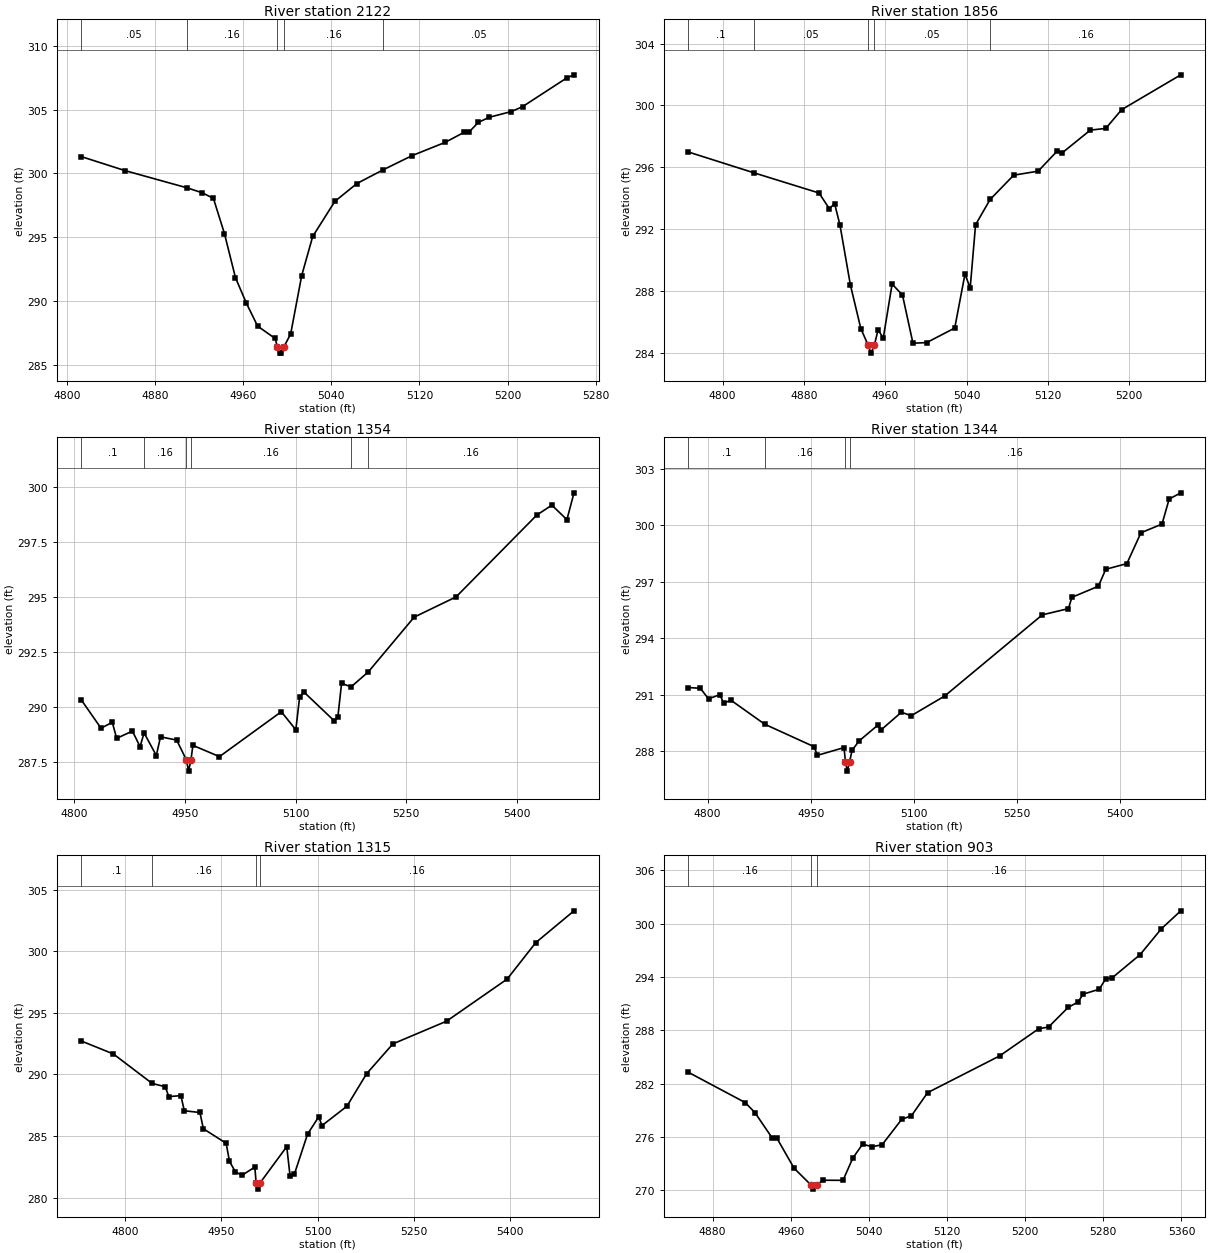
Type RM Length L Ch R = 1 ,2122    ,266,266,266
BEGIN DESCRIPTION:
UNT105 IN WICK 4.0
END DESCRIPTION:
XS GIS Cut Line= 2
      3584912.52     10282056.38      3585358.77     10282082.33
#Sta/Elev= 30
  4813.3  301.32    4853  300.22  4909.2  298.87  4923.1  298.48  4933.1  298.04
  4943.1  295.28  4953.1  291.82  4963.1   289.8  4973.2  288.02  4989.1  287.05
  4991.1   286.4  4993.9   285.9  4994.4   285.9  4997.1   286.4  5003.2  287.41
  5013.2  291.99  5023.2  295.06  5043.3  297.81  5063.3  299.21  5087.2  300.29
  5113.4   301.4  5143.4  302.44  5160.4  303.22  5165.4  303.28  5173.5  304.01
  5183.5  304.41  5203.5  304.86  5213.6  305.24  5253.6  307.49  5260.3  307.74
#Mann= 5 ,-1 , 0
  4813.3     .05       0  4909.2     .16       0  4991.1     .07       0
  4997.1     .16       0  5087.2     .05       0
Bank Sta=4991.1,4997.1
XS Rating Curve= 0 ,0
Exp/Cntr=0.3,0.1

Type RM Length L Ch R = 1 ,1856    ,502,502,502
BEGIN DESCRIPTION:
UNT105 IN WICK 3.0
END DESCRIPTION:
XS GIS Cut Line= 2
      3584766.66      10282254.3      3585238.85     10282363.26
#Sta/Elev= 30
  4766.1     297  4830.9  295.65  4894.8  294.35    4905  293.33  4910.1  293.67
  4915.4  292.28  4925.6  288.43  4935.9   285.6  4943.2  284.51  4945.9  284.01
  4949.2  284.51  4952.9  285.52    4958  284.98  4966.7  288.47  4976.9  287.76
  4987.2  284.65  5000.7  284.69  5028.3  285.63  5038.4  289.12  5043.5  288.21
  5048.8   292.3  5063.1  293.93  5086.3   295.5  5110.4  295.76    5129  297.05
  5134.2  296.95  5161.7  298.41  5176.9  298.52  5192.5  299.73  5250.7  301.98
#Mann= 5 ,-1 , 0
  4766.1      .1       0  4830.9     .05       0  4943.2     .03       0
  4949.2     .05       0  5063.1     .16       0
Bank Sta=4943.2,4949.2
XS Rating Curve= 0 ,0
Exp/Cntr=0.3,0.1

Type RM Length L Ch R = 1 ,1354    ,10,10,10
BEGIN DESCRIPTION:
Mapping XS e82d6bbf
END DESCRIPTION:
XS GIS Cut Line= 4
      3584803.47     10282673.03       3584838.2     10282726.87
       3584919.8     10282770.27      3585421.57      10282867.5
#Sta/Elev= 30
  4809.7   290.3  4836.3  289.02  4851.5  289.29  4857.5  288.56  4878.8  288.89
  4889.2  288.18  4894.6  288.81  4911.2  287.78  4916.9  288.63  4938.8  288.48
  4952.1  287.57  4954.9  287.07  4958.1  287.57  4960.8  288.24  4996.8  287.73
  5080.6  289.77  5100.3  288.95  5105.4  290.43  5111.1  290.67  5151.9  289.37
  5157.2  289.52  5162.3  291.06  5175.2   290.9  5198.5  291.58  5260.7  294.07
  5317.5  294.99  5426.9  298.71  5447.3  299.16  5467.7   298.5  5477.3  299.72
#Mann= 6 ,-1 , 0
  4809.7      .1       0  4894.6     .16       0  4952.1     .07       0
  4958.1     .16       0  5175.2     .05       0  5198.5     .16       0
Bank Sta=4952.1,4958.1
XS Rating Curve= 0 ,0
Exp/Cntr=0.3,0.1

Type RM Length L Ch R = 1 ,1344    ,29,29,29
BEGIN DESCRIPTION:
Mapping XS cec32a0b
END DESCRIPTION:
XS GIS Cut Line= 4
      3584775.69     10282666.08      3584812.16     10282735.55
      3584895.49     10282773.74      3585428.63     10282891.45
#Sta/Elev= 30
  4771.8  291.38  4789.4  291.34  4801.3  290.78  4817.7     291  4823.4  290.56
  4834.1   290.7  4883.1  289.43  4954.6  288.24  4959.7  287.78  4998.3  288.19
  5000.4  287.44  5003.1  286.94  5006.4  287.44  5010.1  288.05  5020.4  288.55
  5047.1  289.37  5052.2  289.13  5081.8  290.07  5095.9  289.88  5144.7  290.93
  5286.6  295.24  5324.5  295.57  5329.6  296.17  5368.1  296.76  5378.8  297.66
  5409.5  297.96    5430   299.6  5460.6  300.06    5471  301.39  5487.9  301.72
#Mann= 4 ,-1 , 0
  4771.8      .1       0  4883.1     .16       0  5000.4     .07       0
  5006.4     .16       0
Bank Sta=5000.4,5006.4
XS Rating Curve= 0 ,0
Exp/Cntr=0.3,0.1

Type RM Length L Ch R = 1 ,1315    ,412,412,412
BEGIN DESCRIPTION:
Mapping XS 86cb229f
END DESCRIPTION:
XS GIS Cut Line= 4
      3584737.53     10282678.98      3584793.06     10282765.76
      3584879.87     10282800.48      3585438.04     10282918.35
#Sta/Elev= 30
    4732  292.71  4781.8  291.66  4842.1  289.27  4862.6     289    4868   288.2
  4886.9  288.28  4892.2  287.05  4916.5  286.91  4921.9  285.59  4957.4  284.41
  4962.5  282.95  4971.7   282.1  4981.9  281.81    5002  282.48  5004.1  281.19
  5006.9  280.69  5010.1  281.19  5051.7  284.14  5056.9  281.75  5063.7  281.92
  5084.1  285.15  5101.5  286.56  5106.6  285.85  5145.4  287.42  5176.1  290.06
    5217  292.48  5300.5  294.32  5394.9  297.74  5439.5   300.7    5499  303.28
#Mann= 4 ,-1 , 0
    4732      .1       0  4842.1     .16       0  5004.1     .07       0
  5010.1     .16       0
Bank Sta=5004.1,5010.1
XS Rating Curve= 0 ,0
Exp/Cntr=0.3,0.1

Type RM Length L Ch R = 1 ,903     ,438,438,438
BEGIN DESCRIPTION:
UNT105 IN WICK 2.0
END DESCRIPTION:
XS GIS Cut Line= 3
      3584823.94     10283202.22      3585235.42     10283176.17
      3585307.76     10283119.34
#Sta/Elev= 30
    4855  283.29  4913.3  279.88  4923.3  278.75  4940.8  275.92  4945.8  275.87
  4963.4  272.49  4980.4  270.64  4983.2  270.14  4986.4  270.64  4993.4  271.14
  5013.5  271.13  5023.5  273.63  5033.5  275.19  5043.5  274.91  5053.6  275.14
  5073.6  277.99  5083.6   278.4  5100.1  280.99  5173.8  285.12  5213.9  288.18
  5223.9  288.37  5243.9  290.57    5254  291.18  5259.4  292.07  5275.8  292.62
  5282.4  293.79  5288.8  293.88  5317.7  296.52  5339.4  299.42  5359.3  301.44
#Mann= 3 ,-1 , 0
    4855     .16       0  4980.4     .07       0  4986.4     .16       0
Bank Sta=4980.4,4986.4
XS Rating Curve= 0 ,0
Exp/Cntr=0.3,0.1

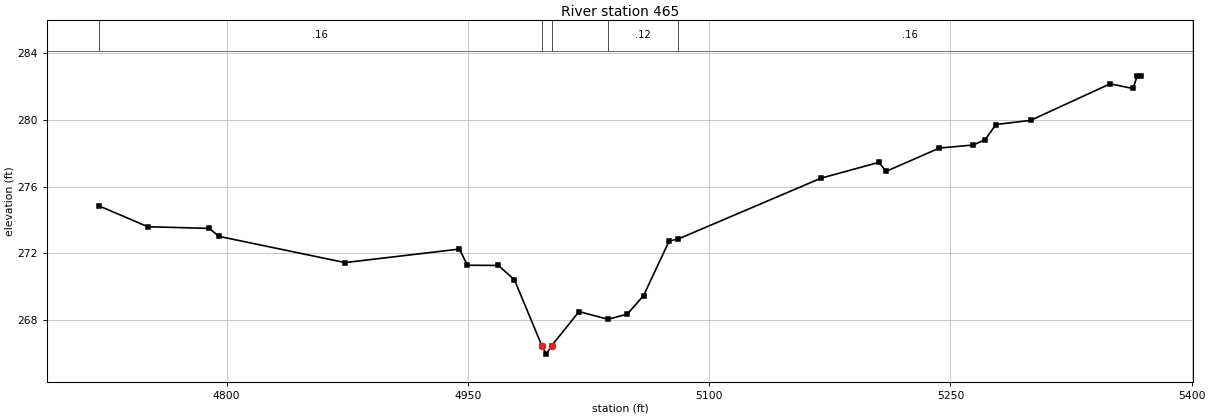
Type RM Length L Ch R = 1 ,465     ,0,0,0
BEGIN DESCRIPTION:
UNT105 IN WICK 1.0
END DESCRIPTION:
XS GIS Cut Line= 4
      3584844.78     10283415.72      3584917.71     10283551.17
      3585256.26     10283577.22       3585360.4     10283462.66
#Sta/Elev= 30
  4720.4  274.86    4751   273.6  4789.1   273.5  4795.3  273.02  4873.6  271.45
  4944.7  272.26  4949.7  271.29  4968.9  271.28  4978.9  270.42    4996  266.46
  4998.8  265.96    5002  266.46  5019.1  268.51  5037.1  268.05  5049.1  268.36
  5059.2  269.47  5075.1  272.74  5080.9  272.87  5169.5  276.51  5205.5  277.46
    5210  276.92  5243.2  278.32  5264.1   278.5  5271.6  278.82  5278.3  279.73
  5299.9  279.98  5349.3  282.17  5363.5  281.89  5366.2  282.65  5368.6  282.65
#Mann= 5 ,-1 , 0
  4720.4     .16       0    4996     .07       0    5002     .16       0
  5037.1     .12       0  5080.9     .16       0
Bank Sta=4996,5002
XS Rating Curve= 0 ,0
Exp/Cntr=0.3,0.1

Chan Stop Cuts=-1
Use User Specified Reach Order=0
Composite Channel Slope=5