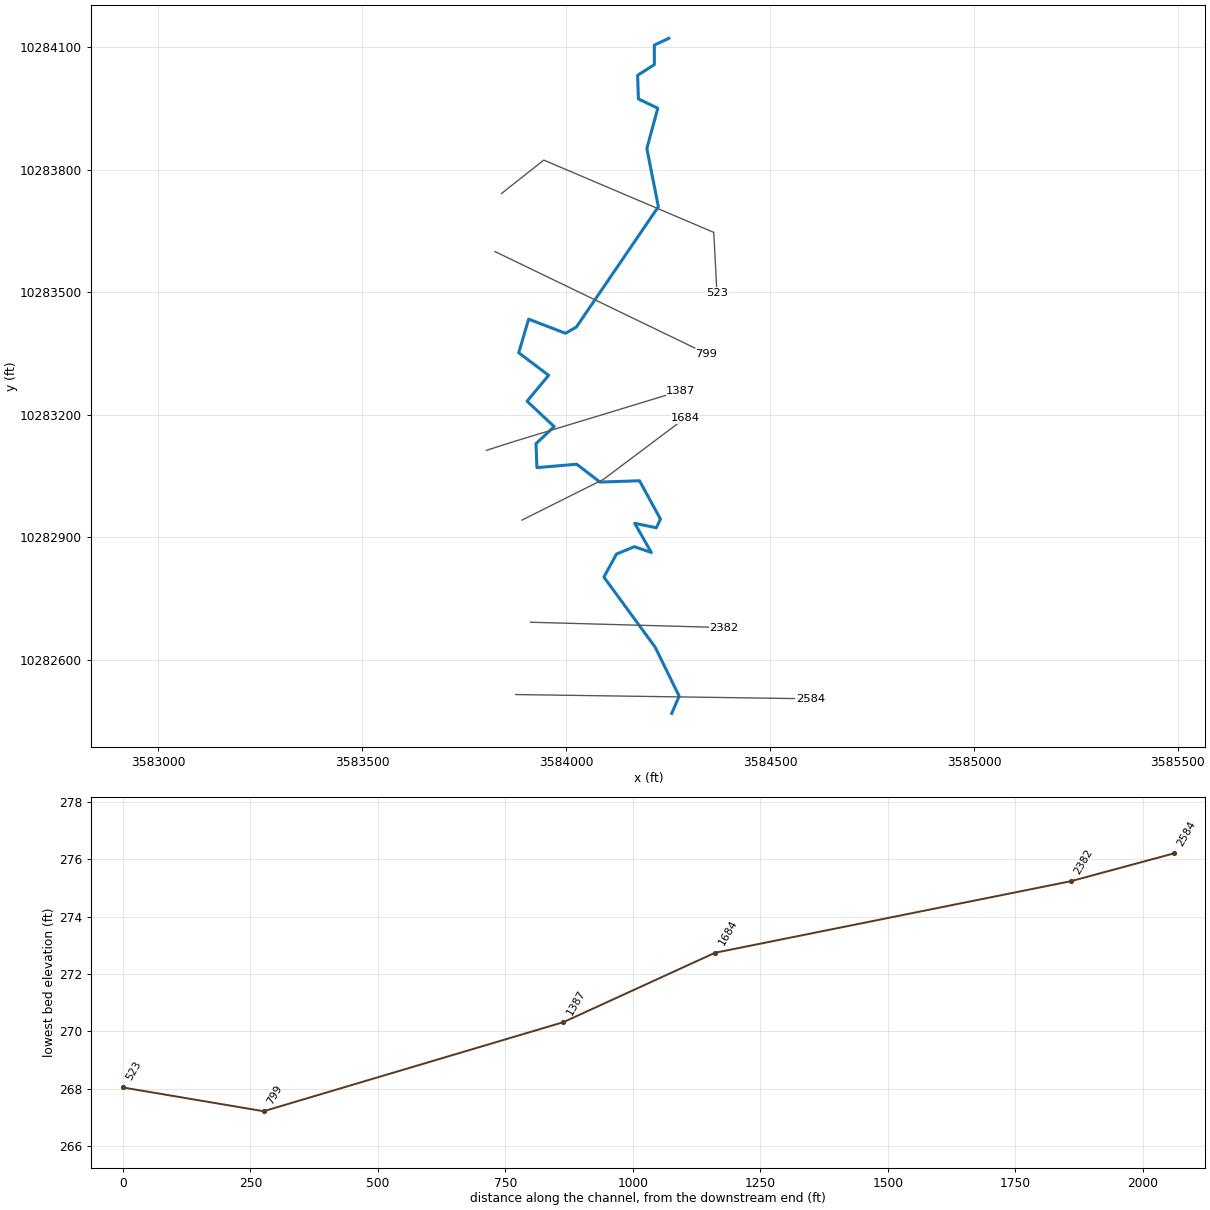
--- SANDCREEKTRIB6.prj (project) ---

Proj Title=SAND CREEK TRIB 6
Current Plan=p01
Default Exp/Contr=0.3,0.1
English Units
Geom File=g01
Flow File=f01
Plan File=p01
Y Axis Title=Elevation
X Axis Title(PF)=Main Channel Distance
X Axis Title(XS)=Station
BEGIN DESCRIPTION:
UNT04791 IN WICK
END DESCRIPTION:
DSS Export Rating Curves= 0
DSS Export Rating Curve Sorted= 0
DSS Export Volume Flow Curves= 0
DXF OffsetX= 0
DXF OffsetY= 0
DXF ScaleX= 1
DXF ScaleY= 10

--- SANDCREEKTRIB6.p01 (plan) ---

Plan Title=Multiple Run
Short Identifier=Multiple
Geom File=g01
Flow File=f01
Subcritical Flow
K Sum by GR= 0
Std Step Tol= 0.01
Critical Tol= 0.01
Num of Std Step Trials= 20
Max Error Tol= 0.3
Flow Tol Ratio= 0.001
Split Flow NTrial= 30
Split Flow Tol= 0.02
Split Flow Ratio= 0.02
Log Output Level= 0
Friction Slope Method= 1
Unsteady Friction Slope Method= 2
Unsteady Bridges Friction Slope Method= 1
Parabolic Critical Depth
Global Vel Dist=  1 , 1 , 1
Global Log Level= 0
CheckData=True
Encroach Param= -1, 0, 0, 0
BEGIN DESCRIPTION:
Multiple Run
END DESCRIPTION:

--- SANDCREEKTRIB6.f01 (steady flow) ---

Flow Title=Multiple
Program Version=4.10
Number of Profiles= 7
Profile Names=10-year,25-year,50-year,1pct_min,100-year,1pct_plu,500-year
River Rch & RM=UNT04791 IN WICK,Reach-1         ,2584
     240     307     359     309     417     564     565
River Rch & RM=SANDCREEKTRIB6,Reach-1         ,2584
     240     307     359     309     417     564     565
Boundary for River Rch & Prof#=SANDCREEKTRIB6,Reach-1         , 1
Up Type= 0
Dn Type= 3
Dn Slope=0.005
Boundary for River Rch & Prof#=SANDCREEKTRIB6,Reach-1         , 2
Up Type= 0
Dn Type= 3
Dn Slope=0.005
Boundary for River Rch & Prof#=SANDCREEKTRIB6,Reach-1         , 3
Up Type= 0
Dn Type= 3
Dn Slope=0.005
Boundary for River Rch & Prof#=SANDCREEKTRIB6,Reach-1         , 4
Up Type= 0
Dn Type= 3
Dn Slope=0.005
Boundary for River Rch & Prof#=SANDCREEKTRIB6,Reach-1         , 5
Up Type= 0
Dn Type= 3
Dn Slope=0.005
Boundary for River Rch & Prof#=SANDCREEKTRIB6,Reach-1         , 6
Up Type= 0
Dn Type= 3
Dn Slope=0.005
Boundary for River Rch & Prof#=SANDCREEKTRIB6,Reach-1         , 7
Up Type= 0
Dn Type= 3
Dn Slope=0.005
DSS Import GetInterval= 0
DSS Import GetPeak= 0
DSS Import FillOption= 0

--- SANDCREEKTRIB6.g01 (geometry) ---

Geom Title=Existing Conditions
Program Version=4.10

River Reach=SANDCREEKTRIB6  ,Reach-1
Reach XY= 30
       3584259.2     10282468.28      3584277.49     10282510.38
       3584218.8     10282630.27      3584092.93     10282802.13
       3584123.8     10282858.46      3584167.58     10282876.51
      3584209.15     10282862.47      3584168.52     10282933.82
      3584221.65     10282922.88      3584231.54     10282944.24
      3584180.27     10283037.98      3584083.31     10283034.79
      3584026.35     10283078.56       3583928.8     10283070.13
      3583926.55     10283128.82      3583971.18     10283170.63
      3583904.61     10283232.89      3583957.58     10283296.18
      3583884.23      10283351.5      3583908.48      10283433.8
      3583998.86     10283399.23      3584025.38     10283414.33
       3584226.5     10283709.25      3584198.27     10283851.59
      3584225.01     10283950.48      3584177.55     10283973.43
      3584175.68     10284031.15       3584216.7     10284057.25
      3584216.61     10284105.04      3584252.11     10284121.64

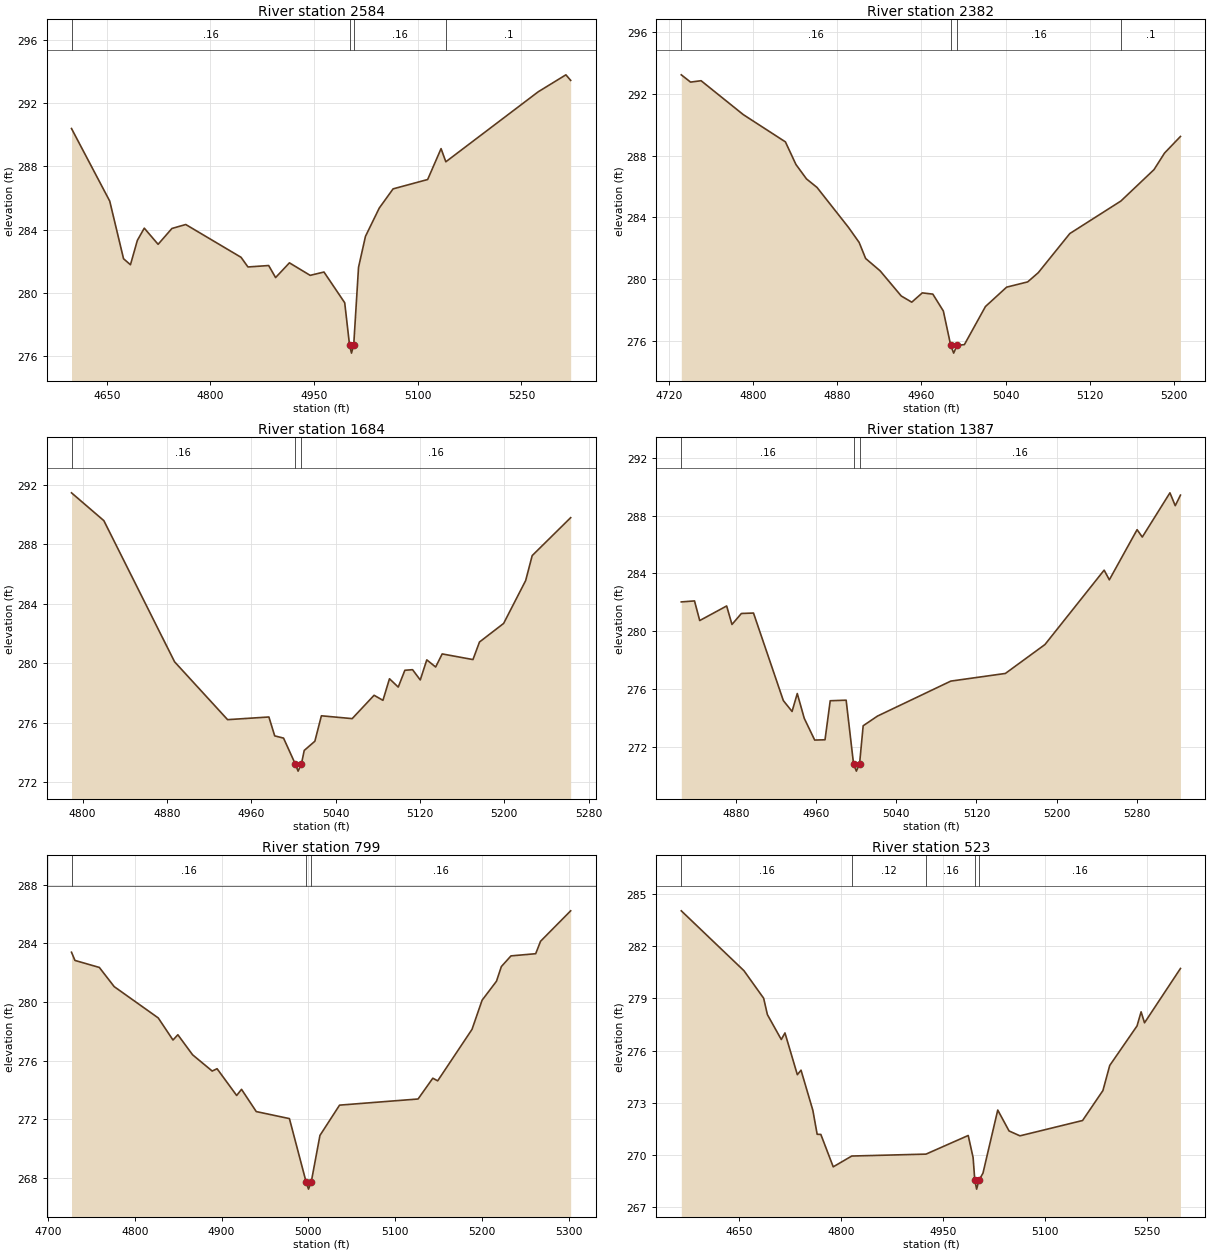
Type RM Length L Ch R = 1 ,2584    ,202,202,202
BEGIN DESCRIPTION:
UNT04791 IN WICK 4.0
END DESCRIPTION:
XS GIS Cut Line= 2
      3583876.83      10282514.4      3584598.96     10282504.01
#Sta/Elev= 30
    4599  290.39  4654.3  285.81  4674.3  282.17  4684.3  281.79  4694.3  283.33
  4704.3   284.1  4724.3  283.08  4744.3  284.08  4764.3  284.33  4844.3  282.26
  4854.3  281.65  4884.3  281.74  4894.3  280.98  4914.3  281.91  4944.3  281.12
  4964.3  281.33  4994.3  279.39  5001.3  276.71  5004.1  276.21  5007.3  276.71
  5014.3  281.63  5024.3  283.58  5044.3  285.37  5064.3  286.58  5114.3  287.17
  5133.7  289.12  5140.6  288.29  5274.3  292.71  5314.3  293.78  5321.2  293.43
#Mann= 4 ,-1 , 0
    4599     .16       0  5001.3     .07       0  5007.3     .16       0
  5140.6      .1       0
Bank Sta=5001.3,5007.3
XS Rating Curve= 0 ,0
Exp/Cntr=0.3,0.1

Type RM Length L Ch R = 1 ,2382    ,698,698,698
BEGIN DESCRIPTION:
Mapping XS 01f7b555
END DESCRIPTION:
XS GIS Cut Line= 2
      3583913.27     10282691.48      3584387.19     10282678.46
#Sta/Elev= 30
    4732  293.21  4740.8  292.74  4750.8  292.83  4790.9  290.64  4830.9  288.88
  4840.9  287.42  4850.9  286.49  4860.9  285.94  4890.9  283.35  4900.9  282.39
  4907.1  281.35  4920.9  280.55  4940.9  278.93  4950.9  278.53  4960.9  279.13
  4970.9  279.05  4980.9  277.96  4987.9  275.74  4990.7  275.24  4993.9  275.74
  5000.9  275.79  5020.9  278.25    5041   279.5    5061  279.84    5071  280.43
    5101  282.96  5149.5  285.06    5181  287.09    5191  288.16  5206.1  289.23
#Mann= 4 ,-1 , 0
    4732     .16       0  4987.9     .07       0  4993.9     .16       0
  5149.5      .1       0
Bank Sta=4987.9,4993.9
XS Rating Curve= 0 ,0
Exp/Cntr=0.3,0.1

Type RM Length L Ch R = 1 ,1684    ,297,297,297
BEGIN DESCRIPTION:
UNT04791 IN WICK 3.0
END DESCRIPTION:
XS GIS Cut Line= 3
      3583892.12     10282941.65      3584092.11     10283041.64
      3584292.12     10283191.65
#Sta/Elev= 30
  4789.4  291.45  4820.1  289.58  4887.2  280.09  4937.5   276.2  4976.7  276.38
  4982.2  275.11  4990.6  274.96  5001.6  273.24  5004.4  272.74  5007.6  273.24
  5010.2  274.13  5020.3  274.75  5026.5  276.46  5055.7  276.27  5076.5  277.84
  5084.9   277.5  5091.1  278.95  5099.4  278.39  5105.7  279.52    5113  279.56
  5120.3  278.87  5126.5  280.22  5134.9  279.74  5141.1  280.62  5170.3  280.24
  5176.5  281.42  5199.4  282.67  5220.3  285.55  5226.5  287.23    5263  289.78
#Mann= 3 ,-1 , 0
  4789.4     .16       0  5001.6     .07       0  5007.6     .16       0
Bank Sta=5001.6,5007.6
XS Rating Curve= 0 ,0
Exp/Cntr=0.3,0.1

Type RM Length L Ch R = 1 ,1387    ,588,588,588
BEGIN DESCRIPTION:
Mapping XS 65b84173
END DESCRIPTION:
XS GIS Cut Line= 3
      3583804.94      10283112.5      3583870.09     10283133.35
      3584281.52     10283258.34
#Sta/Elev= 30
  4825.3  282.03  4838.5   282.1  4843.7  280.74  4870.6  281.75  4875.9  280.47
  4885.3  281.23  4897.4  281.26  4927.2   275.2  4935.9  274.45  4941.1  275.69
  4948.1  273.97  4958.5  272.47  4968.8  272.49    4974  275.19  4989.9  275.23
  4997.3  270.82  5000.1  270.32  5003.3  270.82  5006.9  273.46  5021.2  274.13
  5094.4  276.55  5148.9  277.08  5188.4  279.08  5247.5  284.23  5252.7  283.56
  5280.4  287.03  5285.6  286.52  5313.2  289.58  5318.5  288.69  5323.7  289.42
#Mann= 3 ,-1 , 0
  4825.3     .16       0  4997.3     .07       0  5003.3     .16       0
Bank Sta=4997.3,5003.3
XS Rating Curve= 0 ,0
Exp/Cntr=0.3,0.1

Type RM Length L Ch R = 1 ,799     ,276,276,276
BEGIN DESCRIPTION:
UNT04791 IN WICK 2.0
END DESCRIPTION:
XS GIS Cut Line= 2
      3583825.84     10283599.48      3584344.09     10283349.48
#Sta/Elev= 30
    4727   283.4    4731  282.84  4759.1  282.36  4776.2  281.05    4827  278.91
    4844   277.4  4849.6  277.76  4866.6  276.39  4889.2  275.28  4894.8  275.44
  4917.4  273.61    4923  274.03    4940  272.51  4978.2  272.03  4997.4  267.71
  5000.2  267.21  5003.4  267.71  5013.4  270.88    5036  272.95  5126.5  273.37
  5143.5  274.79  5149.1  274.61  5188.7  278.13  5200.3  280.12  5216.9  281.42
  5222.5  282.42  5233.6  283.15  5262.1   283.3  5267.7  284.15  5302.4  286.23
#Mann= 3 ,-1 , 0
    4727     .16       0  4997.4     .07       0  5003.4     .16       0
Bank Sta=4997.4,5003.4
XS Rating Curve= 0 ,0
Exp/Cntr=0.3,0.1

Type RM Length L Ch R = 1 ,523     ,0,0,0
BEGIN DESCRIPTION:
UNT04791 IN WICK 1.0
END DESCRIPTION:
XS GIS Cut Line= 4
      3583842.12     10283741.65      3583945.61     10283823.45
      3584362.27     10283646.37      3584370.09     10283497.92
#Sta/Elev= 30
  4565.5  284.02  4657.6  280.58  4686.5     279    4692  278.06  4712.4  276.63
  4717.8  277.01    4736  274.61  4741.4  274.87  4758.8  272.56  4765.1  271.19
  4770.5  271.18  4788.7  269.32  4815.9  269.94    4925  270.05    4987  271.12
  4994.2  269.85  4996.7  268.54  4999.4  268.04  5002.7  268.54  5008.7  268.96
  5030.4  272.58    5047  271.38    5063   271.1    5155  271.98  5184.9   273.7
  5194.9  275.14    5235  277.41    5241  278.22    5246  277.59  5298.8  280.71
#Mann= 5 ,-1 , 0
  4565.5     .16       0  4815.9     .12       0    4925     .16       0
  4996.7     .07       0  5002.7     .16       0
Bank Sta=4996.7,5002.7
XS Rating Curve= 0 ,0
Exp/Cntr=0.3,0.1

Chan Stop Cuts=-1
Use User Specified Reach Order=0
Composite Channel Slope=5