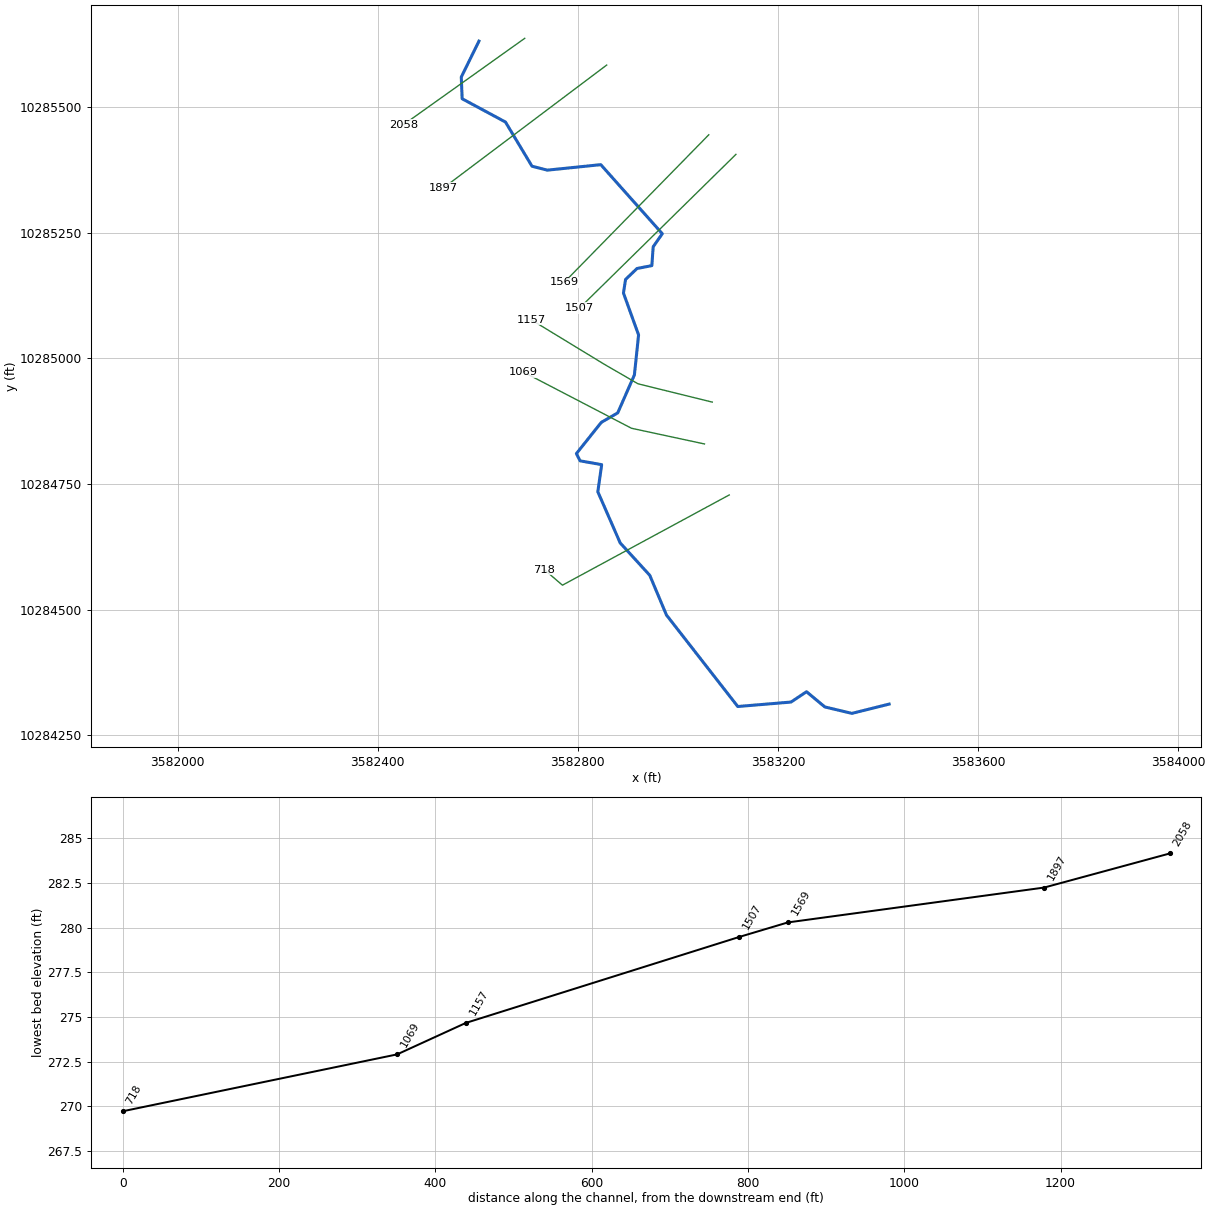
--- SANDCREEKTRIB7.prj (project) ---

Proj Title=SAND CREEK TRIB 7
Current Plan=p01
Default Exp/Contr=0.3,0.1
English Units
Geom File=g01
Flow File=f01
Plan File=p01
Y Axis Title=Elevation
X Axis Title(PF)=Main Channel Distance
X Axis Title(XS)=Station
BEGIN DESCRIPTION:
UNT04789 IN WICK
END DESCRIPTION:
DSS Export Rating Curves= 0
DSS Export Rating Curve Sorted= 0
DSS Export Volume Flow Curves= 0
DXF OffsetX= 0
DXF OffsetY= 0
DXF ScaleX= 1
DXF ScaleY= 10

--- SANDCREEKTRIB7.p01 (plan) ---

Plan Title=Multiple Run
Short Identifier=Multiple
Geom File=g01
Flow File=f01
Subcritical Flow
K Sum by GR= 0
Std Step Tol= 0.01
Critical Tol= 0.01
Num of Std Step Trials= 20
Max Error Tol= 0.3
Flow Tol Ratio= 0.001
Split Flow NTrial= 30
Split Flow Tol= 0.02
Split Flow Ratio= 0.02
Log Output Level= 0
Friction Slope Method= 1
Unsteady Friction Slope Method= 2
Unsteady Bridges Friction Slope Method= 1
Parabolic Critical Depth
Global Vel Dist=  1 , 1 , 1
Global Log Level= 0
CheckData=True
Encroach Param= -1, 0, 0, 0
BEGIN DESCRIPTION:
Multiple Run
END DESCRIPTION:

--- SANDCREEKTRIB7.f01 (steady flow) ---

Flow Title=Multiple
Program Version=4.10
Number of Profiles= 7
Profile Names=10-year,25-year,50-year,1pct_min,100-year,1pct_plu,500-year
River Rch & RM=UNT04789 IN WICK,Reach-1         ,2058
     172     215     247     209     283     382     370
River Rch & RM=SANDCREEKTRIB7,Reach-1         ,2058
     172     215     247     209     283     382     370
Boundary for River Rch & Prof#=SANDCREEKTRIB7,Reach-1         , 1
Up Type= 0
Dn Type= 3
Dn Slope=0.005
Boundary for River Rch & Prof#=SANDCREEKTRIB7,Reach-1         , 2
Up Type= 0
Dn Type= 3
Dn Slope=0.005
Boundary for River Rch & Prof#=SANDCREEKTRIB7,Reach-1         , 3
Up Type= 0
Dn Type= 3
Dn Slope=0.005
Boundary for River Rch & Prof#=SANDCREEKTRIB7,Reach-1         , 4
Up Type= 0
Dn Type= 3
Dn Slope=0.005
Boundary for River Rch & Prof#=SANDCREEKTRIB7,Reach-1         , 5
Up Type= 0
Dn Type= 3
Dn Slope=0.005
Boundary for River Rch & Prof#=SANDCREEKTRIB7,Reach-1         , 6
Up Type= 0
Dn Type= 3
Dn Slope=0.005
Boundary for River Rch & Prof#=SANDCREEKTRIB7,Reach-1         , 7
Up Type= 0
Dn Type= 3
Dn Slope=0.005
DSS Import GetInterval= 0
DSS Import GetPeak= 0
DSS Import FillOption= 0

--- SANDCREEKTRIB7.g01 (geometry) ---

Geom Title=Existing Conditions
Program Version=4.10

River Reach=SANDCREEKTRIB7  ,Reach-1
Reach XY= 30
      3582602.39     10285631.89      3582567.05     10285560.29
       3582568.8     10285517.14      3582655.38     10285470.77
      3582708.39     10285382.77      3582739.12     10285374.96
      3582845.89     10285385.89       3582968.8     10285248.39
      3582950.57     10285222.35      3582947.97     10285184.85
      3582918.28     10285179.12      3582895.37     10285157.25
       3582891.2     10285130.16      3582921.41     10285046.83
      3582913.07     10284967.14      3582879.74     10284891.62
      3582846.88     10284872.64      3582797.13     10284810.49
      3582804.48      10284796.1      3582847.65     10284788.48
      3582839.95     10284734.54      3582884.61     10284632.69
      3582943.79      10284568.1      3582977.15     10284489.02
      3583119.66     10284306.85      3583226.07     10284315.72
      3583257.09     10284336.32      3583293.71     10284305.95
      3583347.77     10284293.18      3583422.11     10284311.64

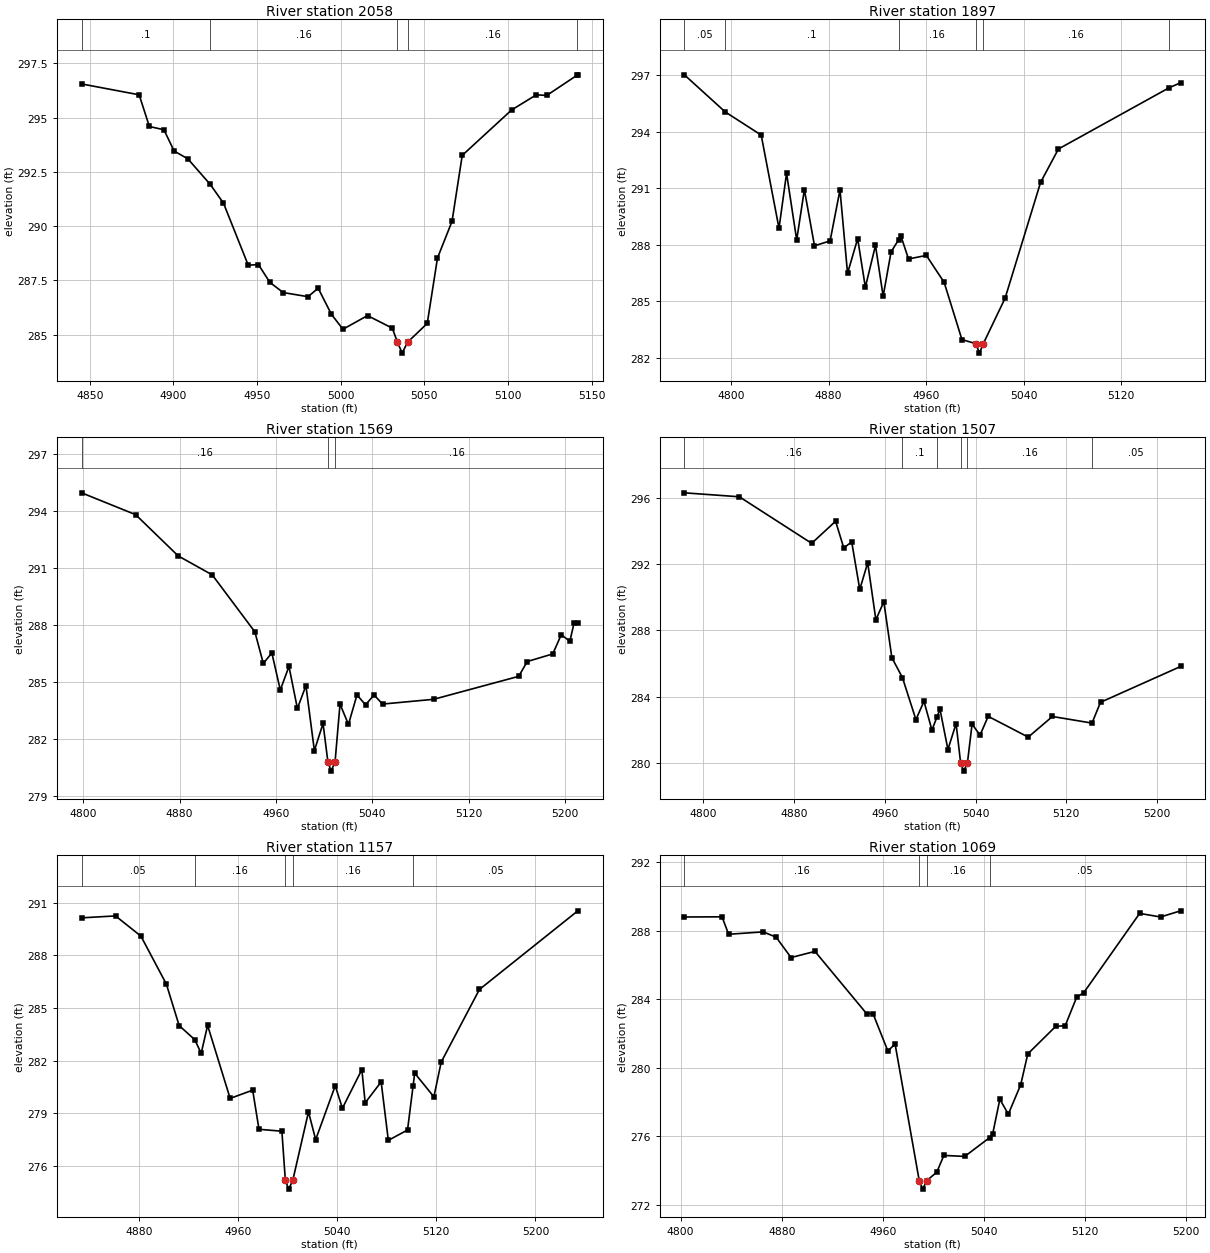
Type RM Length L Ch R = 1 ,2058    ,161,161,161
BEGIN DESCRIPTION:
UNT04789 IN WICK 3.0
END DESCRIPTION:
XS GIS Cut Line= 2
      3582693.87     10285637.45        3582452.     10285465.77
#Sta/Elev= 30
  4845.1  296.55  4879.5  296.05  4885.6  294.59  4894.3  294.44  4900.4  293.46
  4908.6   293.1  4921.9  291.93  4929.9  291.06  4944.7   288.2  4950.8  288.23
  4957.6  287.41  4965.6  286.94  4980.4  286.75  4986.5  287.14  4994.4  285.94
  5001.3  285.25    5016  285.88  5030.8   285.3  5033.9  284.65  5036.7  284.15
  5039.9  284.65  5051.7  285.52  5057.8  288.53  5066.5  290.22  5072.6  293.26
  5102.1  295.35  5116.9  296.05  5123.1  296.02  5141.4  296.96  5141.7  296.97
#Mann= 5 ,-1 , 0
  4845.1      .1       0  4921.9     .16       0  5033.9     .07       0
  5039.9     .16       0  5141.4     .05       0
Bank Sta=5033.9,5039.9
XS Rating Curve= 0 ,0
Exp/Cntr=0.3,0.1

Type RM Length L Ch R = 1 ,1897    ,328,328,328
BEGIN DESCRIPTION:
Mapping XS 3c91a9c4
END DESCRIPTION:
XS GIS Cut Line= 2
       3582857.7     10285584.27      3582532.18     10285340.13
#Sta/Elev= 30
  4761.7  297.02  4795.2  295.05  4824.7  293.82  4839.3  288.87  4845.5  291.79
  4853.8  288.25  4860.1  290.92  4868.4  287.94  4881.2   288.2  4889.3  290.91
  4895.5  286.48  4903.8  288.32  4910.1  285.74  4918.4  287.96  4924.7  285.26
  4931.2  287.62  4937.3  288.25  4939.3  288.45  4945.5  287.24  4960.1  287.43
  4974.7     286  4989.3  282.96  5000.8  282.74  5003.6  282.24  5006.8  282.74
  5024.7  285.16  5053.8  291.31  5068.4  293.08  5159.1  296.33  5168.6   296.6
#Mann= 6 ,-1 , 0
  4761.7     .05       0  4795.2      .1       0  4937.3     .16       0
  5000.8     .07       0  5006.8     .16       0  5159.1     .05       0
Bank Sta=5000.8,5006.8
XS Rating Curve= 0 ,0
Exp/Cntr=0.3,0.1

Type RM Length L Ch R = 1 ,1569    ,62,62,62
BEGIN DESCRIPTION:
Mapping XS 8ada1a5b
END DESCRIPTION:
XS GIS Cut Line= 2
      3583061.74     10285445.42       3582772.8     10285151.58
#Sta/Elev= 30
  4798.6  294.94  4843.5  293.79  4878.8  291.62  4907.1  290.62  4942.5  287.62
  4949.5  285.96  4956.6  286.51  4963.6  284.56  4970.8   285.8  4977.8  283.59
  4984.9  284.79  4991.9  281.37  4999.1   282.8  5003.1  280.79  5005.8  280.29
  5009.1  280.79  5013.2  283.82  5020.2  282.75  5027.3   284.3  5034.4  283.78
  5041.5   284.3  5048.5  283.82  5090.9  284.07  5161.6  285.28  5168.7  286.06
  5189.9  286.46  5196.9  287.47  5204.1  287.13  5207.6   288.1  5210.7   288.1
#Mann= 3 ,-1 , 0
  4798.6     .16       0  5003.1     .07       0  5009.1     .16       0
Bank Sta=5003.1,5009.1
XS Rating Curve= 0 ,0
Exp/Cntr=0.3,0.1

Type RM Length L Ch R = 1 ,1507    ,350,350,350
BEGIN DESCRIPTION:
UNT04789 IN WICK 2.0
END DESCRIPTION:
XS GIS Cut Line= 2
        3583116.     10285406.37      3582803.47     10285100.35
#Sta/Elev= 30
  4783.3  296.34  4831.8   296.1  4895.5  293.28  4916.6  294.62  4923.8     293
  4930.8  293.37  4937.9  290.49  4944.9   292.1  4952.1  288.65  4959.1  289.74
  4966.2  286.35  4975.5  285.15  4987.4   282.6  4994.5  283.71  5001.5  281.97
  5005.8  282.73  5008.6  283.23  5015.6  280.79  5022.8  282.36  5026.8  279.98
  5029.5  279.48  5032.8  279.98  5036.9  282.33  5043.9  281.66  5051.1   282.8
  5086.4  281.54  5107.7  282.79  5142.6  282.39  5150.1  283.65  5220.7  285.82
#Mann= 6 ,-1 , 0
  4783.3     .16       0  4975.5      .1       0  5005.8     .16       0
  5026.8     .07       0  5032.8     .16       0  5142.6     .05       0
Bank Sta=5026.8,5032.8
XS Rating Curve= 0 ,0
Exp/Cntr=0.3,0.1

Type RM Length L Ch R = 1 ,1157    ,88,88,88
BEGIN DESCRIPTION:
Mapping XS fae07e61
END DESCRIPTION:
XS GIS Cut Line= 4
      3583068.67     10284913.04      3582920.26      10284949.5
      3582852.55     10284988.56      3582707.31     10285076.74
#Sta/Elev= 30
  4833.4  290.13  4860.8  290.24  4881.3  289.09  4901.9  286.35  4912.2  283.99
  4924.8  283.19    4930  282.41  4935.2     284  4953.4  279.84  4971.6  280.31
  4976.7  278.08  4995.2  277.97    4998  275.17  5000.7  274.67    5004  275.17
  5016.7  279.07  5022.5  277.49  5038.3  280.56  5044.1  279.28  5059.8  281.48
  5062.5  279.59  5075.4  280.78  5081.2  277.45  5096.7  278.04  5101.2  280.55
  5102.5  281.28    5118  279.93  5123.9  281.91  5154.8  286.05  5234.3  290.53
#Mann= 5 ,-1 , 0
  4833.4     .05       0  4924.8     .16       0    4998     .07       0
    5004     .16       0  5101.2     .05       0
Bank Sta=4998,5004
XS Rating Curve= 0 ,0
Exp/Cntr=0.3,0.1

Type RM Length L Ch R = 1 ,1069    ,351,351,351
BEGIN DESCRIPTION:
Mapping XS c45e1196
END DESCRIPTION:
XS GIS Cut Line= 3
      3583053.08      10284829.7      3582907.24     10284860.95
      3582691.08     10284972.94
#Sta/Elev= 30
    4803  288.81  4832.8  288.82    4838   287.8  4865.4  287.94  4875.6  287.63
  4887.4  286.44  4906.3   286.8  4947.1  283.17  4952.2  283.17    4964  280.98
  4969.7  281.39  4988.8  273.41  4991.6  272.91  4994.8  273.41  5002.7   273.9
  5008.3  274.88  5024.8  274.82  5044.5  275.92  5046.9  276.13  5052.6  278.16
  5059.3  277.29  5069.1  279.01  5074.7  280.81  5096.8  282.42  5104.3  282.46
  5113.3  284.11    5119  284.39  5163.2  289.02  5179.7  288.81  5195.6  289.17
#Mann= 4 ,-1 , 0
    4803     .16       0  4988.8     .07       0  4994.8     .16       0
  5044.5     .05       0
Bank Sta=4988.8,4994.8
XS Rating Curve= 0 ,0
Exp/Cntr=0.3,0.1

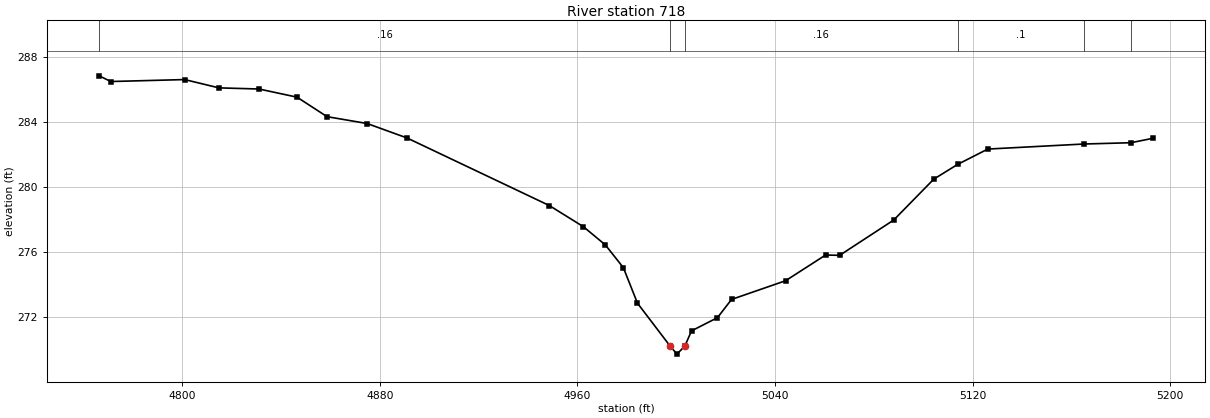
Type RM Length L Ch R = 1 ,718     ,0,0,0
BEGIN DESCRIPTION:
UNT04789 IN WICK 1.0
END DESCRIPTION:
XS GIS Cut Line= 3
      3583102.58     10284728.15      3582769.22     10284548.45
      3582732.78     10284579.69
#Sta/Elev= 30
  4766.3  286.83    4771  286.48  4800.9   286.6  4814.8  286.09    4831  286.02
  4846.4  285.52  4858.6  284.32  4874.8   283.9    4891  283.01  4948.6  278.86
  4962.4  277.56  4971.3  276.44  4978.6  275.04  4984.3  272.86  4997.5  270.23
  5000.3  269.73  5003.5  270.23  5006.2  271.16  5016.7  271.97  5022.4  273.09
  5044.3  274.24  5060.5  275.82  5066.2   275.8  5088.1  277.97  5104.3  280.48
    5114  281.39  5126.2  282.33  5165.1  282.64  5184.2  282.72    5193  282.99
#Mann= 6 ,-1 , 0
  4766.3     .16       0  4997.5     .07       0  5003.5     .16       0
    5114      .1       0  5165.1     .16       0  5184.2      .1       0
Bank Sta=4997.5,5003.5
XS Rating Curve= 0 ,0
Exp/Cntr=0.3,0.1

Chan Stop Cuts=-1
Use User Specified Reach Order=0
Composite Channel Slope=5