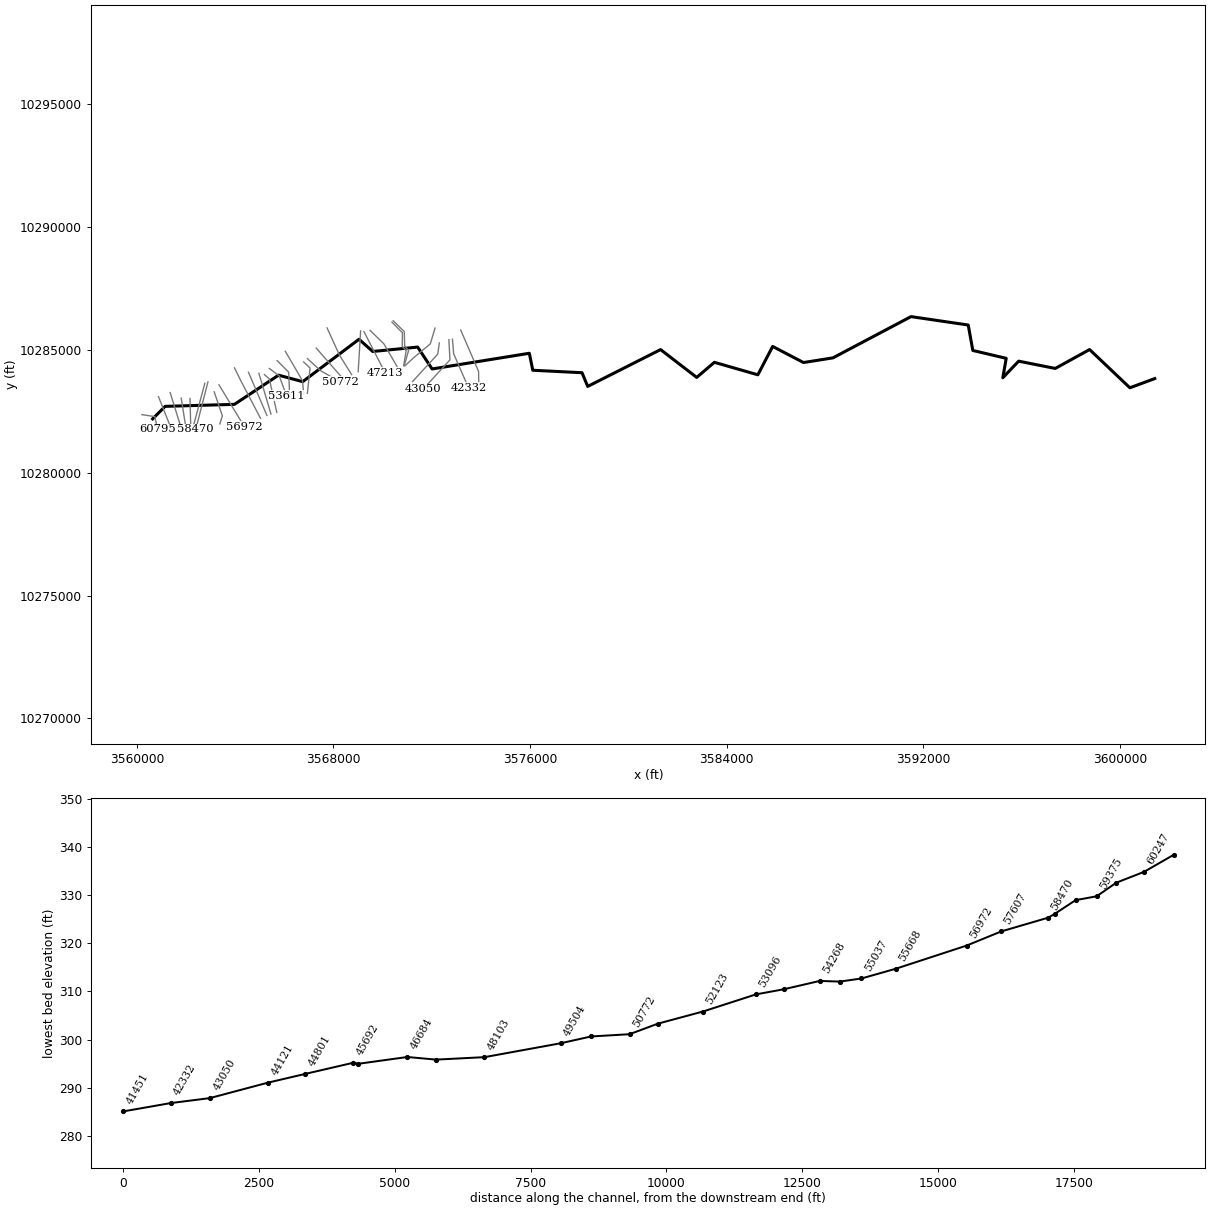
--- SAND CREEK.prj (project) ---

Proj Title=SAND CREEK Base Level Engineering
Current Plan=p01
Default Exp/Contr=0.3,0.1
English Units
Geom File=g01
Flow File=f01
Plan File=p01
Y Axis Title=Elevation
X Axis Title(PF)=Main Channel Distance
X Axis Title(XS)=Station
BEGIN DESCRIPTION:
SAND CREEK
END DESCRIPTION:
DSS Export Rating Curves= 0
DSS Export Rating Curve Sorted= 0
DSS Export Volume Flow Curves= 0
DXF OffsetX= 0
DXF OffsetY= 0
DXF ScaleX= 1
DXF ScaleY= 10

--- SAND CREEK.p01 (plan) ---

Plan Title=Multiple Run
Short Identifier=Multiple
Geom File=g01
Flow File=f01
Subcritical Flow
K Sum by GR= 0
Std Step Tol= 0.01
Critical Tol= 0.01
Num of Std Step Trials= 20
Max Error Tol= 0.3
Flow Tol Ratio= 0.001
Split Flow NTrial= 30
Split Flow Tol= 0.02
Split Flow Ratio= 0.02
Log Output Level= 0
Friction Slope Method= 1
Unsteady Friction Slope Method= 2
Unsteady Bridges Friction Slope Method= 1
Parabolic Critical Depth
Global Vel Dist=  1 , 1 , 1
Global Log Level= 0
CheckData=True
Encroach Param= -1, 0, 0, 0
BEGIN DESCRIPTION:
Multiple Run
END DESCRIPTION:

--- SAND CREEK.f01 (steady flow) ---

Flow Title=Multiple
Program Version=4.10
Number of Profiles= 7
Profile Names=10-year,25-year,50-year,1pct_min,100-year,1pct_plu,500-year
River Rch & RM=SAND CREEK,Reach-1         ,60795
     219     277     321     274     370     501     492
River Rch & RM=SAND CREEK,Reach-1         ,58604
     753    1019    1236    1096    1482    2005    2138
River Rch & RM=SAND CREEK,Reach-1         ,57607
     753    1019    1236    1096    1482    2005    2138
River Rch & RM=SAND CREEK,Reach-1         ,55037
     829    1123    1362    1207    1632    2207    2351
River Rch & RM=SAND CREEK,Reach-1         ,50772
    1134    1561    1914    1713    2317    3133    3406
River Rch & RM=SAND CREEK,Reach-1         ,40047
    1577    2192    2705    2435    3293    4453    4893
River Rch & RM=SAND CREEK,Reach-1         ,36135
    1908    2676    3323    3007    4067    5500    6114
River Rch & RM=SAND CREEK,Reach-1         ,32646
    2038    2861    3554    3217    4351    5884    6542
River Rch & RM=SAND CREEK,Reach-1         ,27273
    2086    2930    3640    3296    4458    6028    6705
River Rch & RM=SAND CREEK,Reach-1         ,26201
    2158    3036    3777    3425    4632    6264    6987
River Rch & RM=SAND CREEK,Reach-1         ,25016
    2121    2975    3694    3342    4519    6112    6785
River Rch & RM=SAND CREEK,Reach-1         ,22272
    2208    3096    3843    3475    4700    6356    7050
River Rch & RM=SAND CREEK,Reach-1         ,12211
    2332    3275    4070    3683    4981    6737    7486
Boundary for River Rch & Prof#=SAND CREEK,Reach-1         , 1
Up Type= 0
Dn Type= 3
Dn Slope=0.00144
Boundary for River Rch & Prof#=SAND CREEK,Reach-1         , 2
Up Type= 0
Dn Type= 3
Dn Slope=0.00144
Boundary for River Rch & Prof#=SAND CREEK,Reach-1         , 3
Up Type= 0
Dn Type= 3
Dn Slope=0.00144
Boundary for River Rch & Prof#=SAND CREEK,Reach-1         , 4
Up Type= 0
Dn Type= 3
Dn Slope=0.00144
Boundary for River Rch & Prof#=SAND CREEK,Reach-1         , 5
Up Type= 0
Dn Type= 3
Dn Slope=0.00144
Boundary for River Rch & Prof#=SAND CREEK,Reach-1         , 6
Up Type= 0
Dn Type= 3
Dn Slope=0.00144
Boundary for River Rch & Prof#=SAND CREEK,Reach-1         , 7
Up Type= 0
Dn Type= 3
Dn Slope=0.00144
DSS Import GetInterval= 0
DSS Import GetPeak= 0
DSS Import FillOption= 0

--- SAND CREEK.g01 (geometry) ---

Geom Title=Existing Conditions
Program Version=4.10

River Reach=SAND CREEK      ,Reach-1
Reach XY= 30
      3560644.25     10282190.18       3561152.7     10282700.28
      3563972.11     10282781.64      3565767.27     10283969.05
      3566750.71     10283704.98      3569042.08     10285430.33
      3569598.05     10284932.99      3571427.45     10285112.09
      3572015.76     10284221.97      3575972.29     10284860.57
      3576112.41     10284169.28      3578116.51      10284069.6
      3578346.88     10283511.44      3581312.46     10285010.47
      3582782.37     10283878.18      3583501.64     10284491.69
      3585271.04     10283984.29       3585873.6     10285138.05
       3587127.9     10284483.32      3588326.48     10284673.38
      3591502.13     10286351.68      3593831.41     10286009.71
      3594018.16     10284975.05      3595377.11     10284654.24
      3595238.06     10283863.09       3595883.3     10284539.09
      3597371.58     10284242.89      3598769.41     10285011.84
      3600409.17     10283455.54      3601422.07     10283831.24

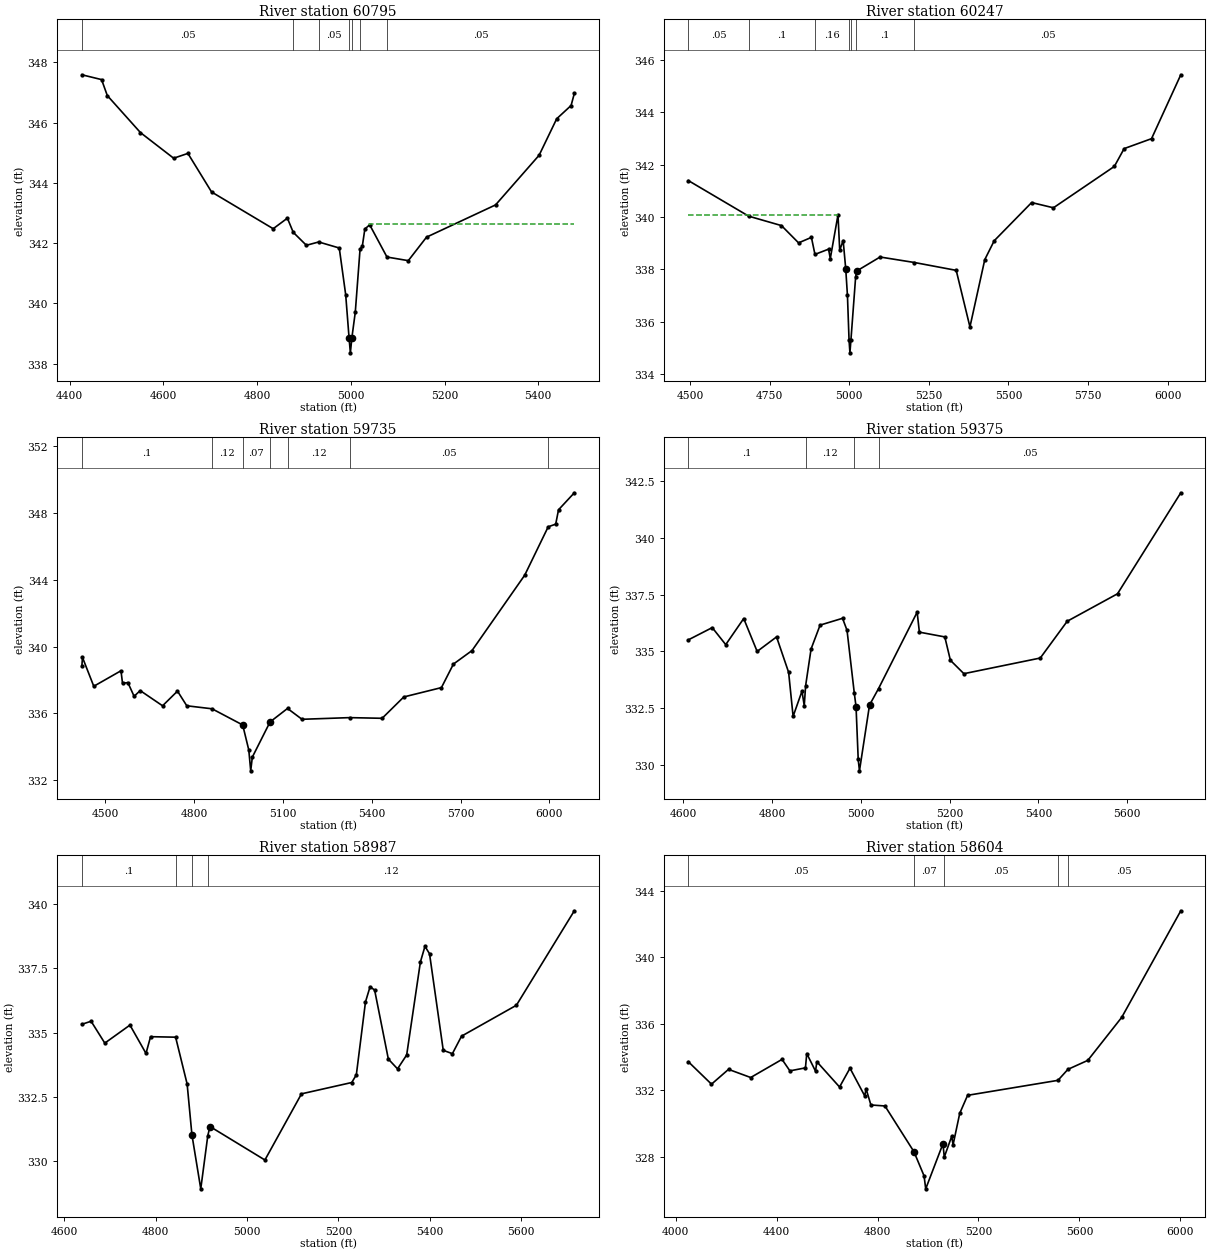
Type RM Length L Ch R = 1 ,60795   ,548,548,548
BEGIN DESCRIPTION:
SAND CREEK 94.0
END DESCRIPTION:
XS GIS Cut Line= 3
      3560208.43     10282363.43       3560732.7     10282283.58
      3560843.43      10281774.9
#Sta/Elev= 30
    4426  347.59  4468.1  347.43  4480.3   346.9  4551.1  345.67  4621.9  344.82
  4652.3  344.98  4702.8   343.7  4834.3  342.48  4864.6  342.83  4877.1  342.36
  4905.1  341.93  4931.4  342.04  4975.3  341.84    4989  340.29  4996.2  338.86
    4999  338.36  5002.2  338.86  5009.5  339.71  5019.7  341.81  5024.4  341.89
  5029.9  342.47  5040.2  342.61  5077.1  341.54  5122.6  341.42  5161.5   342.2
  5308.8  343.27  5401.8  344.92  5439.3  346.13    5470  346.57  5476.9  346.97
#Mann= 7 ,-1 , 0
    4426     .05       0  4877.1      .1       0  4931.4     .05       0
  4996.2     .03       0  5002.2     .05       0  5019.7      .1       0
  5077.1     .05       0
#XS Ineff= 2 , 0
                         5039.23          342.63
Permanent Ineff=
       F       F
Bank Sta=4996.2,5002.2
XS Rating Curve= 0 ,0
Exp/Cntr=0.3,0.1

Type RM Length L Ch R = 1 ,60247   ,512,512,512
BEGIN DESCRIPTION:
SAND CREEK 93.0
END DESCRIPTION:
XS GIS Cut Line= 2
        3560883.     10283093.46      3561455.78      10281656.3
#Sta/Elev= 30
  4494.5  341.39  4684.1  340.03  4787.1  339.67  4840.9  339.01  4881.2  339.22
  4892.3  338.57  4935.1  338.77  4940.5  338.41  4964.7  340.08  4970.1  338.73
  4980.9   339.1    4989  338.02  4994.4     337  4999.4  335.31  5002.2  334.81
  5005.4  335.31  5020.2  337.72  5024.1  337.94  5096.9  338.47  5204.9  338.26
  5336.1  337.96  5379.2   335.8  5425.8  338.37  5455.4  339.09    5573  340.55
  5641.5  340.35  5832.9  341.93  5863.6  342.61  5949.7  342.99  6041.6  345.43
#Mann= 7 ,-1 , 0
  4494.5     .05       0  4684.1      .1       0  4892.3     .16       0
  4999.4     .07       0  5005.4     .16       0  5020.2      .1       0
  5204.9     .05       0
#XS Ineff= 2 , 0
         4964.55  340.08
Permanent Ineff=
       F       F
Bank Sta=4989,5024.1
XS Rating Curve= 0 ,0
Exp/Cntr=0.3,0.1

Type RM Length L Ch R = 1 ,59735   ,360,360,360
BEGIN DESCRIPTION:
SAND CREEK 92.0
END DESCRIPTION:
XS GIS Cut Line= 2
      3561356.96     10283260.14      3561851.74     10281671.61
#Sta/Elev= 30
  4420.5  338.81  4422.6  339.35  4460.8  337.62  4552.7  338.55  4557.9   337.8
    4576  337.84    4597  337.02  4617.7  337.36  4693.2  336.45  4743.6  337.33
    4775  336.45  4860.3  336.27  4963.9   335.3  4984.5   333.8    4991  332.55
  4996.4  333.37  5056.3  335.48  5115.3  336.29  5164.3  335.64  5324.9  335.74
    5435   335.7  5508.2  336.98  5635.3  337.54  5675.8  338.95  5738.6  339.76
  5916.7  344.28    5996  347.18  6021.4  347.34  6030.9   348.2  6084.3  349.22
#Mann= 7 ,-1 , 0
  4420.5      .1       0  4860.3     .12       0  4963.9     .07       0
  5056.3     .05       0  5115.3     .12       0  5324.9     .05       0
    5996      .1       0
Bank Sta=4963.9,5056.3
XS Rating Curve= 0 ,0
Exp/Cntr=0.3,0.1

Type RM Length L Ch R = 1 ,59375   ,388,388,388
BEGIN DESCRIPTION:
Mapping XS 7fdfe7ea
END DESCRIPTION:
XS GIS Cut Line= 2
      3561806.29     10283034.87       3561979.9     10281938.94
#Sta/Elev= 30
  4611.4  335.51  4665.3  336.05  4695.7   335.3  4736.2  336.45  4766.5     335
  4810.2  335.64  4837.4  334.08  4847.5  332.14  4867.5  333.25  4872.6  332.61
  4875.7  333.49    4888  335.11  4908.3  336.16  4958.9  336.46    4969  335.93
 4985.45  333.15  4989.3  332.57  4994.2  330.24    4997  329.74  5019.7  332.64
  5039.9  333.36    5127  336.73    5132  335.85  5189.3  335.64  5201.9  334.61
  5232.3  334.02  5404.4  334.71  5465.1  336.33  5578.4  337.54    5721  341.99
#Mann= 4 ,-1 , 0
  4611.4      .1       0  4875.7     .12       0 4985.45     .07       0
  5039.9     .05       0
Bank Sta=4989.3,5019.7
XS Rating Curve= 0 ,0
Exp/Cntr=0.3,0.1

Type RM Length L Ch R = 1 ,58987   ,383,383,383
BEGIN DESCRIPTION:
Mapping XS 7beaf7e8
END DESCRIPTION:
XS GIS Cut Line= 2
      3562164.36     10283021.86      3562192.52     10281945.03
#Sta/Elev= 30
  4638.8  335.32    4659  335.44    4689  334.59    4744  335.29  4779.1  334.19
  4789.1  334.84  4843.9  334.82  4869.1     333 4879.55  331.03  4898.9  328.93
 4914.32     331  4919.1  331.35  5039.2  330.05  5119.2  332.62  5229.2  333.06
  5239.2  333.36  5259.2  336.19  5269.2  336.78  5279.2  336.65  5309.2  333.97
  5329.3  333.59  5349.3  334.13  5379.3  337.74  5389.3  338.35  5399.3  338.06
  5429.3  334.31  5449.3  334.18  5469.3  334.86  5589.3  336.06    5716  339.73
#Mann= 4 ,-1 , 0
  4638.8      .1       0  4843.9     .12       0 4879.55     .07       0
 4914.32     .12       0
Bank Sta=4879.55,4919.1
XS Rating Curve= 0 ,0
Exp/Cntr=0.3,0.1

Type RM Length L Ch R = 1 ,58604   ,123,123,123
BEGIN DESCRIPTION:
SAND CREEK 91.0
END DESCRIPTION:
XS GIS Cut Line= 2
       3562768.4     10283640.34      3562263.43     10281755.82
#Sta/Elev= 30
  4050.5  333.73  4142.3  332.38  4209.8  333.27  4297.6  332.78  4421.8  333.87
  4452.9  333.18  4514.5  333.36  4519.7  334.22  4554.5  333.16  4559.7  333.73
  4649.6  332.21    4691  333.34  4749.5  331.67  4754.6  332.11  4773.8  331.13
  4829.5  331.07  4944.4  328.32  4984.4  326.87    4991  326.09  5059.3   328.8
  5064.5     328  5094.1  329.25  5099.3  328.73  5125.8  330.63  5156.9  331.71
  5514.9  332.61  5554.3  333.27  5633.1  333.81  5767.7   336.4  6001.5   342.8
#Mann= 5 ,-1 , 0
  4050.5     .05       0  4944.4     .07       0  5064.5     .05       0
  5514.9      .1       0  5554.3     .05       0
Bank Sta=4944.4,5059.3
XS Rating Curve= 0 ,0
Exp/Cntr=0.3,0.1

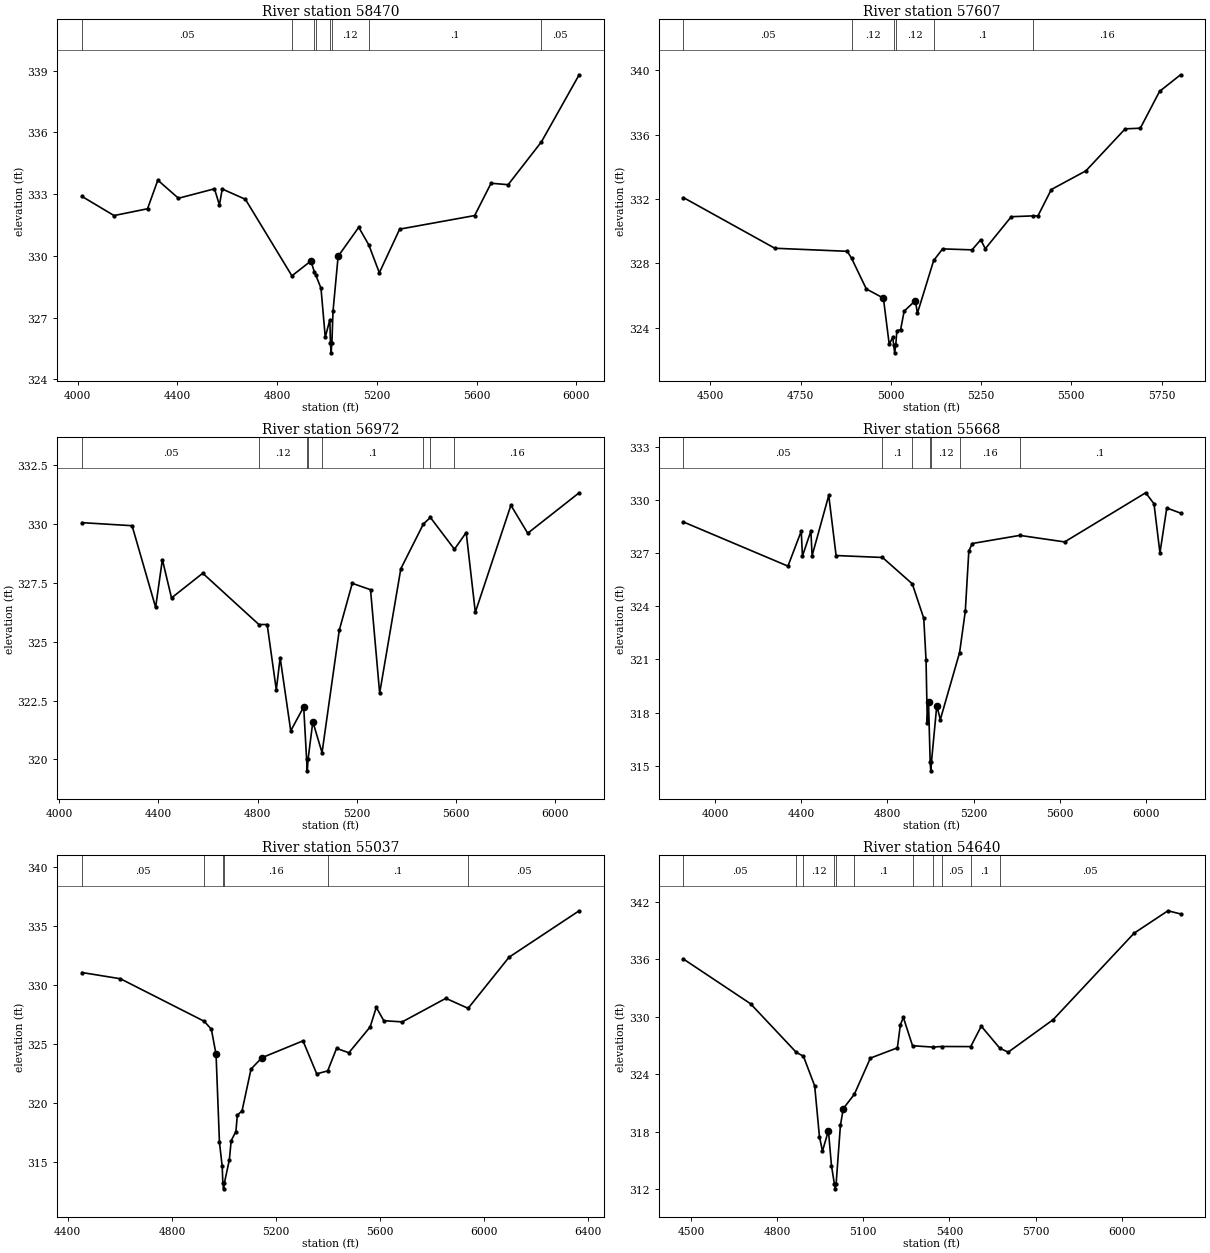
Type RM Length L Ch R = 1 ,58470   ,863,863,863
BEGIN DESCRIPTION:
SAND CREEK 90.0
END DESCRIPTION:
XS GIS Cut Line= 2
      3562895.57     10283696.16      3562398.77     10281765.96
#Sta/Elev= 30
  4017.7  332.89  4146.3  331.96  4280.5  332.29  4321.8  333.68  4404.4   332.8
    4549  333.26  4568.8  332.47    4580  333.25  4672.9  332.75  4859.3  329.03
  4935.2  329.75  4949.8  329.21  4955.2  329.06  4975.9  328.43    4993  326.05
  5011.5   326.9  5013.7  325.79  5016.4  325.29  5019.7  325.79    5024   327.3
  5044.6  329.98  5127.2  331.39  5167.7  330.53  5209.8  329.18  5291.3   331.3
  5591.9  331.96  5657.7  333.53  5726.1  333.46  5859.5  335.54  6010.8   338.8
#Mann= 8 ,-1 , 0
  4017.7     .05       0  4859.3     .12       0  4949.8     .05       0
  4955.2     .12       0  5013.7     .07       0  5019.7     .12       0
  5167.7      .1       0  5859.5     .05       0
Bank Sta=4935.2,5044.6
XS Rating Curve= 0 ,0
Exp/Cntr=0.3,0.1

Type RM Length L Ch R = 1 ,57607   ,635,635,635
BEGIN DESCRIPTION:
SAND CREEK 89.0
END DESCRIPTION:
XS GIS Cut Line= 3
       3563148.6     10283291.45      3563481.95     10282312.24
      3563378.19      10281985.4
#Sta/Elev= 30
  4425.3  332.09  4678.6  328.94  4879.3  328.75  4891.4  328.31  4932.1  326.41
  4979.4  325.84  4995.5  322.98  5005.5   323.4  5007.8  322.94  5010.6  322.44
  5013.8  322.94  5016.7  323.81  5027.2  323.89  5036.9  325.03  5068.2  325.69
  5073.5  324.89  5118.7  328.18  5143.4   328.9    5225  328.84  5249.1  329.47
  5261.7  328.91  5333.6   330.9  5392.5  330.95  5407.5  330.95  5444.6  332.59
  5540.4  333.75  5649.2  336.36  5691.1   336.4  5744.5  338.69  5802.6  339.72
#Mann= 6 ,-1 , 0
  4425.3     .05       0  4891.4     .12       0  5007.8     .07       0
  5013.8     .12       0  5118.7      .1       0  5392.5     .16       0
Bank Sta=4979.4,5068.2
XS Rating Curve= 0 ,0
Exp/Cntr=0.3,0.1

Type RM Length L Ch R = 1 ,56972   ,1304,1304,1304
BEGIN DESCRIPTION:
SAND CREEK 88.0
END DESCRIPTION:
XS GIS Cut Line= 2
      3563341.33     10283577.86      3564382.31     10281865.44
#Sta/Elev= 30
  4092.1  330.06  4294.1  329.93    4389  326.46  4416.2  328.49    4453  326.86
  4578.9  327.91  4805.2  325.73  4838.6  325.73  4875.4  322.95  4890.9  324.32
  4933.6  321.21  4985.8  322.23  4997.5  320.01  5000.2  319.51  5003.5  320.01
  5022.7   321.6  5059.8  320.28  5129.3  325.49  5181.6  327.48  5255.2  327.21
    5292  322.81  5377.3   328.1  5468.1     330  5496.5  330.28  5593.5  328.93
  5640.8  329.64  5677.6  326.25    5821   330.8  5888.8  329.61  6096.1  331.33
#Mann= 8 ,-1 , 0
  4092.1     .05       0  4805.2     .12       0  4997.5     .07       0
  5003.5     .12       0  5059.8      .1       0  5468.1     .16       0
  5496.5      .1       0  5593.5     .16       0
Bank Sta=4985.8,5022.7
XS Rating Curve= 0 ,0
Exp/Cntr=0.3,0.1

Type RM Length L Ch R = 1 ,55668   ,631,631,631
BEGIN DESCRIPTION:
SAND CREEK 86.0
END DESCRIPTION:
XS GIS Cut Line= 3
      3563973.17      10284265.9      3564247.57     10283713.28
      3565033.17     10282214.93
#Sta/Elev= 30
  3852.6  328.78  4338.3  326.28    4400  328.26  4405.6  326.85  4444.8  328.27
  4450.4  326.87  4527.7  330.28  4561.8  326.88  4777.3  326.77  4915.6  325.28
  4968.9  323.33  4979.5  320.96  4985.3  317.43    4991  318.61  4998.7   315.2
  5001.5   314.7  5004.7   315.2  5029.4  318.39  5045.8   317.6  5135.3  321.39
  5161.8  323.73  5178.2  327.14  5194.1  327.56  5414.9  328.02  5623.1  327.65
  5999.5  330.43    6038  329.81  6065.7  327.03  6097.4  329.57  6161.4  329.28
#Mann= 7 ,-1 , 0
  3852.6     .05       0  4777.3      .1       0  4915.6     .12       0
  4998.7     .07       0  5004.7     .12       0  5135.3     .16       0
  5414.9      .1       0
Bank Sta=4991,5029.4
XS Rating Curve= 0 ,0
Exp/Cntr=0.3,0.1

Type RM Length L Ch R = 1 ,55037   ,397,397,397
BEGIN DESCRIPTION:
Mapping XS b869847f
END DESCRIPTION:
XS GIS Cut Line= 2
      3564543.56     10284087.54      3565293.55     10282330.62
#Sta/Elev= 30
  4454.4  331.04  4602.2  330.51  4924.2   326.9  4951.5  326.23  4969.6   324.1
  4982.7  316.62  4993.2  314.59  4995.7  313.18  4998.4  312.68  5001.7  313.18
  5020.8  315.16  5027.7  316.77  5045.9  317.54  5051.3  318.93  5069.5   319.3
    5104  322.85  5145.8  323.81  5303.7  325.24  5356.4  322.44  5398.5  322.69
  5432.6   324.6  5479.9  324.23  5561.6  326.42  5585.2  328.08  5614.2  326.95
    5685  326.85  5852.6  328.85    5938     328  6095.4  332.34  6364.7  336.28
#Mann= 6 ,-1 , 0
  4454.4     .05       0  4924.2     .16       0  4995.7     .07       0
  5001.7     .16       0  5398.5      .1       0    5938     .05       0
Bank Sta=4969.6,5145.8
XS Rating Curve= 0 ,0
Exp/Cntr=0.3,0.1

Type RM Length L Ch R = 1 ,54640   ,372,372,372
BEGIN DESCRIPTION:
Mapping XS 91f06aed
END DESCRIPTION:
XS GIS Cut Line= 2
      3564967.18     10284045.85      3565460.14     10282386.42
#Sta/Elev= 30
  4473.7  336.02  4707.6  331.35  4866.5  326.29  4891.8  325.87  4930.9  322.78
  4947.5  317.48    4958  315.98  4978.8  318.11  4989.3  314.47  4999.5  312.54
  5002.3  312.04  5005.5  312.54  5020.5  318.66  5030.5  320.41  5069.1  321.91
  5124.9  325.68  5218.8  326.75  5229.2  329.15  5239.6  329.93  5271.6  326.97
  5341.6  326.83  5372.9  326.89  5474.2  326.88  5510.9  329.01  5575.5  326.71
  5604.7   326.3  5761.2  329.69  6042.9  338.71  6160.9  341.05  6204.8  340.72
#Mann= 11 ,-1 , 0
  4473.7     .05       0  4866.5     .16       0  4891.8     .12       0
  4999.5     .07       0  5005.5     .12       0  5069.1      .1       0
  5271.6     .07       0  5341.6      .1       0  5372.9     .05       0
  5474.2      .1       0  5575.5     .05       0
Bank Sta=4978.8,5030.5
XS Rating Curve= 0 ,0
Exp/Cntr=0.3,0.1

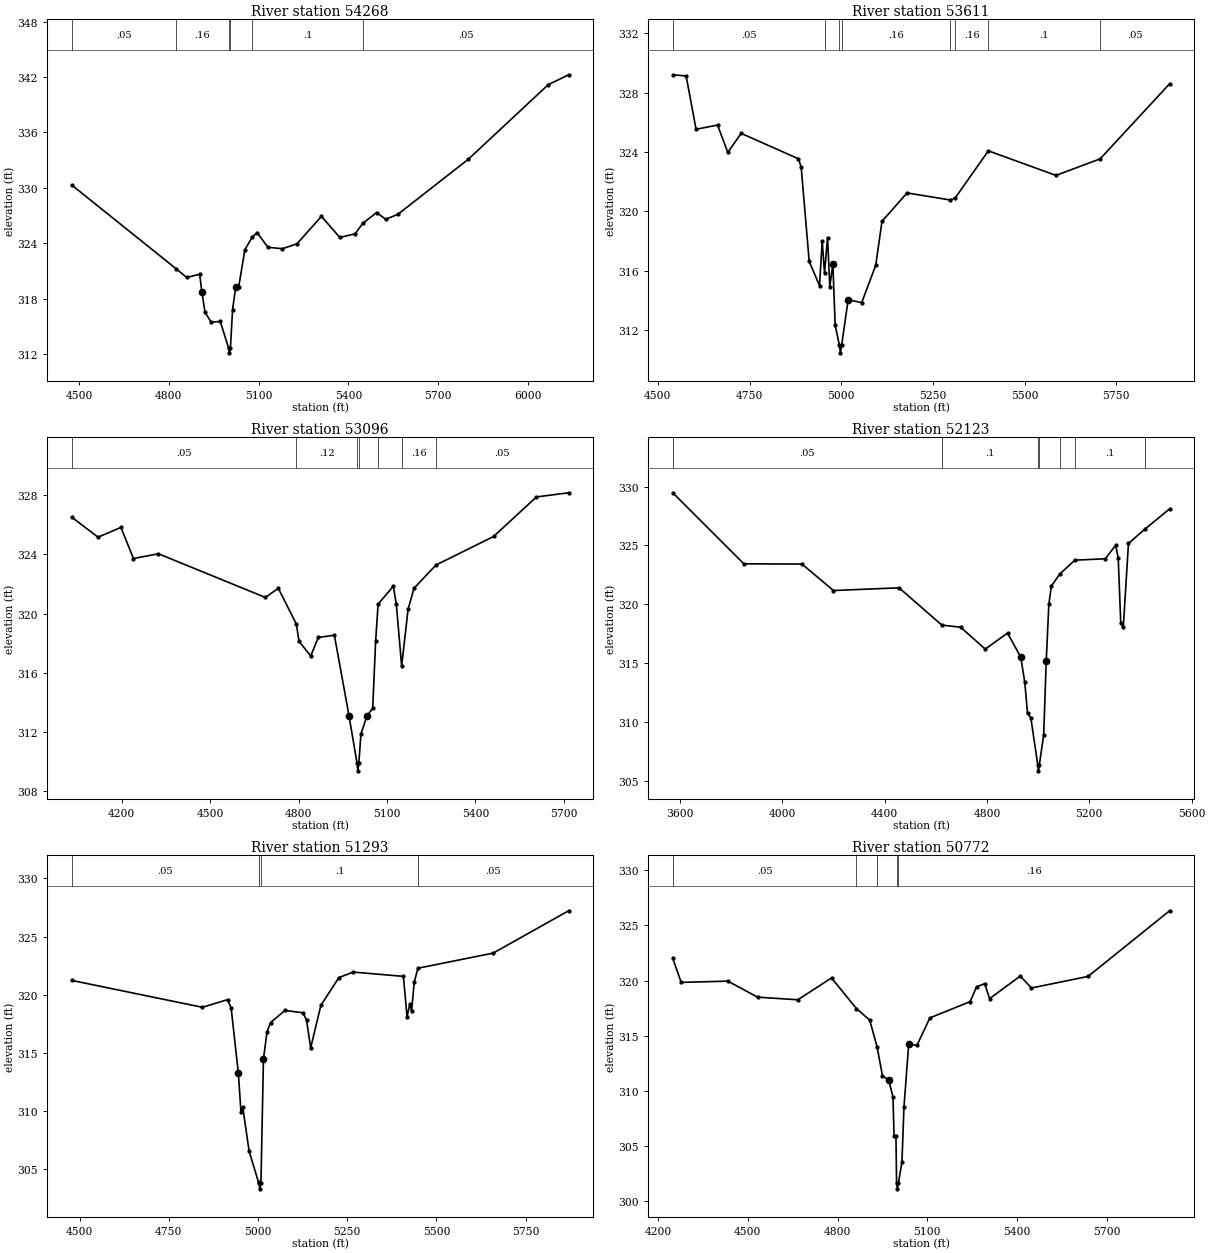
Type RM Length L Ch R = 1 ,54268   ,657,657,657
BEGIN DESCRIPTION:
SAND CREEK 83.0
END DESCRIPTION:
XS GIS Cut Line= 3
       3565192.1     10283991.65      3565392.81     10283816.02
      3565695.07     10282454.77
#Sta/Elev= 30
  4475.5  330.31  4823.9  321.27  4859.4  320.32  4902.9  320.67  4910.6  318.71
  4920.8  316.56  4941.3  315.49    4972  315.56  4999.8  312.67  5002.5  312.17
  5005.8  312.67    5013  316.83  5023.3  319.24  5033.5   319.3    5054  323.31
  5078.1  324.65    5095  325.18  5130.9  323.59  5179.6  323.43  5228.3  323.96
  5310.1  326.93  5371.5  324.65  5422.8  325.04  5447.9  326.16  5494.5  327.34
  5525.2  326.61  5566.2  327.16  5801.8  333.12  6068.1  341.16  6136.6  342.24
#Mann= 6 ,-1 , 0
  4475.5     .05       0  4823.9     .16       0  4999.8     .07       0
  5005.8     .16       0  5078.1      .1       0  5447.9     .05       0
Bank Sta=4910.6,5023.3
XS Rating Curve= 0 ,0
Exp/Cntr=0.3,0.1

Type RM Length L Ch R = 1 ,53611   ,515,515,515
BEGIN DESCRIPTION:
SAND CREEK 82.0
END DESCRIPTION:
XS GIS Cut Line= 3
      3565392.12     10284241.63      3565792.11     10283941.64
      3566092.11     10283141.62
#Sta/Elev= 30
  4540.7  329.21  4577.1  329.13  4604.2  325.53  4662.6  325.82  4690.7  323.97
  4727.1  325.26  4883.4  323.54  4890.7  322.98  4912.6  316.62  4940.7  314.98
    4948  317.98  4954.4  315.84  4962.6  318.23  4968.8  314.91  4977.1  316.46
  4983.4  312.31    4995  310.95  4997.7  310.45    5001  310.95  5018.8  314.03
  5055.8  313.84  5094.1  316.37    5111  319.32  5179.5  321.24  5297.7  320.76
  5310.6   320.9  5401.1  324.08  5585.4  322.42  5705.9  323.54  5895.1   328.6
#Mann= 8 ,-1 , 0
  4540.7     .05       0  4954.4     .16       0    4995     .07       0
    5001     .16       0  5297.7      .1       0  5310.6     .16       0
  5401.1      .1       0  5705.9     .05       0
Bank Sta=4977.1,5018.8
XS Rating Curve= 0 ,0
Exp/Cntr=0.3,0.1

Type RM Length L Ch R = 1 ,53096   ,973,973,973
BEGIN DESCRIPTION:
SAND CREEK 81.0
END DESCRIPTION:
XS GIS Cut Line= 3
      3565712.99     10284558.22      3566179.87     10284093.49
      3566221.53     10283067.48
#Sta/Elev= 30
  4030.5  326.51  4119.4  325.16  4197.2  325.82  4239.6  323.72  4324.4  324.04
  4687.3  321.09  4731.1  321.71  4792.6  319.28  4801.2  318.13  4841.2  317.14
  4866.9  318.39  4921.3  318.54  4971.3  313.07  4998.3  309.88  5001.1  309.38
  5004.3  309.88  5011.4  311.86  5031.4  313.07  5051.4  313.61  5061.4  318.16
  5069.7  320.64  5121.4  321.85  5131.5  320.63  5149.6  316.47  5171.5   320.3
  5191.5  321.71    5266  323.28  5461.7  325.21  5606.9  327.88  5716.1  328.16
#Mann= 7 ,-1 , 0
  4030.5     .05       0  4792.6     .12       0  4998.3     .07       0
  5004.3     .12       0  5069.7      .1       0  5149.6     .16       0
    5266     .05       0
Bank Sta=4971.3,5031.4
XS Rating Curve= 0 ,0
Exp/Cntr=0.3,0.1

Type RM Length L Ch R = 1 ,52123   ,830,830,830
BEGIN DESCRIPTION:
SAND CREEK 79.0
END DESCRIPTION:
XS GIS Cut Line= 3
      3566042.12     10284941.62      3566742.11     10283741.64
      3566792.11     10283191.63
#Sta/Elev= 30
  3572.2  329.47    3850  323.43    4077  323.41  4200.2  321.16  4456.6  321.39
  4623.7  318.22  4697.2  318.04  4793.1  316.18  4880.4  317.54  4932.1   315.5
  4947.8  313.36  4958.5  310.74  4971.5  310.34  4998.6  306.33  5001.3  305.83
  5004.6  306.33  5021.7  308.88  5031.7  315.17  5041.8  319.98  5051.8  321.54
  5084.5  322.56  5143.4  323.74  5262.7  323.86  5302.8  325.01  5312.9  323.95
  5322.9   318.4  5332.9  318.06    5353  325.16  5417.9  326.39  5513.7   328.1
#Mann= 7 ,-1 , 0
  3572.2     .05       0  4623.7      .1       0  4998.6     .07       0
  5004.6      .1       0  5084.5     .05       0  5143.4      .1       0
  5417.9     .05       0
Bank Sta=4932.1,5031.7
XS Rating Curve= 0 ,0
Exp/Cntr=0.3,0.1

Type RM Length L Ch R = 1 ,51293   ,521,521,521
BEGIN DESCRIPTION:
SAND CREEK 78.0
END DESCRIPTION:
XS GIS Cut Line= 3
      3566789.24     10284504.95      3567049.66     10284260.16
      3566940.41     10283231.45
#Sta/Elev= 30
  4478.4  321.23  4844.4  318.92  4914.8  319.58  4924.8  318.85  4944.9  313.29
  4952.3  309.93  4957.3  310.35  4975.1  306.56  5001.5  303.87  5002.3  303.81
    5005  303.31  5008.3  303.81  5015.3   314.5  5025.4  316.82  5035.4  317.61
  5075.7  318.65  5125.9  318.45    5136  317.83  5147.6  315.43  5176.2  319.09
  5226.5  321.47  5266.7  321.95  5407.5  321.58  5417.6  318.11  5425.4  319.21
  5430.4  318.59  5437.7  321.08  5448.1  322.28  5658.9  323.58  5870.3  327.22
#Mann= 5 ,-1 , 0
  4478.4     .05       0  5001.5      .1       0  5002.3    .035       0
  5008.3      .1       0  5448.1     .05       0
Bank Sta=4944.9,5015.3
XS Rating Curve= 0 ,0
Exp/Cntr=0.3,0.1

Type RM Length L Ch R = 1 ,50772   ,709,709,709
BEGIN DESCRIPTION:
SAND CREEK 77.0
END DESCRIPTION:
XS GIS Cut Line= 3
      3566942.08     10284641.67      3567492.11     10284141.64
      3568292.09     10283691.65
#Sta/Elev= 30
  4249.1  322.01  4277.2  319.84  4433.3  319.95  4532.6   318.5  4667.1  318.26
  4779.9  320.24  4862.9  317.47  4907.6  316.42  4932.2  313.99  4950.2  311.38
  4971.2  310.98  4985.3  309.45  4989.1  305.91  4995.3  305.91  4997.4  301.62
  5000.2  301.12  5003.4  301.62  5015.4  303.55  5022.1  308.53    5038  314.25
  5065.4  314.12  5108.8  316.62  5243.3  318.09  5264.9  319.44  5292.3  319.72
  5308.3  318.36  5410.9  320.41  5448.5  319.33  5637.8  320.38  5910.3  326.33
#Mann= 5 ,-1 , 0
  4249.1     .05       0  4862.9      .1       0  4932.2     .16       0
  4997.4     .07       0  5003.4     .16       0
Bank Sta=4971.2,5038
XS Rating Curve= 0 ,0
Exp/Cntr=0.3,0.1

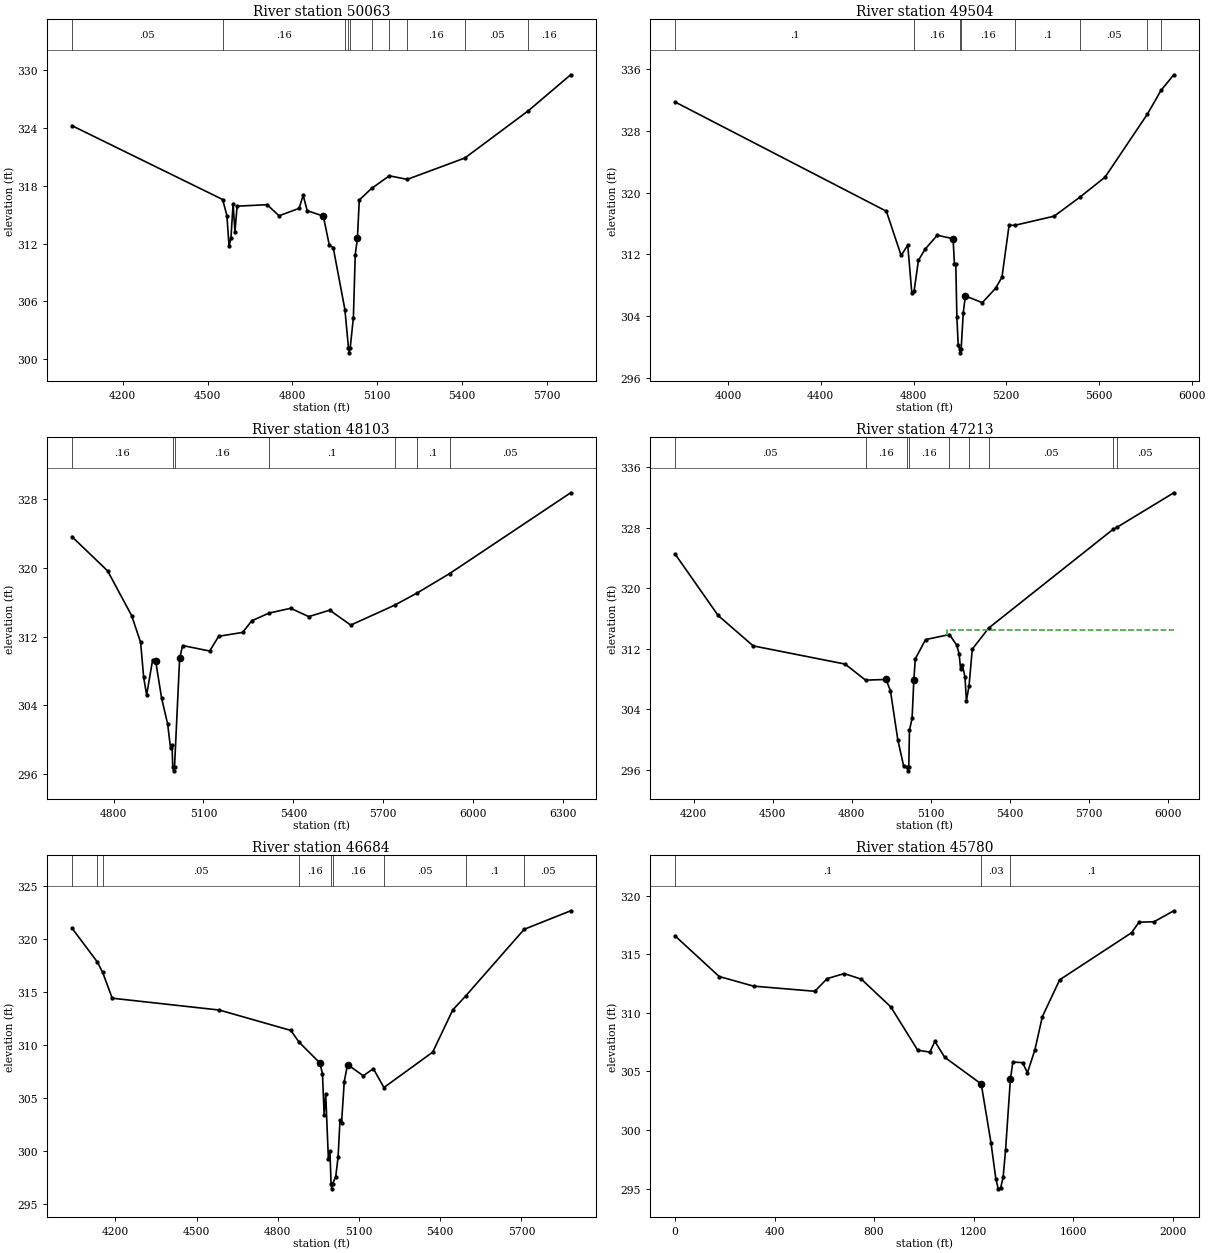
Type RM Length L Ch R = 1 ,50063   ,559,559,559
BEGIN DESCRIPTION:
SAND CREEK 76.0
END DESCRIPTION:
XS GIS Cut Line= 2
      3567299.66     10285072.66      3568460.17     10283745.62
#Sta/Elev= 30
  4020.4  324.24  4553.2  316.57  4568.2   314.9  4575.8   311.7  4582.5  312.56
  4590.1  316.12  4596.7  313.24  4604.3  315.88  4710.6  316.03  4752.4  314.88
  4823.5  315.65  4837.8  317.01    4852  315.41    4909  314.85  4929.8  311.88
  4944.1  311.56  4985.3  305.14    4998  301.15  5000.8  300.65    5004  301.15
  5015.3   304.3  5021.9  310.84  5029.5  312.53  5036.2  316.52  5079.5  317.72
  5142.4  319.03  5205.7  318.66  5409.4  320.88  5633.1  325.77  5783.3  329.52
#Mann= 10 ,-1 , 0
  4020.4     .05       0  4553.2     .16       0  4985.3      .1       0
    4998     .07       0    5004      .1       0  5079.5     .16       0
  5142.4      .1       0  5205.7     .16       0  5409.4     .05       0
  5633.1     .16       0
Bank Sta=4909,5029.5
XS Rating Curve= 0 ,0
Exp/Cntr=0.3,0.1

Type RM Length L Ch R = 1 ,49504   ,1401,1401,1401
BEGIN DESCRIPTION:
SAND CREEK 74.0
END DESCRIPTION:
XS GIS Cut Line= 3
      3567742.12     10285891.61      3568242.11     10284791.64
      3568742.12     10283991.62
#Sta/Elev= 30
  3771.2  331.73  4682.9  317.58  4746.6  311.85  4775.2  313.18  4792.7  306.99
  4802.7  307.26  4821.3  311.22  4849.9  312.66  4902.6  314.47  4970.7  314.02
  4976.7  310.71  4982.4  310.71  4987.1  303.83    4993  300.22  4999.5  299.74
  5002.2  299.24  5005.5  299.74  5014.8  304.46  5023.7  306.61  5096.8  305.74
  5154.6  307.62  5181.7  309.05  5212.4  315.78  5236.2  315.75  5406.9  316.94
  5518.7  319.42  5626.3  321.99  5808.9  330.15  5868.2  333.25  5922.9  335.25
#Mann= 8 ,-1 , 0
  3771.2      .1       0  4802.7     .16       0  4999.5     .07       0
  5005.5     .16       0  5236.2      .1       0  5518.7     .05       0
  5808.9     .16       0  5868.2     .05       0
Bank Sta=4970.7,5023.7
XS Rating Curve= 0 ,0
Exp/Cntr=0.3,0.1

Type RM Length L Ch R = 1 ,48103   ,890,890,890
BEGIN DESCRIPTION:
SAND CREEK 71.0
END DESCRIPTION:
XS GIS Cut Line= 2
      3569106.95     10285770.54      3569007.99     10284109.09
#Sta/Elev= 30
    4661  323.65  4780.1  319.66  4860.3  314.45  4890.3  311.32  4900.3   307.3
  4910.3  305.19  4930.4  309.29  4940.4  309.17  4960.4  304.81  4980.5  301.81
  4990.1  299.02  4995.1  299.37  4997.5  296.86  5000.3  296.36  5003.5  296.86
  5020.5  309.48  5030.6  310.96  5120.7  310.32  5150.8  312.04  5230.9  312.49
    5261  313.84  5318.5  314.74  5391.2   315.3  5451.3  314.33  5521.4  315.08
  5591.5  313.34  5737.7  315.66  5811.5  317.05  5921.2  319.34  6325.4  328.76
#Mann= 7 ,-1 , 0
    4661     .16       0  4997.5     .07       0  5003.5     .16       0
  5318.5      .1       0  5737.7     .05       0  5811.5      .1       0
  5921.2     .05       0
Bank Sta=4940.4,5020.5
XS Rating Curve= 0 ,0
Exp/Cntr=0.3,0.1

Type RM Length L Ch R = 1 ,47213   ,529,529,529
BEGIN DESCRIPTION:
SAND CREEK 70.0
END DESCRIPTION:
XS GIS Cut Line= 2
      3569242.13      10285741.6      3570107.91     10284058.53
#Sta/Elev= 30
  4129.2  324.52  4292.7  316.39  4425.7  312.37  4774.9  309.96  4852.1  307.84
  4930.1  307.93  4946.7  306.42  4974.5  299.97  4996.7  296.49  5010.2  296.35
    5013  295.85  5016.2  296.35  5018.8  301.21  5028.8  302.79  5035.4  307.85
    5041  310.66  5079.8   313.2  5170.5  313.87  5197.5   312.5  5207.2  311.35
  5212.8  309.33    5220   309.8  5229.4  308.29    5235  305.09    5245  307.12
  5257.2  311.94  5319.6  314.73    5793  327.82  5805.7  328.03  6021.9  332.61
#Mann= 9 ,-1 , 0
  4129.2     .05       0  4852.1     .16       0  5010.2     .07       0
  5016.2     .16       0  5170.5     .05       0    5245     .16       0
  5319.6     .05       0    5793      .1       0  5805.7     .05       0
#XS Ineff= 2 , 0
                         5162.59          314.42
Permanent Ineff=
       F       F
Bank Sta=4930.1,5035.4
XS Rating Curve= 0 ,0
Exp/Cntr=0.3,0.1

Type RM Length L Ch R = 1 ,46684   ,904,904,904
BEGIN DESCRIPTION:
Mapping XS 21f46875
END DESCRIPTION:
XS GIS Cut Line= 3
      3569491.95     10285792.07      3570051.83     10285245.21
      3570585.69     10284329.39
#Sta/Elev= 30
  4039.2     321  4133.4  317.79  4152.9  316.81  4188.1  314.38  4584.2  313.26
  4847.8  311.34  4878.9  310.22  4955.3  308.27  4964.9  307.25    4971   303.4
  4976.8  305.38  4986.7  299.25  4992.5  299.97  4996.6  296.89  4999.3  296.39
  5002.6  296.89    5014  297.55  5022.7  299.42  5029.7  302.91  5035.5  302.64
  5045.4  306.51  5057.5  308.12  5115.7  307.06  5152.9  307.73    5192  305.95
  5372.1  309.29  5446.5  313.28  5495.1  314.62    5710  320.88  5881.9  322.63
#Mann= 9 ,-1 , 0
  4039.2     .05       0  4133.4      .1       0  4152.9     .05       0
  4878.9     .16       0  4996.6     .07       0  5002.6     .16       0
    5192     .05       0  5495.1      .1       0    5710     .05       0
Bank Sta=4955.3,5057.5
XS Rating Curve= 0 ,0
Exp/Cntr=0.3,0.1

Type RM Length L Ch R = 1 ,45780   ,88,88,88
XS GIS Cut Line= 5
     3570383.184    10286126.371     3570807.664     10285694.08
     3570799.851      10285144.6     3570961.221    10284960.033
      3570858.66    10284353.691
#Sta/Elev= 30
       0  316.57   177.5   313.1  315.56  312.28  562.09  311.84  611.38  312.92
   680.3  313.35  749.22  312.87  867.36  310.51  975.65  306.81 1024.88  306.65
 1044.57  307.57 1083.95  306.21 1231.01  303.93 1270.08  298.93 1289.62  295.85
 1299.39  294.98 1309.16  295.07 1318.93  295.95 1328.69  298.26 1348.23  304.32
    1358   305.8 1397.07  305.75 1416.81  304.89 1446.73  306.84 1476.64  309.67
 1546.45  312.82 1835.62  316.84 1865.54  317.74 1925.37  317.77 2005.14  318.71
#Mann= 3 , 0 , 0
       0      .1       0 1231.01     .03       0 1348.23      .1       0
Bank Sta=1231.01,1348.23
XS Rating Curve= 0 ,0
Exp/Cntr=0.3,0.1

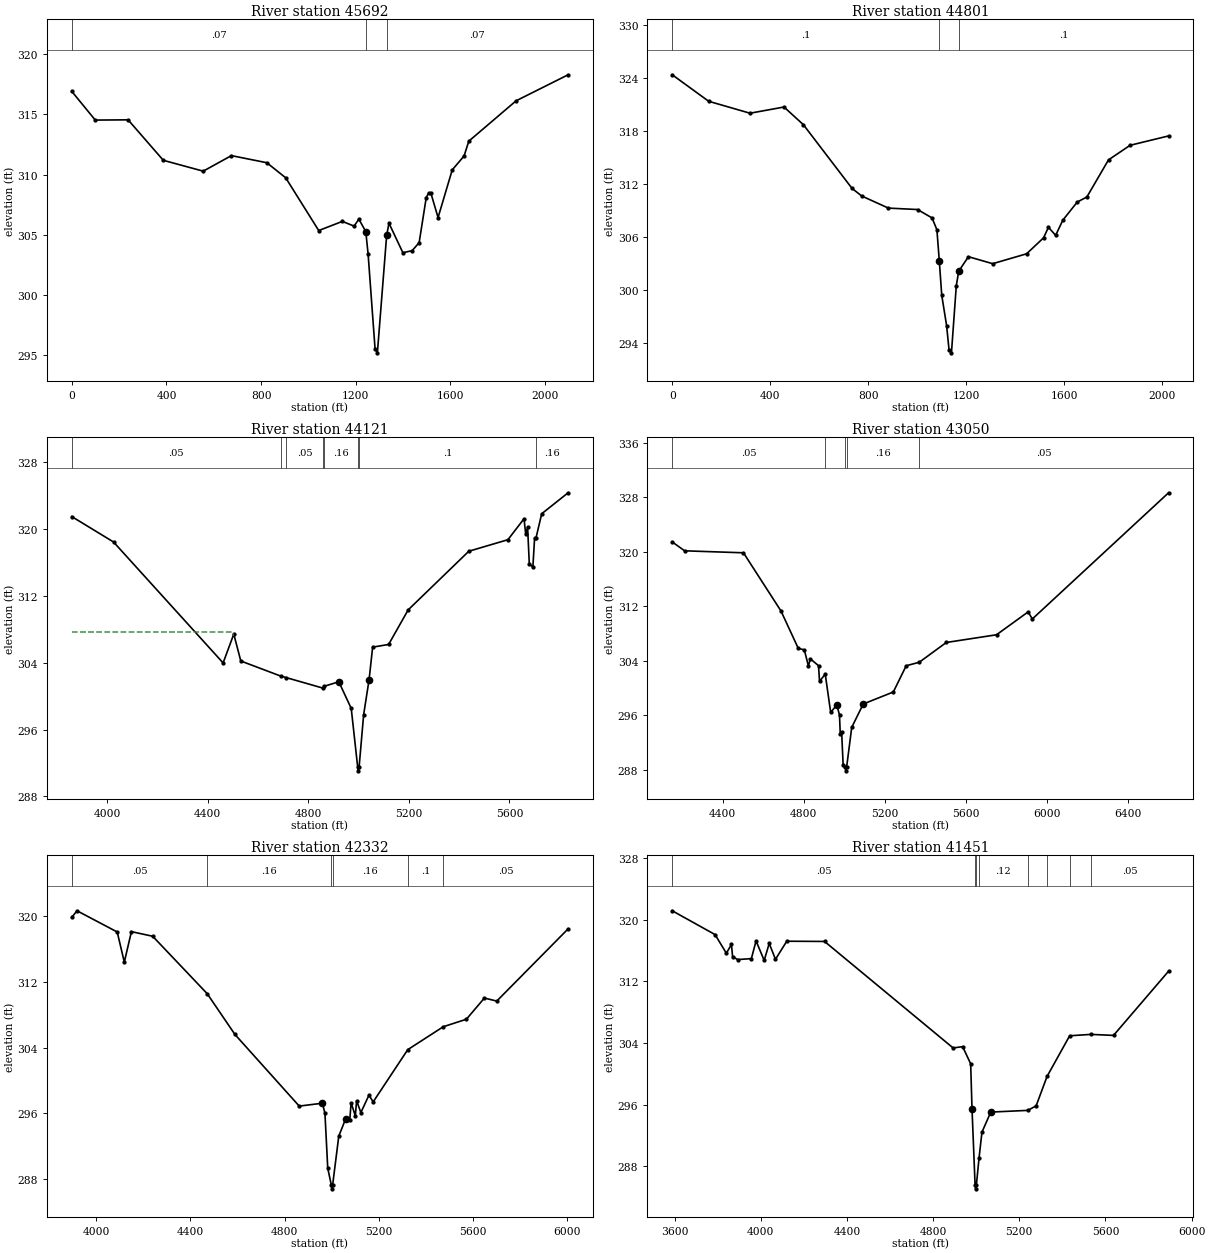
Type RM Length L Ch R = 1 ,45692   ,891,891,891
XS GIS Cut Line= 5
     3570431.362    10286184.097      3570882.75    10285743.125
     3570900.112    10285159.791      3571060.14    10284971.892
     3570880.795    10284354.993
#Sta/Elev= 30
       0   316.9   99.14  314.52  237.94  314.54  386.66  311.18   555.2  310.28
  674.45  311.57     824  310.98  903.77  309.73 1043.35  305.35 1143.06  306.11
 1192.91  305.72 1212.85   306.3 1242.22  305.26 1252.02  303.39 1281.39  295.53
 1291.19   295.2 1330.35  304.95 1340.15  305.96  1398.9  303.51 1438.07  303.68
 1467.64  304.35 1497.61  308.09 1507.61  308.47  1517.6  308.43 1547.57  306.43
 1607.51  310.39 1657.47  311.54 1677.45  312.77 1877.26  316.12 2097.06  318.28
#Mann= 3 , 0 , 0
       0     .07       0 1242.22     .05       0 1330.35     .07       0
Bank Sta=1242.22,1330.35
XS Rating Curve= 0 ,0
Exp/Cntr=0.3,0.1

Type RM Length L Ch R = 1 ,44801   ,680,680,680
BEGIN DESCRIPTION:
SAND CREEK 67.0
END DESCRIPTION:
XS GIS Cut Line= 4
      3572136.45     10285884.99      3571942.11     10285241.64
 3571280.700309310284693.6294186     3570918.556    10284356.295
#Sta/Elev= 30
       0  324.34  148.81  321.34  317.47  319.99  456.36  320.69  535.73  318.68
  734.01  311.48  773.61  310.62  882.51  309.25  1001.3  309.09  1060.7  308.14
  1080.5   306.8  1090.4  303.22  1100.3  299.38  1120.1  295.95    1130  293.23
  1139.9  292.87 1159.69  300.47 1169.59  302.11 1209.19  303.75 1308.19  302.96
 1446.78  304.08 1516.08  305.89 1535.88  307.08  1565.3  306.17 1594.72  307.89
 1653.57  309.94 1692.81  310.51 1781.08  314.71 1869.35  316.36 2026.28  317.42
#Mann= 3 , 0 , 0
       0      .1       0  1090.4     .07       0 1169.59      .1       0
Bank Sta=1090.4,1169.59
XS Rating Curve= 0 ,0
Exp/Cntr=0.3,0.1

Type RM Length L Ch R = 1 ,44121   ,1071,1071,1071
BEGIN DESCRIPTION:
Mapping XS 2ed67cab
END DESCRIPTION:
XS GIS Cut Line= 3
      3572309.45     10285282.55      3572246.95     10284827.71
      3571222.63     10283713.11
#Sta/Elev= 30
  3860.5  321.51  4026.3  318.47    4462  303.99  4504.4  307.44  4532.3  304.22
  4690.5  302.42  4711.9  302.24  4859.2  300.97  4862.1  301.18    4922  301.73
  4971.3  298.54  4996.7  291.57  4999.4  291.07  5002.7  291.57  5020.6  297.79
  5042.2  301.97  5056.4  305.88  5119.9   306.2  5197.6  310.34  5438.6  317.36
    5594  318.74  5658.1  321.25  5664.9  319.39  5672.3  320.24  5679.1  315.86
  5693.3  315.46  5700.1  318.91  5705.4  318.91  5728.4  321.85  5833.4  324.36
#Mann= 8 ,-1 , 0
  3860.5     .05       0  4690.5     .16       0  4711.9     .05       0
  4859.2     .12       0  4862.1     .16       0  4996.7     .07       0
  5002.7      .1       0  5705.4     .16       0
#XS Ineff= 2 , 0
         4501.99   307.7
Permanent Ineff=
       F       F
Bank Sta=4922,5042.2
XS Rating Curve= 0 ,0
Exp/Cntr=0.3,0.1

Type RM Length L Ch R = 1 ,43050   ,718,718,718
BEGIN DESCRIPTION:
SAND CREEK 64.0
END DESCRIPTION:
XS GIS Cut Line= 3
      3572698.97     10285412.79      3572742.11     10284591.64
      3571642.08     10283391.62
#Sta/Elev= 30
    4151  321.42  4212.2  320.12  4502.6  319.83  4687.6  311.31    4773  305.83
    4803  305.59  4823.1  303.26  4833.1  304.27  4873.1  303.28  4878.1  300.98
  4906.3  302.04  4933.2  296.42  4963.3  297.53  4976.7  296.04  4980.4  293.27
  4987.2  293.61  4994.6  288.75  5005.7  288.36  5008.5  287.86  5011.7  288.36
  5037.1  294.23  5093.8  297.66  5242.4  299.42    5306  303.27  5370.4  303.78
  5503.9  306.68  5751.8  307.81  5907.8  311.16  5928.7  310.13  6601.2  328.63
#Mann= 5 ,-1 , 0
    4151     .05       0  4906.3     .16       0  5005.7     .07       0
  5011.7     .16       0  5370.4     .05       0
Bank Sta=4963.3,5093.8
XS Rating Curve= 0 ,0
Exp/Cntr=0.3,0.1

Type RM Length L Ch R = 1 ,42332   ,881,881,881
BEGIN DESCRIPTION:
SAND CREEK 63.0
END DESCRIPTION:
XS GIS Cut Line= 3
      3572844.79     10285433.69      3572892.11     10284841.64
      3573496.87     10283456.11
#Sta/Elev= 30
  3897.1  319.87  3919.2  320.67  4089.8  318.09  4119.9  314.42    4150  318.13
  4240.2  317.57  4471.6  310.58  4589.2  305.62    4862   296.9  4960.2  297.25
  4971.1  296.02    4983  289.34  4997.9  287.33  5000.7  286.83  5003.9  287.33
  5029.8  293.24  5058.7  295.33  5076.6  295.25  5082.1   297.3    5100  295.72
  5105.5  297.55  5123.5  296.11  5157.8  298.23  5175.7  297.41  5322.5  303.77
  5473.2  306.56  5571.2  307.47  5647.6  310.05  5700.1  309.68  6002.8  318.47
#Mann= 6 ,-1 , 0
  3897.1     .05       0  4471.6     .16       0  4997.9     .07       0
  5003.9     .16       0  5322.5      .1       0  5473.2     .05       0
Bank Sta=4960.2,5058.7
XS Rating Curve= 0 ,0
Exp/Cntr=0.3,0.1

Type RM Length L Ch R = 1 ,41451   ,1404,1404,1404
BEGIN DESCRIPTION:
SAND CREEK 60.0
END DESCRIPTION:
XS GIS Cut Line= 3
      3573178.12     10285808.69       3573907.3     10284121.15
      3573914.24     10283656.24
#Sta/Elev= 30
  3589.5  321.17  3788.2  318.08  3840.7  315.66  3864.2   316.8  3869.6  315.21
  3893.1  314.84  3956.7  314.96  3978.5  317.26  4016.1  314.73  4039.6  316.93
  4068.5  314.87  4120.9  317.22  4296.3  317.19    4893  303.37  4937.1  303.54
  4974.4  301.32  4980.7  295.44  4994.9  285.59  4997.6  285.09  5000.9  285.59
  5013.3  289.09  5026.8  292.45  5067.8  295.05  5239.5  295.27  5278.2  295.86
    5329  299.68  5433.8  304.95  5531.9  305.13  5637.4     305  5892.8  313.33
#Mann= 8 ,-1 , 0
  3589.5     .05       0  4994.9    .035       0  5000.9     .05       0
  5013.3     .12       0  5239.5     .16       0    5329     .12       0
  5433.8     .16       0  5531.9     .05       0
Bank Sta=4980.7,5067.8
XS Rating Curve= 0 ,0
Exp/Cntr=0.3,0.1