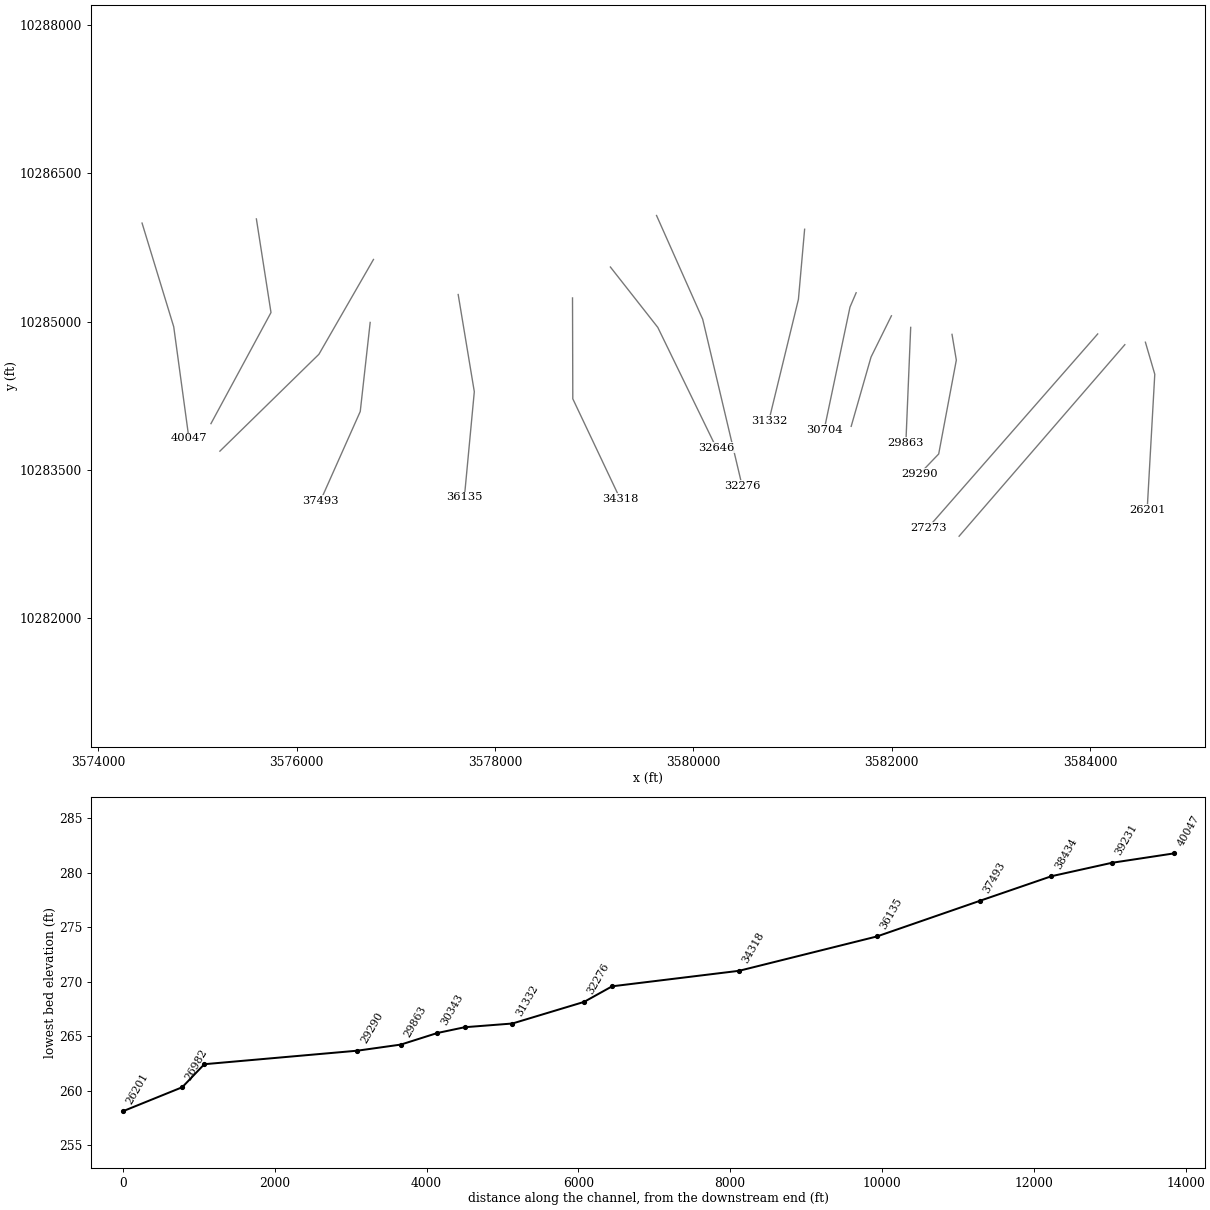
HEC-RAS study SAND CREEK.prj: SAND CREEK Base Level Engineering

--- SAND CREEK.g01 (geometry) --- (continued)

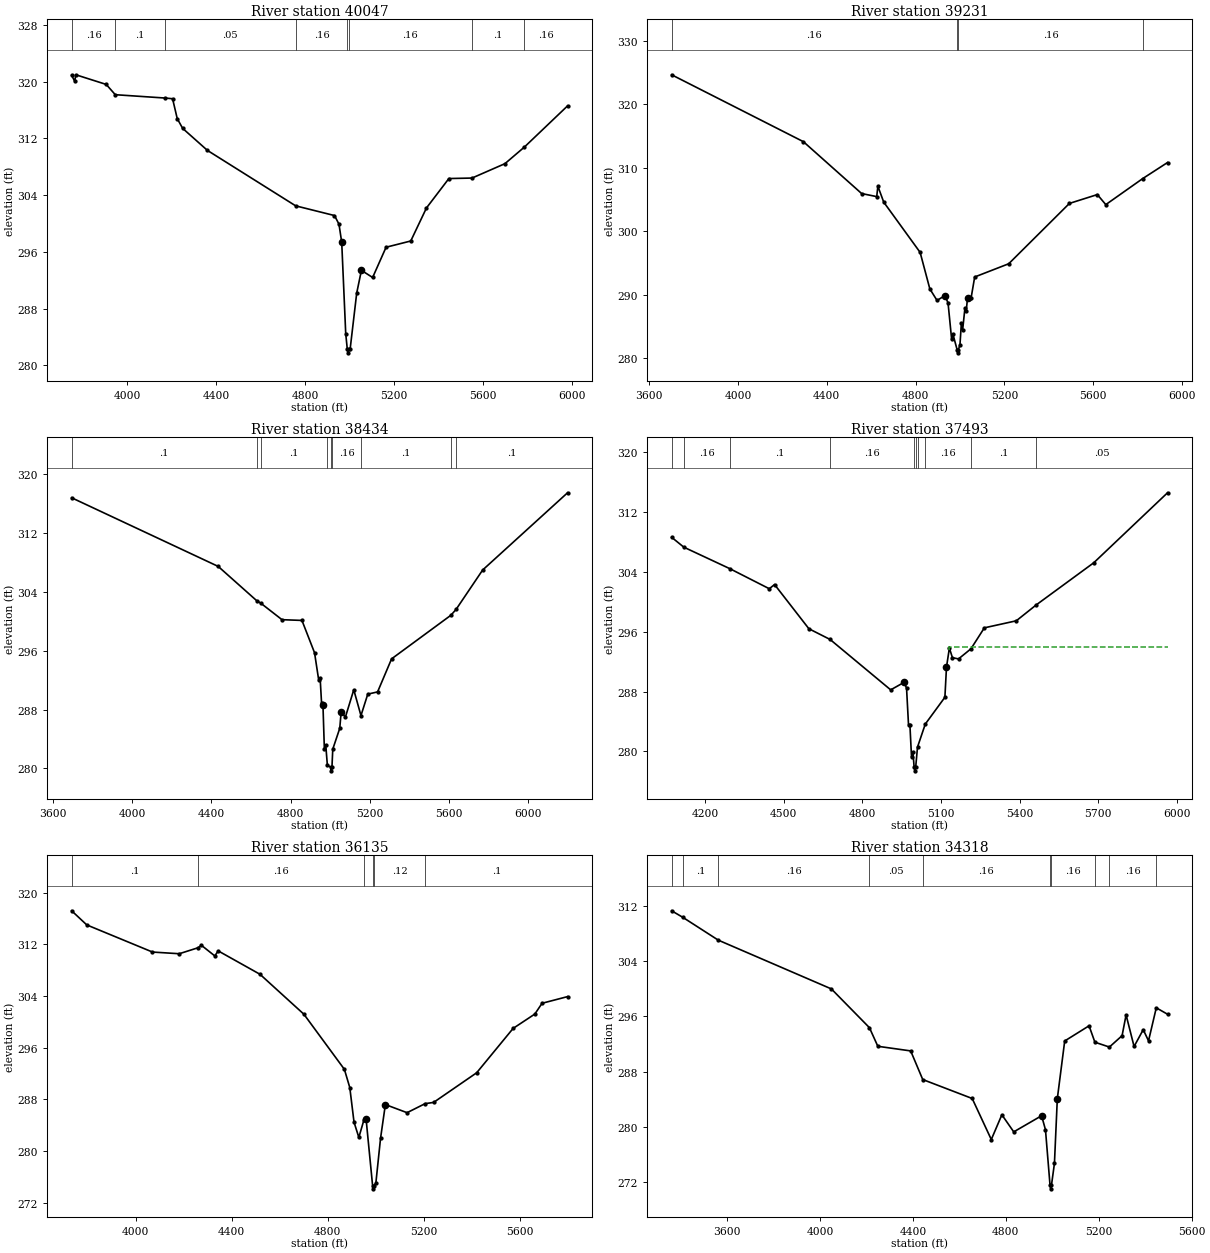
Type RM Length L Ch R = 1 ,40047   ,816,816,816
BEGIN DESCRIPTION:
SAND CREEK 58.0
END DESCRIPTION:
XS GIS Cut Line= 3
      3574442.03     10285996.11      3574761.46     10284947.54
      3574914.25     10283822.51
#Sta/Elev= 30
  3749.1   320.9  3762.8  320.07    3768  320.98  3904.6  319.62  3945.4  318.17
    4169   317.7  4203.3   317.6  4224.2   314.8  4248.6  313.42  4360.1  310.31
  4757.1  302.49  4931.9  301.12  4952.1   299.9  4964.4  297.34  4982.4  284.47
  4989.5  282.25  4992.2  281.75  4995.5  282.25  5002.6  282.36  5031.8  290.17
    5053  293.39  5103.5  292.38    5164  296.65  5275.1  297.53  5345.7  302.19
  5446.6  306.34  5550.7  306.41  5698.9  308.44  5786.7  310.79  5980.6  316.59
#Mann= 8 ,-1 , 0
  3749.1     .16       0  3945.4      .1       0    4169     .05       0
  4757.1     .16       0  4989.5     .07       0  4995.5     .16       0
  5550.7      .1       0  5786.7     .16       0
Bank Sta=4964.4,5053
XS Rating Curve= 0 ,0
Exp/Cntr=0.3,0.1

Type RM Length L Ch R = 1 ,39231   ,797,797,797
BEGIN DESCRIPTION:
SAND CREEK 56.0
END DESCRIPTION:
XS GIS Cut Line= 3
      3575594.79     10286037.83      3575742.11     10285091.64
      3575136.76     10283968.93
#Sta/Elev= 30
  3701.6  324.62  4294.9   314.1  4557.3  305.94  4625.2  305.46  4630.3   307.1
  4656.7  304.59  4820.6  296.69  4864.4  290.94  4896.8  289.13  4931.9  289.89
  4946.3  288.75  4962.5  283.02  4968.2  283.85  4987.1  281.39  4989.8  280.89
  4993.1  281.39    5000  282.16  5006.3  285.52    5012  284.48  5022.5  287.98
  5028.2  287.47  5034.1  289.54  5050.1  289.51  5066.3  292.82  5219.6   294.9
  5492.9  304.39  5618.6  305.78  5656.7   304.2  5822.7  308.29  5934.7  310.82
#Mann= 4 ,-1 , 0
  3701.6     .16       0  4987.1     .07       0  4993.1     .16       0
  5822.7      .1       0
Bank Sta=4931.9,5034.1
XS Rating Curve= 0 ,0
Exp/Cntr=0.3,0.1

Type RM Length L Ch R = 1 ,38434   ,941,941,941
BEGIN DESCRIPTION:
SAND CREEK 54.0
END DESCRIPTION:
XS GIS Cut Line= 3
      3576775.37     10285628.13      3576225.32     10284670.01
      3575226.95     10283690.81
#Sta/Elev= 30
  3695.1  316.82  4434.8  307.48  4628.6  302.83  4651.5  302.44  4756.9  300.23
  4857.6  300.13  4921.2  295.73  4942.5  291.96  4949.5  292.25  4956.6  288.89
  4963.6  288.67  4970.8  282.61  4977.8  283.15    4986   280.4  5003.1  280.16
  5005.8  279.66  5009.1  280.16  5013.2  282.61  5048.5  285.45  5055.6  287.73
  5076.8  286.96  5119.2  290.69  5155.5  287.18  5189.9   290.1  5239.4   290.4
  5310.1   294.9  5609.3  300.83  5635.7  301.63  5769.8  306.99  6198.3   317.5
#Mann= 9 ,-1 , 0
  3695.1      .1       0  4628.6     .16       0  4651.5      .1       0
    4986     .16       0  5003.1     .07       0  5009.1     .16       0
  5155.5      .1       0  5609.3     .16       0  5635.7      .1       0
Bank Sta=4963.6,5055.6
XS Rating Curve= 0 ,0
Exp/Cntr=0.3,0.1

Type RM Length L Ch R = 1 ,37493   ,1358,1358,1358
BEGIN DESCRIPTION:
SAND CREEK 52.0
END DESCRIPTION:
XS GIS Cut Line= 3
      3576742.11     10284991.66      3576642.11     10284091.64
      3576242.12     10283191.68
#Sta/Elev= 30
  4073.5  308.59  4119.9  307.27  4295.3   304.4  4445.8  301.72  4465.9  302.28
  4596.7  296.38  4677.5  294.95  4908.6  288.22  4958.9  289.21    4969  288.48
  4976.5  283.56  4981.8  283.56    4988  279.25  4993.4  279.88  4997.9  277.91
  5000.7  277.41  5003.9  277.91  5010.8  280.58  5040.4  283.65  5115.2  287.23
  5121.3  291.26  5132.3   293.8  5143.9  292.52  5167.1  292.35  5214.5   293.7
  5265.6   296.5  5387.4  297.44  5463.7  299.57  5682.8  305.19  5963.9  314.53
#Mann= 10 ,-1 , 0
  4073.5      .1       0  4119.9     .16       0  4295.3      .1       0
  4677.5     .16       0  4997.9     .07       0  5003.9     .16       0
  5010.8      .1       0  5040.4     .16       0  5214.5      .1       0
  5463.7     .05       0
#XS Ineff= 2 , 0
                         5131.32          293.92
Permanent Ineff=
       F       F
Bank Sta=4958.9,5121.3
XS Rating Curve= 0 ,0
Exp/Cntr=0.3,0.1

Type RM Length L Ch R = 1 ,36135   ,1817,1817,1817
BEGIN DESCRIPTION:
SAND CREEK 49.0
END DESCRIPTION:
XS GIS Cut Line= 3
      3577629.52     10285273.92      3577792.11     10284291.64
      3577692.08     10283225.97
#Sta/Elev= 30
  3733.1  317.19  3796.2     315  4069.9   310.8  4181.4  310.54  4260.1  311.47
  4273.6  311.85  4329.5   310.2  4343.6  310.98  4517.7  307.36  4700.8  301.17
  4869.4  292.64  4891.9  289.82  4909.5  284.47  4929.6   282.1  4950.5  284.78
  4959.8  284.95  4986.9  274.64  4989.6  274.14  4992.9  274.64  5000.6  275.06
    5020  281.96  5040.1  287.19  5130.5  285.93  5205.7  287.33    5241  287.52
  5420.5  292.11  5572.4  298.98  5662.8   301.2    5693  302.87  5799.1   303.9
#Mann= 6 ,-1 , 0
  3733.1      .1       0  4260.1     .16       0  4950.5     .12       0
  4986.9     .07       0  4992.9     .12       0  5205.7      .1       0
Bank Sta=4959.8,5040.1
XS Rating Curve= 0 ,0
Exp/Cntr=0.3,0.1

Type RM Length L Ch R = 1 ,34318   ,1672,1672,1672
BEGIN DESCRIPTION:
SAND CREEK 46.0
END DESCRIPTION:
XS GIS Cut Line= 3
       3578782.3     10285239.21      3578785.21     10284219.67
      3579261.46     10283211.43
#Sta/Elev= 30
  3361.5  311.31  3409.6  310.36  3562.4  307.05  4049.1  299.98  4212.9  294.36
  4249.1  291.66  4390.5  290.99  4442.4  286.84  4655.3  284.09  4737.5  278.14
    4783  281.73  4834.1  279.25    4954  281.59  4970.7  279.56  4990.4  271.49
  4993.2  270.99  4996.4  271.49  5009.3  274.67  5021.7  284.06  5053.5  292.43
  5158.3  294.63  5183.5  292.25  5245.9  291.55  5300.5   293.2  5317.7  296.21
  5352.1  291.63  5391.5  294.07  5414.3  292.45  5447.7  297.24  5496.1  296.31
#Mann= 10 ,-1 , 0
  3361.5     .05       0  3409.6      .1       0  3562.4     .16       0
  4212.9     .05       0  4442.4     .16       0  4990.4     .07       0
  4996.4     .16       0  5183.5     .05       0  5245.9     .16       0
  5447.7     .05       0
Bank Sta=4954,5021.7
XS Rating Curve= 0 ,0
Exp/Cntr=0.3,0.1

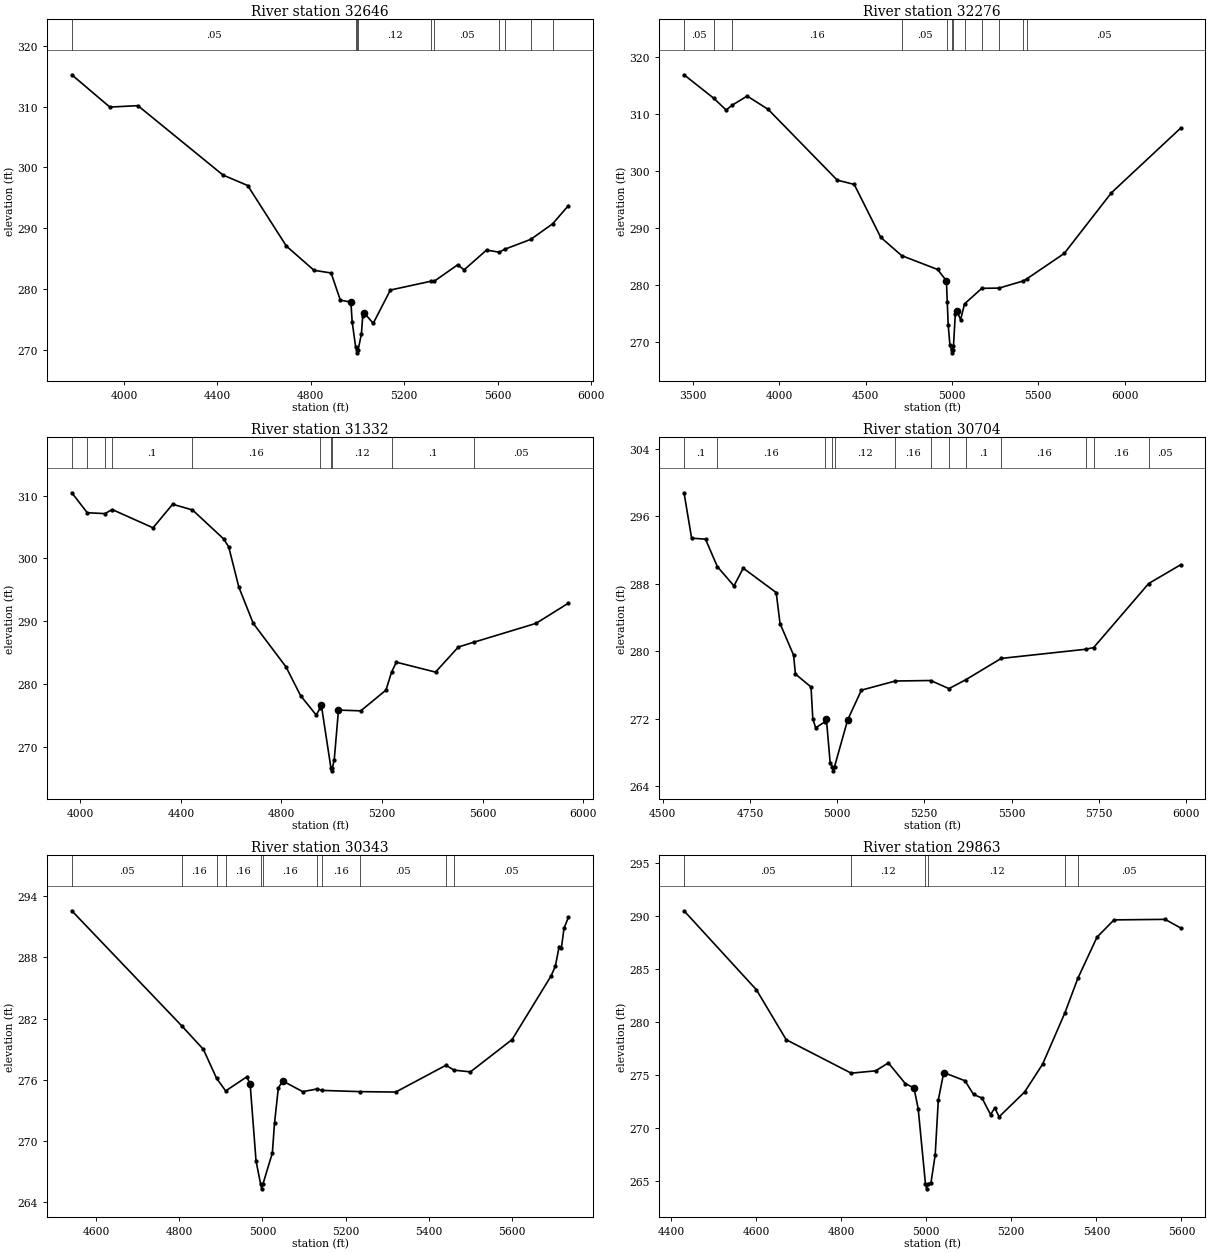
Type RM Length L Ch R = 1 ,32646   ,370,370,370
BEGIN DESCRIPTION:
SAND CREEK 45.0
END DESCRIPTION:
XS GIS Cut Line= 3
      3579164.23     10285551.72      3579642.11     10284941.64
      3580232.11     10283725.45
#Sta/Elev= 30
  3776.5  315.22  3939.3  309.92  4059.6  310.15    4424  298.76  4529.8  297.04
  4695.4   287.1  4813.8  283.12  4887.1  282.68  4926.6  278.22  4971.8   277.9
  4977.3  274.65  4992.4  270.48  4996.9  270.07  4999.7  269.57  5002.9  270.07
  5016.9  272.69  5022.5  275.63  5029.4  276.08  5067.6  274.42  5140.9  279.88
  5313.8  281.32  5327.7   281.3  5428.7  284.01  5456.9   283.2  5552.7  286.44
  5607.6  286.09  5630.2  286.57  5742.3   288.2    5836  290.76  5903.2  293.73
#Mann= 10 ,-1 , 0
  3776.5     .05       0  4992.4     .12       0  4996.9     .07       0
  5002.9     .12       0  5313.8     .16       0  5327.7     .05       0
  5607.6     .16       0  5630.2     .05       0  5742.3     .16       0
    5836     .05       0
Bank Sta=4971.8,5029.4
XS Rating Curve= 0 ,0
Exp/Cntr=0.3,0.1

Type RM Length L Ch R = 1 ,32276   ,944,944,944
BEGIN DESCRIPTION:
SAND CREEK 44.0
END DESCRIPTION:
XS GIS Cut Line= 3
       3579629.5     10286072.58       3580094.8     10285023.93
       3580492.1     10283341.65
#Sta/Elev= 30
    3449  316.89  3621.7  312.76  3692.9  310.71  3727.3  311.55  3814.7  313.16
  3936.5  310.82  4336.2  298.42  4434.7  297.67  4587.8  288.41  4709.6  285.18
  4917.1  282.76  4968.5  280.79  4973.5  277.05  4978.8  273.09    4989  269.46
  4998.2  268.64  5000.9  268.14  5004.2  268.64  5009.6  269.35  5019.9  274.91
  5030.1  275.42  5050.7  273.95  5073.5  276.72  5173.5  279.45  5273.5  279.49
  5413.1  280.74  5435.5  281.14  5651.1  285.57  5924.1   296.2  6324.8  307.53
#Mann= 12 ,-1 , 0
    3449     .05       0  3621.7      .1       0  3727.3     .16       0
  4709.6     .05       0  4973.5     .16       0  4998.2     .07       0
  5004.2     .16       0  5073.5     .12       0  5173.5     .16       0
  5273.5     .05       0  5413.1     .16       0  5435.5     .05       0
Bank Sta=4968.5,5030.1
XS Rating Curve= 0 ,0
Exp/Cntr=0.3,0.1

Type RM Length L Ch R = 1 ,31332   ,628,628,628
BEGIN DESCRIPTION:
SAND CREEK 42.0
END DESCRIPTION:
XS GIS Cut Line= 3
      3581122.58     10285933.66      3581060.07     10285225.32
      3580761.51     10283996.36
#Sta/Elev= 30
  3965.7  310.46  4027.3  307.28  4097.6  307.14  4126.3  307.79    4289  304.88
  4366.8  308.63  4445.7  307.73  4570.1   303.1  4590.1  301.83  4630.3  295.43
  4687.6  289.66    4818  282.72  4876.1  278.14  4937.9  275.06  4953.6  276.12
  4958.4  276.69  4996.6  266.66  4999.3  266.16  5002.6  266.66  5009.9  267.91
  5026.8  275.84  5115.5  275.72  5215.7  279.02  5237.9  281.87  5256.9  283.47
  5412.9  281.89  5503.8  285.89    5567  286.67  5812.6  289.65  5941.5  292.87
#Mann= 10 ,-1 , 0
  3965.7      .1       0  4027.3     .05       0  4097.6     .16       0
  4126.3      .1       0  4445.7     .16       0  4953.6     .12       0
  4996.6     .07       0  5002.6     .12       0  5237.9      .1       0
    5567     .05       0
Bank Sta=4958.4,5026.8
XS Rating Curve= 0 ,0
Exp/Cntr=0.3,0.1

Type RM Length L Ch R = 1 ,30704   ,361,361,361
BEGIN DESCRIPTION:
SAND CREEK 41.0
END DESCRIPTION:
XS GIS Cut Line= 3
      3581642.09      10285291.6      3581579.86      10285146.4
      3581319.78     10283907.68
#Sta/Elev= 30
  4561.1  298.79  4582.8  293.41  4622.7  293.29  4656.5  290.04  4704.3  287.75
  4730.8  289.85  4825.4  286.96  4836.3  283.29  4875.3  279.53  4880.4   277.3
  4925.2  275.76  4930.3  271.99  4938.5  270.92  4964.5  271.62  4969.2     272
  4980.1  266.74  4986.6  266.32  4989.4  265.82  4992.6  266.32  5030.5  271.89
  5069.7  275.39  5166.9  276.47  5268.1  276.53  5320.7  275.57  5369.3  276.63
  5470.5  279.15  5713.5  280.24  5735.6  280.44  5893.3  288.03  5984.8  290.25
#Mann= 13 ,-1 , 0
  4561.1      .1       0  4656.5     .16       0  4964.5     .12       0
  4986.6     .07       0  4992.6     .12       0  5166.9     .16       0
  5268.1      .1       0  5320.7     .16       0  5369.3      .1       0
  5470.5     .16       0  5713.5     .05       0  5735.6     .16       0
  5893.3     .05       0
Bank Sta=4969.2,5030.5
XS Rating Curve= 0 ,0
Exp/Cntr=0.3,0.1

Type RM Length L Ch R = 1 ,30343   ,480,480,480
BEGIN DESCRIPTION:
SAND CREEK 40.0
END DESCRIPTION:
XS GIS Cut Line= 3
      3581997.57     10285058.65      3581792.11     10284641.64
       3581592.1     10283941.63
#Sta/Elev= 30
    4542  292.58    4806  281.29  4858.1  278.98  4889.9  276.13  4911.7   274.9
  4962.3  276.28  4970.4  275.58  4984.6  268.03  4995.4  265.79  4998.2  265.29
  5001.4  265.79  5023.8  268.81    5029  271.75  5038.1  275.17  5048.5  275.88
  5096.6  274.83    5131  275.09  5144.2  274.95  5234.3  274.83  5320.2  274.79
  5440.9  277.42  5460.1  276.94  5499.6  276.77  5599.7  279.94  5693.3  286.18
  5703.7  287.15  5712.8  289.07    5718  288.88  5724.5  290.87  5734.9  291.93
#Mann= 11 ,-1 , 0
    4542     .05       0    4806     .16       0  4889.9     .12       0
  4911.7     .16       0  4995.4     .07       0  5001.4     .16       0
    5131     .12       0  5144.2     .16       0  5234.3     .05       0
  5440.9     .16       0  5460.1     .05       0
Bank Sta=4970.4,5048.5
XS Rating Curve= 0 ,0
Exp/Cntr=0.3,0.1

Type RM Length L Ch R = 1 ,29863   ,573,573,573
BEGIN DESCRIPTION:
SAND CREEK 39.0
END DESCRIPTION:
XS GIS Cut Line= 2
      3582192.11     10284941.67      3582143.46     10283775.28
#Sta/Elev= 30
  4430.6  290.48  4600.8  283.02  4670.8  278.31  4823.6  275.15    4881  275.37
    4911  276.12  4951.1  274.15  4971.1  273.77  4981.1  271.79  4998.1  264.73
  5000.9  264.23  5004.1  264.73  5011.1  264.78  5021.1  267.45  5028.4  272.62
  5041.2  275.21  5091.2  274.43  5111.2  273.14  5131.2   272.8  5151.2  271.24
  5161.3  271.87  5171.3  271.03  5231.3  273.37  5273.5  275.99  5326.2  280.86
  5356.3  284.09  5401.5  287.99  5441.5  289.62  5561.6  289.67    5598  288.86
#Mann= 6 ,-1 , 0
  4430.6     .05       0  4823.6     .12       0  4998.1     .07       0
  5004.1     .12       0  5326.2      .1       0  5356.3     .05       0
Bank Sta=4971.1,5041.2
XS Rating Curve= 0 ,0
Exp/Cntr=0.3,0.1

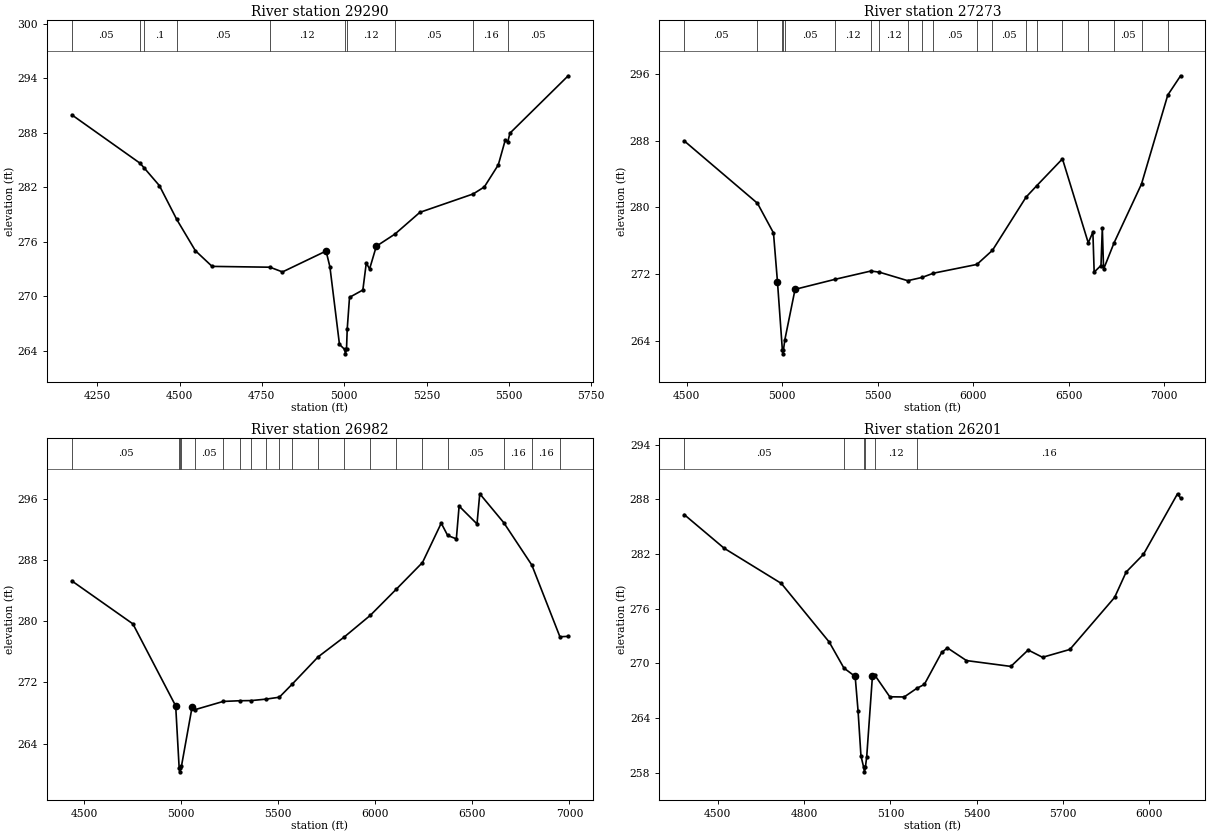
Type RM Length L Ch R = 1 ,29290   ,2017,2017,2017
BEGIN DESCRIPTION:
SAND CREEK 37.0
END DESCRIPTION:
XS GIS Cut Line= 4
      3582608.68      10284871.2      3582652.19     10284610.96
      3582474.35     10283662.14      3582282.29     10283461.42
#Sta/Elev= 30
    4173  289.99  4380.2  284.66  4391.8  284.18    4439  282.19  4491.6  278.47
  4548.1  275.03  4598.9   273.3  4774.6  273.21  4812.6  272.69  4944.9  274.99
  4956.6  273.25  4985.6  264.71    5001  264.17  5003.8  263.67    5007  264.17
  5009.1  266.37  5016.1  269.89  5056.6   270.7    5067  273.67  5077.1  273.02
  5097.5  275.52  5154.1  276.86  5229.7  279.25  5391.7  281.28  5425.4  282.05
  5467.8  284.48  5488.9  287.21  5496.5  287.01  5503.1  287.97    5680  294.29
#Mann= 10 ,-1 , 0
    4173     .05       0  4380.2     .16       0  4391.8      .1       0
  4491.6     .05       0  4774.6     .12       0    5001     .07       0
    5007     .12       0  5154.1     .05       0  5391.7     .16       0
  5496.5     .05       0
Bank Sta=4944.9,5097.5
XS Rating Curve= 0 ,0
Exp/Cntr=0.3,0.1

Type RM Length L Ch R = 1 ,27273   ,291,291,291
BEGIN DESCRIPTION:
SAND CREEK 34.0
END DESCRIPTION:
XS GIS Cut Line= 2
      3584077.69      10284875.3      3582367.57     10282917.78
#Sta/Elev= 30
  4486.9  287.99  4870.6   280.5  4954.4  276.94  4975.3  271.07  5000.8  262.93
  5003.5  262.43  5006.8  262.93  5014.2  264.15  5067.4  270.17  5278.1  271.38
  5464.8  272.37    5509  272.23  5657.2  271.21  5732.4   271.6  5792.3  272.11
  6019.7  273.16  6101.2  274.86  6277.1  281.24  6332.6   282.6  6467.6  285.83
  6602.7  275.75  6626.9  277.04  6633.6  272.24  6669.4  273.03  6676.3  277.55
  6682.9  272.59  6737.8  275.75  6881.5  282.81  7019.1  293.49  7086.2   295.8
#Mann= 20 ,-1 , 0
  4486.9     .05       0  4870.6     .05       0  5000.8     .07       0
  5006.8     .08       0  5014.2     .05       0  5278.1     .12       0
  5464.8     .08       0    5509     .12       0  5657.2     .05       0
  5732.4     .12       0  5792.3     .05       0  6019.7     .12       0
  6101.2     .05       0  6277.1     .12       0  6332.6     .05       0
  6467.6     .05       0  6602.7     .05       0  6737.8     .05       0
  6881.5     .05       0  7019.1     .05       0
Bank Sta=4975.3,5067.4
XS Rating Curve= 0 ,0
Exp/Cntr=0.3,0.1

Type RM Length L Ch R = 1 ,26982   ,781,781,781
BEGIN DESCRIPTION:
Mapping XS 4b8f9548
END DESCRIPTION:
XS GIS Cut Line= 2
      3584351.14     10284766.81      3582680.09     10282830.99
#Sta/Elev= 30
  4436.2  285.27    4751  279.65  4971.4  268.93  4989.3  260.82    4992  260.32
  4995.3  260.82  5001.3  261.08  5055.9  268.79  5071.8  268.45  5216.3  269.52
  5302.7  269.61  5360.8  269.63    5437  269.82  5505.4  270.07  5571.3  271.77
  5705.6  275.35  5839.9  277.94  5974.2  280.77  6108.6   284.2  6242.9  287.67
  6339.4  292.81  6372.6   291.2  6417.3  290.76  6431.5  295.04  6523.7  292.71
  6537.9  296.65  6661.7  292.87  6806.3  287.33  6950.8  277.97  6993.5  278.02
#Mann= 20 ,-1 , 0
  4436.2     .05       0  4989.3     .04       0  4995.3     .05       0
  5001.3     .12       0  5071.8     .05       0  5216.3     .05       0
  5302.7     .16       0  5360.8     .05       0    5437     .16       0
  5505.4     .05       0  5571.3     .16       0  5705.6      .1       0
  5839.9      .1       0  5974.2      .1       0  6108.6      .1       0
  6242.9      .1       0  6372.6     .05       0  6661.7     .16       0
  6806.3     .16       0  6950.8     .12       0
Bank Sta=4971.4,5055.9
XS Rating Curve= 0 ,0
Exp/Cntr=0.3,0.1

Type RM Length L Ch R = 1 ,26201   ,1185,1185,1185
BEGIN DESCRIPTION:
SAND CREEK 33.0
END DESCRIPTION:
XS GIS Cut Line= 4
      3584558.64     10284791.76      3584653.13      10284467.9
      3584576.01     10283090.34      3584576.01     10283097.85
#Sta/Elev= 30
  4383.6  286.33  4522.7  282.63    4721  278.78  4887.5  272.35  4938.5   269.5
  4977.6  268.58  4987.6  264.82  4997.7  259.87  5007.1  258.62  5009.9  258.12
  5013.1  258.62  5017.7  259.77  5037.7  268.67    5045  268.76  5097.8  266.35
  5147.9  266.33  5190.9  267.26    5218  267.71  5278.1  271.21  5298.1  271.71
  5364.3  270.32  5518.5  269.68  5578.6  271.48  5628.6  270.68  5723.5  271.54
    5879  277.25  5919.1  280.03  5979.2  281.97  6097.5  288.61  6108.2  288.13
#Mann= 6 ,-1 , 0
  4383.6     .05       0  4938.5     .16       0  5007.1     .07       0
  5013.1     .16       0    5045     .12       0  5190.9     .16       0
Bank Sta=4977.6,5037.7
XS Rating Curve= 0 ,0
Exp/Cntr=0.3,0.1