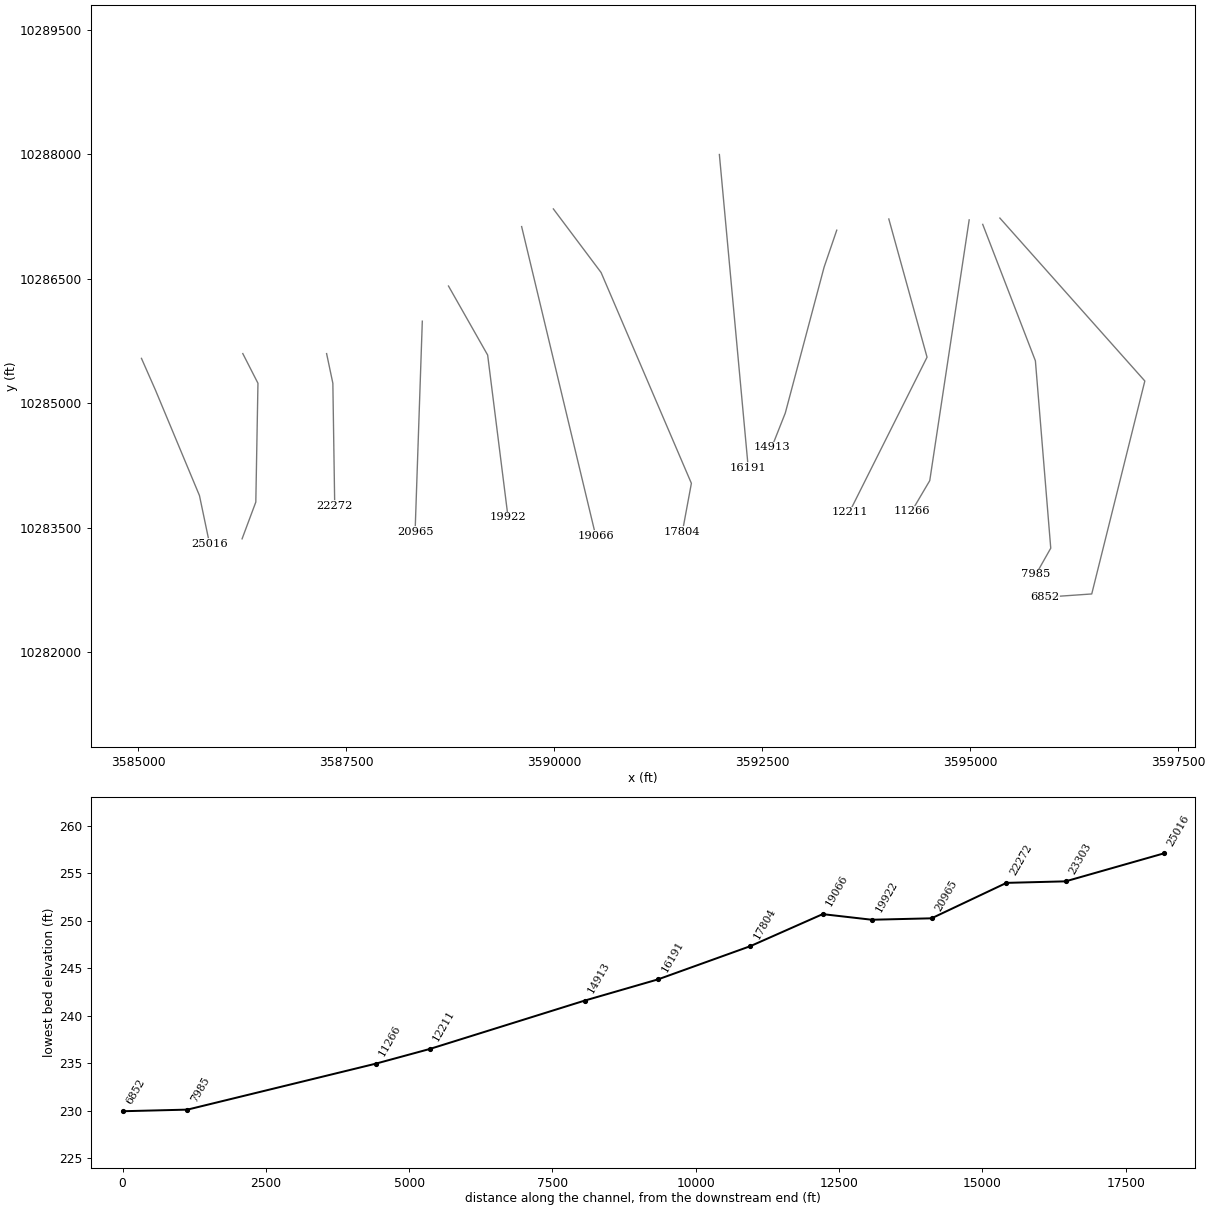
HEC-RAS study SAND CREEK.prj: SAND CREEK Base Level Engineering

--- SAND CREEK.g01 (geometry) --- (continued)

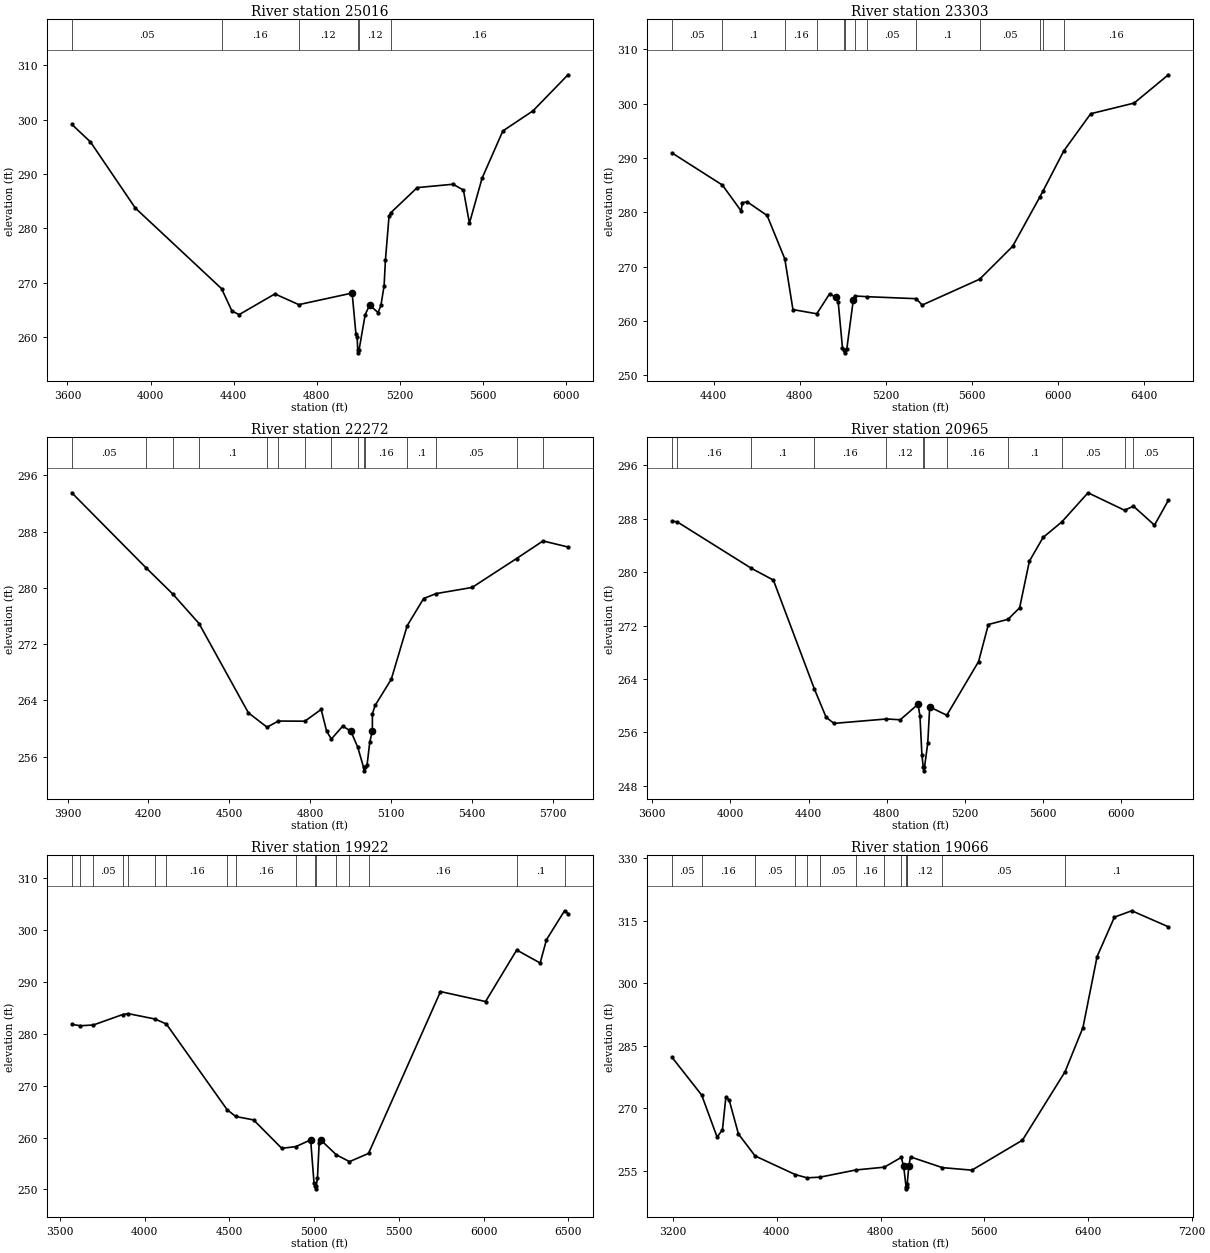
Type RM Length L Ch R = 1 ,25016   ,1713,1713,1713
BEGIN DESCRIPTION:
SAND CREEK 31.0
END DESCRIPTION:
XS GIS Cut Line= 4
      3585042.09     10285541.68      3585210.18     10285159.65
       3585739.2     10283888.95      3585860.74     10283307.31
#Sta/Elev= 30
  3620.9  299.13  3710.8  295.89  3926.4  283.74  4341.7   268.9  4391.3   264.8
  4426.1  264.12  4598.3  267.93  4713.4  265.96    4970  268.09  4988.4  260.52
  4993.9     260  4997.2  257.59  4999.9  257.09  5003.2  257.59  5032.7  264.11
  5054.3  265.89  5094.6  264.49  5108.5   265.8  5123.9  269.46  5130.2  274.14
  5147.7  282.28    5155  282.83  5283.2  287.49  5455.6  288.11  5505.6  287.04
  5534.5  280.94  5595.4  289.23  5695.3  297.91  5840.2  301.61  6008.9  308.25
#Mann= 6 ,-1 , 0
  3620.9     .05       0  4341.7     .16       0  4713.4     .12       0
  4997.2     .07       0  5003.2     .12       0    5155     .16       0
Bank Sta=4970,5054.3
XS Rating Curve= 0 ,0
Exp/Cntr=0.3,0.1

Type RM Length L Ch R = 1 ,23303   ,1031,1031,1031
BEGIN DESCRIPTION:
SAND CREEK 29.0
END DESCRIPTION:
XS GIS Cut Line= 4
      3586260.02     10285599.05      3586442.11     10285241.64
      3586416.29     10283810.82      3586251.36     10283368.12
#Sta/Elev= 30
  4207.1  290.93  4440.5  285.03  4527.6  280.27  4533.2  281.79  4555.4  281.95
  4648.2  279.43  4730.4  271.44  4768.2  262.11  4878.9  261.34  4938.3  265.01
  4968.3  264.35  4978.3  263.53  4998.3  255.03  5005.3  254.65    5008  254.15
  5011.3  254.65  5018.3  254.87  5048.3  263.83  5057.5  264.62  5114.1  264.48
  5340.5  264.12  5368.3  262.94  5635.4  267.71  5788.4  273.75  5914.7  282.83
  5930.7  284.02  6026.1  291.32    6151  298.16  6352.6  300.12  6511.7  305.33
#Mann= 13 ,-1 , 0
  4207.1     .05       0  4440.5      .1       0  4730.4     .16       0
  4878.9     .05       0  5005.3     .03       0  5011.3     .05       0
  5057.5     .16       0  5114.1     .05       0  5340.5      .1       0
  5635.4     .05       0  5914.7     .16       0  5930.7     .05       0
  6026.1     .16       0
Bank Sta=4968.3,5048.3
XS Rating Curve= 0 ,0
Exp/Cntr=0.3,0.1

Type RM Length L Ch R = 1 ,22272   ,1307,1307,1307
BEGIN DESCRIPTION:
SAND CREEK 27.0
END DESCRIPTION:
XS GIS Cut Line= 3
      3587266.98       10285599.      3587342.11     10285241.64
      3587364.62     10283765.98
#Sta/Elev= 30
  3915.6  293.53    4190   282.9  4289.4  279.17  4387.6  274.94  4570.8  262.24
  4639.9   260.2  4682.1  261.07  4780.3  261.05  4840.8  262.72  4860.8  259.65
  4878.5  258.51  4920.8  260.35  4950.8  259.63  4976.7  257.34  4997.9  254.49
  5000.6  253.99  5003.9  254.49  5010.9  254.75  5020.9  258.02  5030.7   259.7
  5030.9  262.12  5040.9  263.29  5100.9  267.01    5160  274.63  5220.9  278.49
  5266.9  279.19  5400.9  280.07  5565.7  284.18  5663.9  286.68  5756.6  285.82
#Mann= 15 ,-1 , 0
  3915.6     .05       0    4190      .1       0  4289.4     .05       0
  4387.6      .1       0  4639.9     .05       0  4682.1      .1       0
  4780.3     .12       0  4878.5      .1       0  4976.7     .16       0
  4997.9     .07       0  5003.9     .16       0    5160      .1       0
  5266.9     .05       0  5565.7      .1       0  5663.9     .05       0
Bank Sta=4950.8,5030.7
XS Rating Curve= 0 ,0
Exp/Cntr=0.3,0.1

Type RM Length L Ch R = 1 ,20965   ,1043,1043,1043
BEGIN DESCRIPTION:
SAND CREEK 24.0
END DESCRIPTION:
XS GIS Cut Line= 2
      3588417.15     10285989.61      3588330.35      10283450.6
#Sta/Elev= 30
  3701.4  287.62  3728.3  287.49  4106.9  280.56  4219.7   278.8  4429.6  262.51
  4489.8  258.27  4529.9  257.36  4798.7  258.02  4869.3   257.9  4960.1  260.22
  4970.1   258.5  4980.1  252.69  4987.1  250.76  4989.9  250.26  4993.1  250.76
  5010.1  254.41  5020.1  259.82  5107.5  258.58  5270.3  266.61  5320.3  272.15
  5420.9  272.93  5480.4  274.65  5530.4  281.63  5600.5  285.18  5696.5   287.5
  5830.6  291.86  6017.4  289.25  6063.3  289.85  6170.8  287.02  6241.9  290.73
#Mann= 12 ,-1 , 0
  3701.4     .05       0  3728.3     .16       0  4106.9      .1       0
  4429.6     .16       0  4798.7     .12       0  4987.1     .07       0
  4993.1     .12       0  5107.5     .16       0  5420.9      .1       0
  5696.5     .05       0  6017.4     .16       0  6063.3     .05       0
Bank Sta=4960.1,5020.1
XS Rating Curve= 0 ,0
Exp/Cntr=0.3,0.1

Type RM Length L Ch R = 1 ,19922   ,856,856,856
BEGIN DESCRIPTION:
SAND CREEK 22.0
END DESCRIPTION:
XS GIS Cut Line= 3
      3588731.81     10286412.85      3589202.42     10285581.33
      3589447.81     10283625.42
#Sta/Elev= 30
    3571  281.85  3621.3  281.58    3698  281.72  3870.3  283.73    3903  283.92
    4063  282.87    4129   281.9    4487  265.39  4537.6  264.07  4643.2  263.41
  4809.2  257.93  4892.9  258.26  4979.7  259.56  4999.8  251.17  5006.9  250.61
  5009.7  250.11  5012.9  250.61    5020  252.25  5030.1  259.02  5040.1  259.52
    5131  256.68  5208.8  255.36  5321.1  256.94  5745.6  288.17  6011.4  286.25
  6195.1  296.19  6333.3  293.68  6370.5  298.17  6477.1  303.76  6497.7  303.23
#Mann= 17 ,-1 , 0
    3571     .05       0  3621.3      .1       0    3698     .05       0
  3870.3      .1       0    3903     .05       0    4063      .1       0
    4129     .16       0    4487     .05       0  4537.6     .16       0
  4892.9     .12       0  5006.9     .07       0  5012.9     .12       0
    5131     .16       0  5208.8     .12       0  5321.1     .16       0
  6195.1      .1       0  6477.1     .16       0
Bank Sta=4979.7,5040.1
XS Rating Curve= 0 ,0
Exp/Cntr=0.3,0.1

Type RM Length L Ch R = 1 ,19066   ,1262,1262,1262
BEGIN DESCRIPTION:
SAND CREEK 20.0
END DESCRIPTION:
XS GIS Cut Line= 2
      3589610.72     10287129.01      3590500.48     10283407.19
#Sta/Elev= 30
  3193.1  282.22  3420.9   273.2    3540   263.1  3581.1  264.88  3607.2  272.62
  3632.5  272.07  3704.5  263.85    3833  258.59  4141.1  254.14  4233.2  253.34
  4333.2   253.5  4610.5  255.23  4829.8   255.9  4959.7  258.24  4978.4  256.13
    4997   251.2  4999.7   250.7    5003   251.2  5005.9  251.86 5018.19  256.13
  5031.4  258.36  5277.1  255.79  5504.5  255.18  5894.5  262.37    6223  278.78
  6361.2   289.4  6470.3  306.43  6603.9  315.89  6737.6  317.41  7019.8  313.57
#Mann= 14 ,-1 , 0
  3193.1     .05       0  3420.9     .16       0    3833     .05       0
  4141.1      .1       0  4233.2     .12       0  4333.2     .05       0
  4610.5     .16       0  4829.8     .12       0  4959.7     .16       0
    4997     .07       0    5003     .16       0  5005.9     .12       0
  5277.1     .05       0    6223      .1       0
Bank Sta=4978.4,5018.19
XS Rating Curve= 0 ,0
Exp/Cntr=0.3,0.1

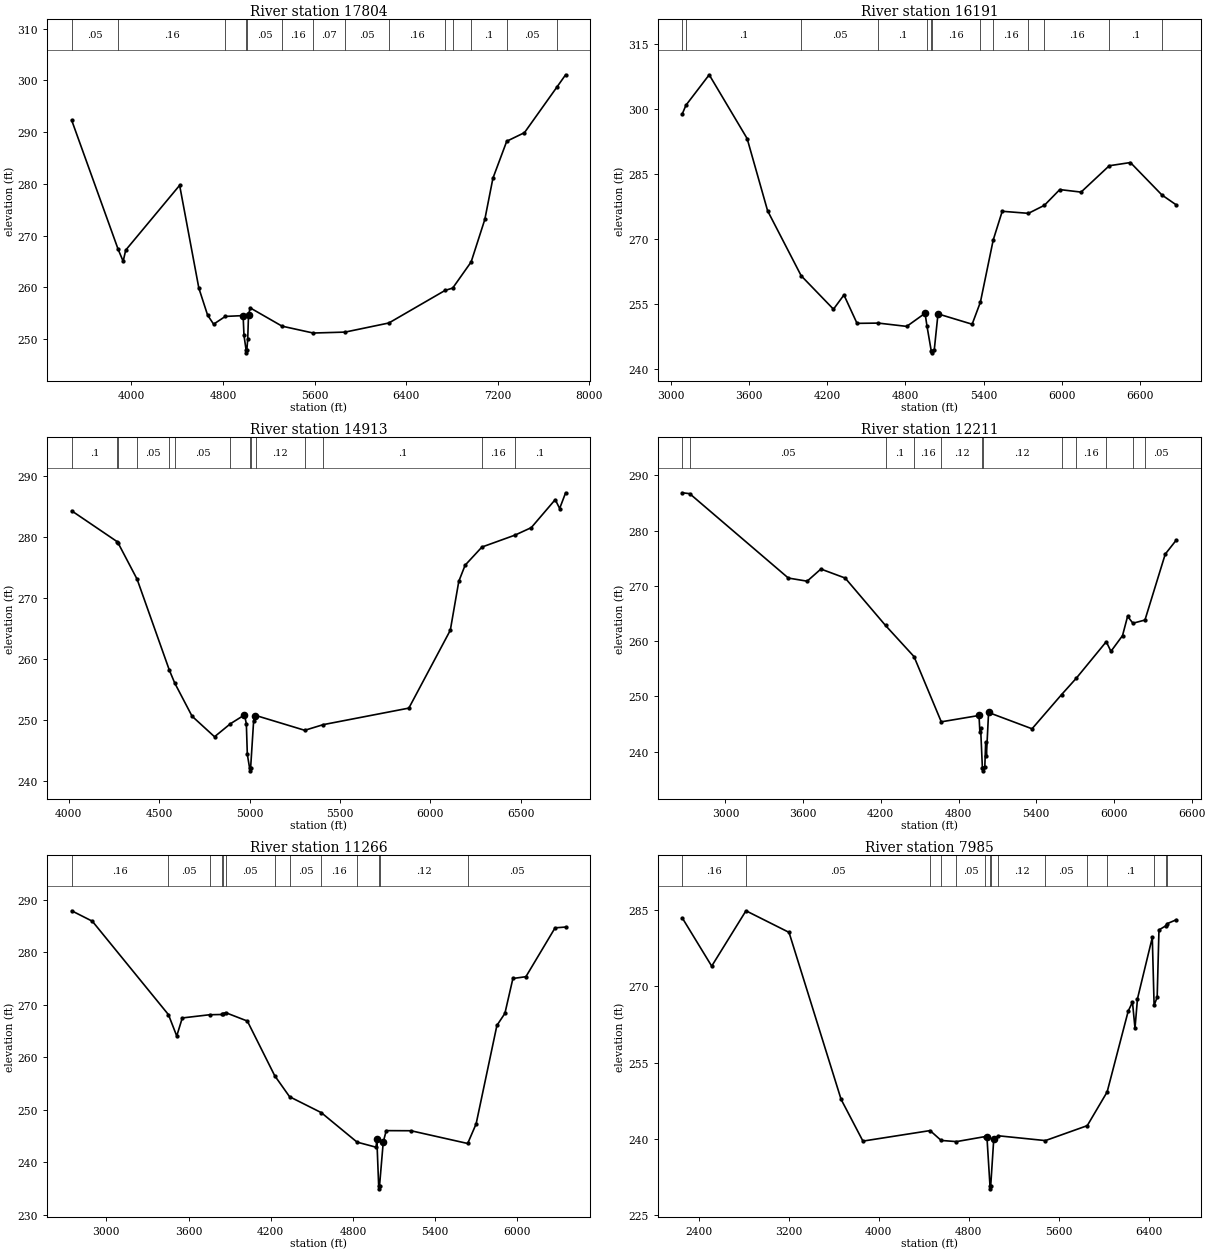
Type RM Length L Ch R = 1 ,17804   ,1613,1613,1613
BEGIN DESCRIPTION:
SAND CREEK 19.0
END DESCRIPTION:
XS GIS Cut Line= 4
      3589992.12     10287341.63      3590565.59     10286575.58
      3591650.66     10284036.52      3591542.16      10283450.6
#Sta/Elev= 30
  3478.3   292.3  3884.5  267.32    3928  265.03  3950.3  267.19  4421.2  279.72
    4589  259.84  4665.3  254.63  4717.9  252.87    4820  254.37  4975.6  254.53
  4983.2   250.7    5002  247.83  5004.7  247.33    5008  247.83  5015.9  250.01
  5022.8   254.7  5037.6  256.02  5315.5  252.49  5587.6  251.16  5866.5  251.34
  6248.4   253.1  6740.5  259.41    6806  259.85  6967.1   264.9  7086.6  273.12
  7157.4  281.09    7278  288.24  7432.9   289.9  7714.6  298.66  7792.3  301.09
#Mann= 14 ,-1 , 0
  3478.3     .05       0  3884.5     .16       0    4820     .05       0
    5002    .035       0    5008     .05       0  5315.5     .16       0
  5587.6     .07       0  5866.5     .05       0  6248.4     .16       0
  6740.5      .1       0    6806     .16       0  6967.1      .1       0
    7278     .05       0  7714.6      .1       0
Bank Sta=4975.6,5022.8
XS Rating Curve= 0 ,0
Exp/Cntr=0.3,0.1

Type RM Length L Ch R = 1 ,16191   ,1278,1278,1278
BEGIN DESCRIPTION:
SAND CREEK 16.0
END DESCRIPTION:
XS GIS Cut Line= 2
      3591987.03     10287996.99      3592334.25     10284221.02
#Sta/Elev= 30
  3087.1  298.89  3114.8  300.86  3293.3  307.87  3584.5  293.18  3741.7  276.54
  3999.4  261.58  4247.3  253.88  4327.7  257.16  4428.1  250.62  4592.3  250.68
  4809.7  249.92  4950.3  252.94  4965.3  249.97  4997.5  244.33  5000.2  243.83
  5003.5  244.33  5020.6  244.37  5049.7   252.8  5311.8  250.42  5375.3  255.51
  5473.6  269.82  5542.8  276.43  5743.8  275.96  5866.2   277.8  5984.6  281.43
    6148  280.85  6364.4  286.92  6526.9  287.66    6769  280.18    6879   277.9
#Mann= 13 ,-1 , 0
  3087.1     .16       0  3114.8      .1       0  3999.4     .05       0
  4592.3      .1       0  4965.3     .16       0  4997.5     .07       0
  5003.5     .16       0  5375.3     .12       0  5473.6     .16       0
  5743.8      .1       0  5866.2     .16       0  6364.4      .1       0
    6769     .05       0
Bank Sta=4950.3,5049.7
XS Rating Curve= 0 ,0
Exp/Cntr=0.3,0.1

Type RM Length L Ch R = 1 ,14913   ,2702,2702,2702
BEGIN DESCRIPTION:
SAND CREEK 14.0
END DESCRIPTION:
XS GIS Cut Line= 4
      3593397.63     10287085.59      3593245.71     10286640.68
      3592779.13     10284882.87      3592616.74     10284471.47
#Sta/Elev= 30
  4016.6  284.25  4269.7  279.16  4273.2  278.98  4378.4  273.03  4556.6  258.12
  4586.4     256  4682.3  250.56  4806.5  247.19  4894.5  249.33    4972  250.77
  4982.4  249.32  4987.8   244.3  5000.1   242.1  5002.8   241.6  5006.1   242.1
  5022.8  249.85    5028  250.63  5035.9  250.67  5305.2  248.25  5407.9  249.18
  5880.9  251.89  6110.1  264.66    6157  272.68    6192  275.33    6285  278.31
  6467.3  280.26  6557.7  281.49  6690.3  286.09  6714.7  284.63  6747.7  287.21
#Mann= 14 ,-1 , 0
  4016.6      .1       0  4269.7     .05       0  4273.2      .1       0
  4378.4     .05       0  4556.6      .1       0  4586.4     .05       0
  4894.5     .16       0  5000.1     .07       0  5006.1     .16       0
  5035.9     .12       0  5305.2     .16       0  5407.9      .1       0
    6285     .16       0  6467.3      .1       0
Bank Sta=4972,5028
XS Rating Curve= 0 ,0
Exp/Cntr=0.3,0.1

Type RM Length L Ch R = 1 ,12211   ,945,945,945
BEGIN DESCRIPTION:
SAND CREEK 13.0
END DESCRIPTION:
XS GIS Cut Line= 3
      3594023.27     10287220.48      3594482.69     10285555.61
      3593549.53     10283689.29
#Sta/Elev= 30
  2667.7  286.83  2724.4  286.67    3486   271.4  3631.3  270.83  3737.4  273.03
  3924.8   271.4  4236.4  262.82  4456.6  257.18  4666.9  245.38  4958.2  246.53
  4965.1  243.47  4970.7  244.22  4984.4  237.01  4987.2  236.51  4990.4  237.01
    5003  237.23  5009.8  241.76  5015.4  239.26  5032.1  247.07  5367.6  244.12
  5595.4   250.3  5709.6  253.28  5940.8  259.88  5976.9  258.13  6066.3  260.98
  6105.5  264.48  6146.5  263.22  6239.5   263.8  6396.2  275.73  6481.4  278.27
#Mann= 12 ,-1 , 0
  2667.7     .16       0  2724.4     .05       0  4236.4      .1       0
  4456.6     .16       0  4666.9     .12       0  4984.4     .07       0
  4990.4     .12       0  5595.4     .05       0  5709.6     .16       0
  5940.8     .05       0  6146.5      .1       0  6239.5     .05       0
Bank Sta=4958.2,5032.1
XS Rating Curve= 0 ,0
Exp/Cntr=0.3,0.1

Type RM Length L Ch R = 1 ,11266   ,3281,3281,3281
BEGIN DESCRIPTION:
SAND CREEK 10.0
END DESCRIPTION:
XS GIS Cut Line= 3
      3594988.97     10287209.67      3594515.24     10284069.07
      3594298.25     10283700.18
#Sta/Elev= 30
  2747.2  287.94  2897.9  285.95  3453.3  268.15  3513.8  264.08  3554.3  267.52
  3753.1  268.13  3843.3  268.18    3853  268.35  3869.7  268.54    4029  266.93
  4228.6  256.52  4337.2  252.51  4568.4  249.48  4829.6  243.86  4968.6  242.89
  4973.7  244.53  4987.3  235.46  4990.1  234.96  4993.3  235.46  5020.7   243.9
  5042.6  246.05  5222.9  246.03  5636.7   243.6  5698.2  247.33  5849.9  266.09
  5908.2  268.39  5966.7  275.04  6061.5  275.38  6274.4  284.69  6351.3  284.84
#Mann= 13 ,-1 , 0
  2747.2     .16       0  3453.3     .05       0  3753.1      .1       0
  3843.3     .05       0    3853      .1       0  3869.7     .05       0
  4228.6      .1       0  4337.2     .05       0  4568.4     .16       0
  4829.6     .12       0  4987.3     .07       0  4993.3     .12       0
  5636.7     .05       0
Bank Sta=4973.7,5020.7
XS Rating Curve= 0 ,0
Exp/Cntr=0.3,0.1

Type RM Length L Ch R = 1 ,7985    ,1133,1133,1133
BEGIN DESCRIPTION:
SAND CREEK 7.0
END DESCRIPTION:
XS GIS Cut Line= 4
      3595151.73     10287155.41      3595784.77     10285512.21
      3595969.24     10283255.27      3595792.09     10282941.62
#Sta/Elev= 30
  2256.3  283.45  2516.9  273.98  2821.3  284.88  3203.4  280.63  3665.8  247.75
  3859.6  239.53    4456   241.6  4554.2  239.66  4690.1  239.43  4947.2  240.43
  4960.9  240.27    4988  230.63  4990.8  230.13    4994  230.63  5021.1  239.88
  5060.2  240.58  5479.7  239.63  5851.4  242.57  6027.8   249.2  6215.1  265.13
  6252.9  266.89  6275.3  261.76  6297.3  267.56  6428.9  279.62    6445  266.26
  6472.2  267.85  6488.1  281.11    6552  281.96  6560.3  282.34  6641.9  283.11
#Mann= 15 ,-1 , 0
  2256.3     .16       0  2821.3     .05       0    4456     .05       0
  4554.2      .1       0  4690.1     .05       0  4947.2     .16       0
    4988     .07       0    4994     .16       0  5060.2     .12       0
  5479.7     .05       0  5851.4     .12       0  6027.8      .1       0
    6445     .05       0    6552      .1       0  6560.3     .05       0
Bank Sta=4960.9,5021.1
XS Rating Curve= 0 ,0
Exp/Cntr=0.3,0.1

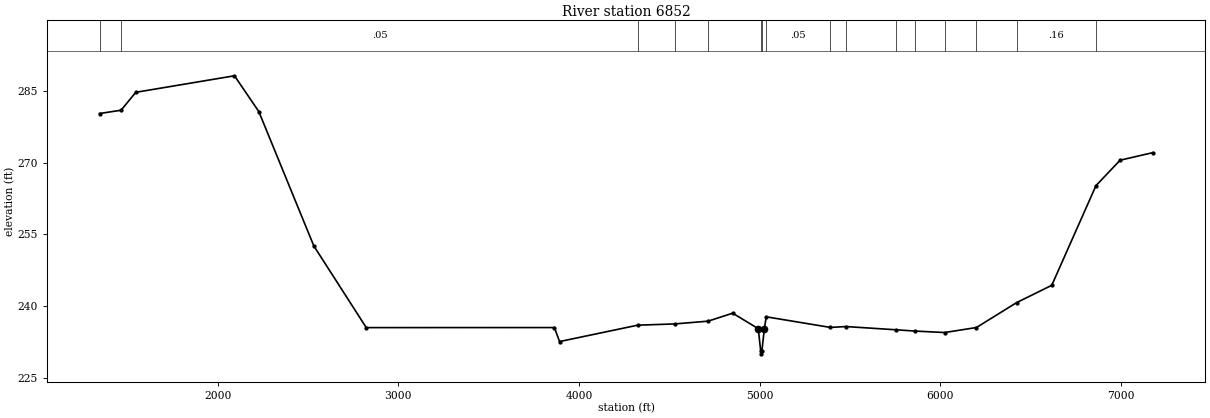
Type RM Length L Ch R = 1 ,6852    ,0,0,0
BEGIN DESCRIPTION:
SAND CREEK 1.0
END DESCRIPTION:
XS GIS Cut Line= 4
       3595357.9     10287231.37      3597099.88     10285269.15
      3596461.86     10282704.05      3595901.96     10282664.99
#Sta/Elev= 30
  1346.9  280.26  1466.1  280.95  1547.7   284.7  2093.8  288.16  2228.4  280.67
  2532.8  252.55    2823  235.45  3864.2  235.46  3892.6  232.53  4325.1  235.96
  4529.5  236.22  4714.7   236.8  4850.8  238.47 4992.31  235.22    5006  230.46
  5008.7  229.96    5012  230.46 5026.19  235.25  5036.4  237.71  5391.2  235.49
  5478.1  235.67  5756.1  234.99  5858.3  234.73    6024  234.42  6199.7  235.47
  6421.8  240.68  6616.4   244.3  6861.1  265.17  6994.7  270.49  7175.3  272.07
#Mann= 16 ,-1 , 0
  1346.9     .16       0  1466.1     .05       0  4325.1     .05       0
  4529.5     .16       0  4714.7     .12       0    5006     .07       0
    5012     .12       0  5036.4     .05       0  5391.2     .16       0
  5478.1     .05       0  5756.1     .16       0  5858.3     .05       0
    6024     .16       0  6199.7     .05       0  6421.8     .16       0
  6861.1     .05       0
Bank Sta=4992.31,5026.19
XS Rating Curve= 0 ,0
Exp/Cntr=0.3,0.1

Chan Stop Cuts=-1
Use User Specified Reach Order=0
Composite Channel Slope=5