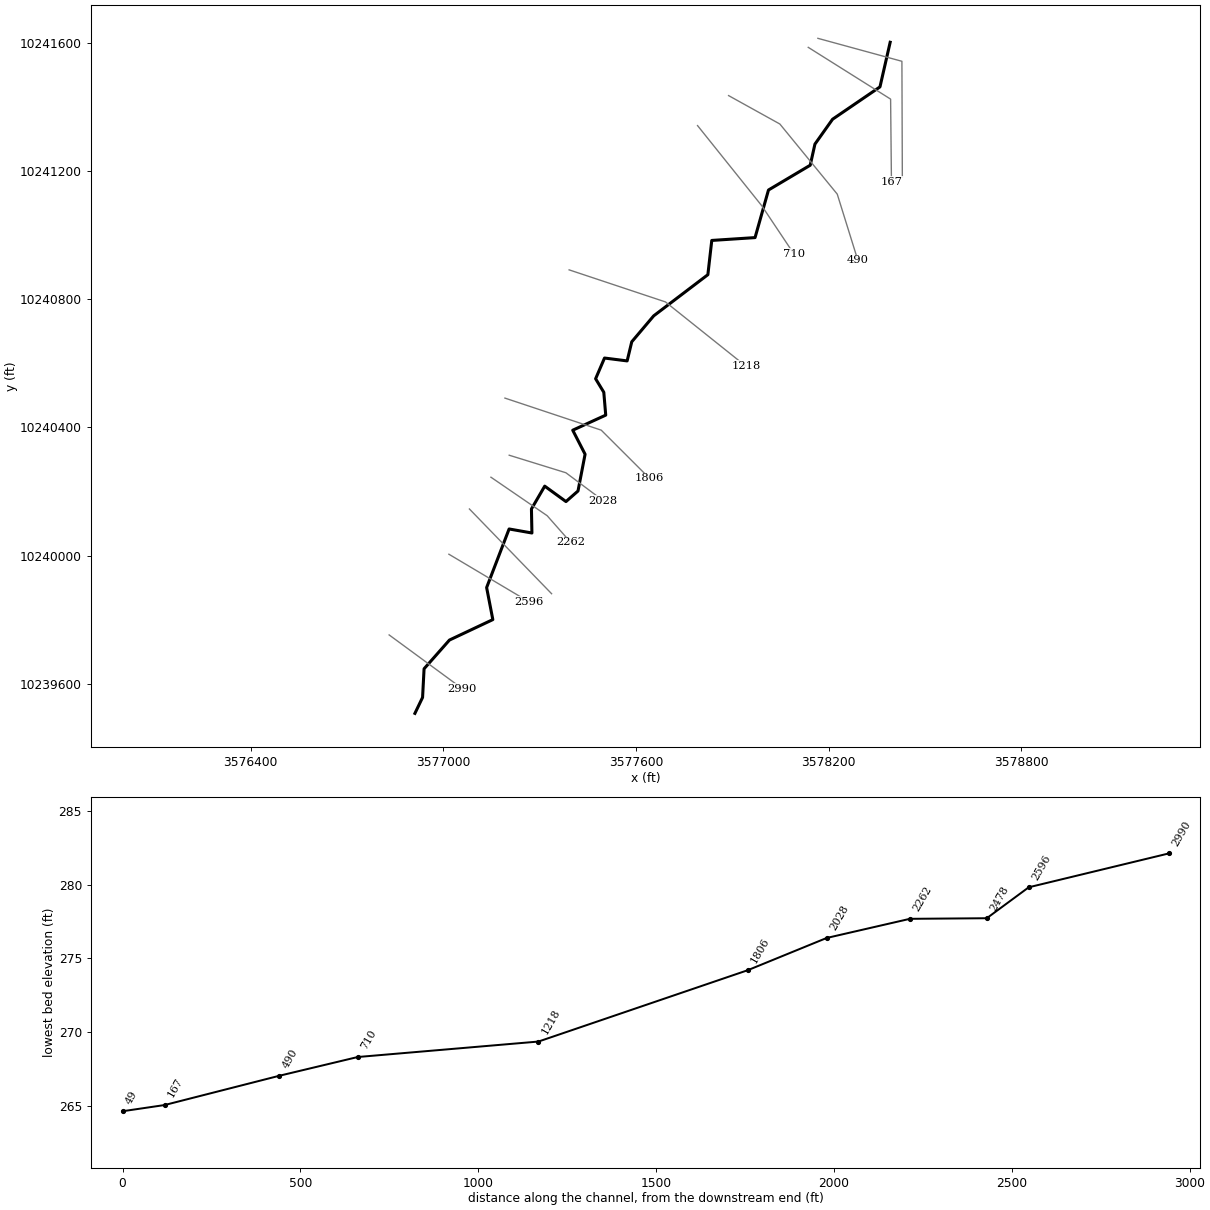
--- STEEP HOLLOW BRANCH TRIB 1 1.prj (project) ---

Proj Title=STEEP HOLLOW BRANCH TRIB 1 1 Base Level Engineering
Current Plan=p01
Default Exp/Contr=0.3,0.1
English Units
Geom File=g01
Flow File=f01
Plan File=p01
Y Axis Title=Elevation
X Axis Title(PF)=Main Channel Distance
X Axis Title(XS)=Station
BEGIN DESCRIPTION:
STEEP HOLLOW BRANCH TRIB 1 1
END DESCRIPTION:
DSS Export Rating Curves= 0
DSS Export Rating Curve Sorted= 0
DSS Export Volume Flow Curves= 0
DXF OffsetX= 0
DXF OffsetY= 0
DXF ScaleX= 1
DXF ScaleY= 10

--- STEEP HOLLOW BRANCH TRIB 1 1.p01 (plan) ---

Plan Title=Multiple Run
Short Identifier=Multiple
Geom File=g01
Flow File=f01
Subcritical Flow
K Sum by GR= 0
Std Step Tol= 0.01
Critical Tol= 0.01
Num of Std Step Trials= 20
Max Error Tol= 0.3
Flow Tol Ratio= 0.001
Split Flow NTrial= 30
Split Flow Tol= 0.02
Split Flow Ratio= 0.02
Log Output Level= 0
Friction Slope Method= 1
Unsteady Friction Slope Method= 2
Unsteady Bridges Friction Slope Method= 1
Parabolic Critical Depth
Global Vel Dist=  1 , 1 , 1
Global Log Level= 0
CheckData=True
Encroach Param= -1, 0, 0, 0
BEGIN DESCRIPTION:
Multiple Run
END DESCRIPTION:

--- STEEP HOLLOW BRANCH TRIB 1 1.f01 (steady flow) ---

Flow Title=Multiple
Program Version=4.10
Number of Profiles= 7
Profile Names=10-year,25-year,50-year,1pct_min,100-year,1pct_plu,500-year
River Rch & RM=STEEP HOLLOW BRA,Reach-1         ,2990
     247     318     373     323     436     590     596
Boundary for River Rch & Prof#=STEEP HOLLOW BRA,Reach-1         , 1
Up Type= 0
Dn Type= 3
Dn Slope=0.01
Boundary for River Rch & Prof#=STEEP HOLLOW BRA,Reach-1         , 2
Up Type= 0
Dn Type= 3
Dn Slope=0.01
Boundary for River Rch & Prof#=STEEP HOLLOW BRA,Reach-1         , 3
Up Type= 0
Dn Type= 3
Dn Slope=0.01
Boundary for River Rch & Prof#=STEEP HOLLOW BRA,Reach-1         , 4
Up Type= 0
Dn Type= 3
Dn Slope=0.01
Boundary for River Rch & Prof#=STEEP HOLLOW BRA,Reach-1         , 5
Up Type= 0
Dn Type= 3
Dn Slope=0.01
Boundary for River Rch & Prof#=STEEP HOLLOW BRA,Reach-1         , 6
Up Type= 0
Dn Type= 3
Dn Slope=0.01
Boundary for River Rch & Prof#=STEEP HOLLOW BRA,Reach-1         , 7
Up Type= 0
Dn Type= 3
Dn Slope=0.01
DSS Import GetInterval= 0
DSS Import GetPeak= 0
DSS Import FillOption= 0

--- STEEP HOLLOW BRANCH TRIB 1 1.g01 (geometry) ---

Geom Title=Existing Conditions
Program Version=4.10

River Reach=STEEP HOLLOW BRA,Reach-1
Reach XY= 30
      3576911.71     10239508.16      3576935.57     10239557.91
      3576940.25     10239647.27      3577019.27     10239736.87
      3577154.42     10239800.68       3577135.1     10239900.61
      3577205.12     10240083.38      3577276.16     10240070.83
      3577274.69     10240145.76      3577316.06     10240216.96
      3577382.25     10240168.84      3577419.74     10240201.89
      3577441.79      10240316.5      3577403.32     10240391.45
      3577506.08      10240438.5      3577500.06     10240509.83
      3577474.57     10240551.93       3577502.3      10240616.6
      3577572.81     10240607.63      3577587.16     10240667.25
      3577655.52     10240748.22      3577824.23     10240876.58
      3577836.39     10240983.44      3577971.21     10240992.27
      3578013.06     10241140.73      3578143.05     10241218.01
      3578157.74     10241283.91      3578212.67     10241361.48
      3578360.32     10241462.38      3578392.11     10241601.64

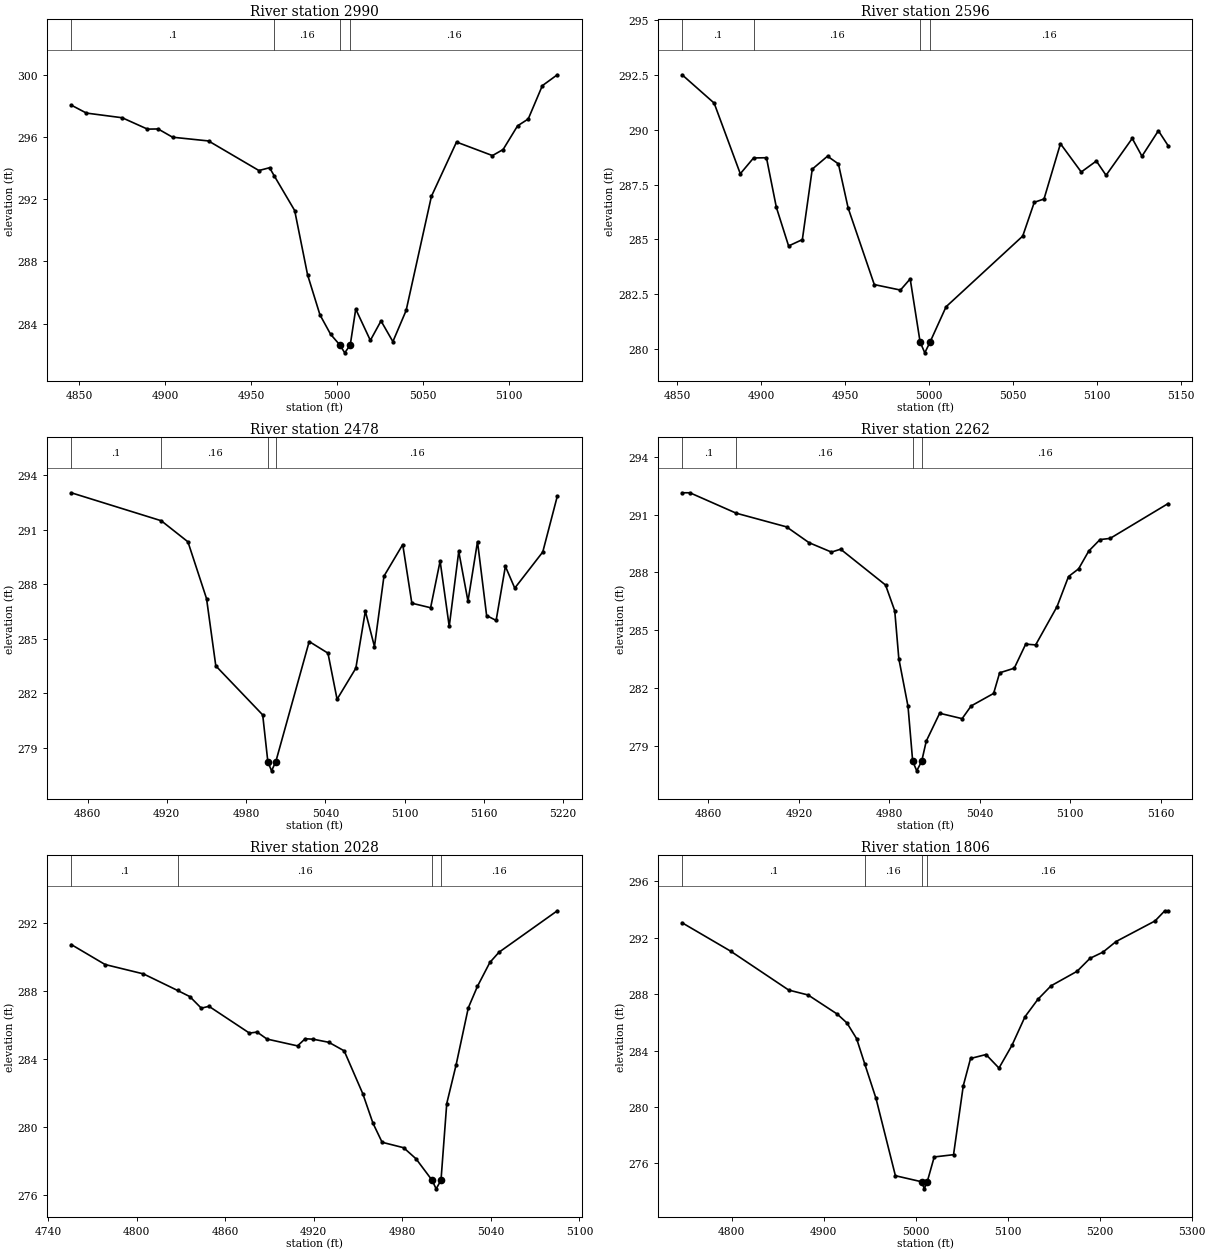
Type RM Length L Ch R = 1 ,2990    ,394,394,394
BEGIN DESCRIPTION:
UNT05250 IN WICK 16.0
END DESCRIPTION:
XS GIS Cut Line= 2
      3576831.42     10239752.88      3577059.15     10239585.53
#Sta/Elev= 30
  4845.4  298.04  4854.2  297.53    4875  297.23  4889.7   296.5  4895.9  296.51
  4904.3  295.98  4925.2  295.74  4954.5  293.84  4960.7  294.02  4963.3  293.52
  4975.3  291.27  4982.8  287.14    4990  284.57  4996.2  283.32  5001.6  282.63
  5004.4  282.13  5007.6  282.63  5010.8  284.94  5019.3  282.93  5025.5  284.18
  5032.4  282.85  5040.1  284.85  5054.8  292.18  5069.4  295.67  5090.3   294.8
  5096.5  295.19  5104.9  296.71  5111.1  297.15  5119.3  299.29    5128  299.99
#Mann= 4 ,-1 , 0
  4845.4      .1       0  4963.3     .16       0  5001.6     .07       0
  5007.6     .16       0
Bank Sta=5001.6,5007.6
XS Rating Curve= 0 ,0
Exp/Cntr=0.3,0.1

Type RM Length L Ch R = 1 ,2596    ,118,118,118
BEGIN DESCRIPTION:
Mapping XS ba8b51d5
END DESCRIPTION:
XS GIS Cut Line= 2
      3577017.57      10240004.6       3577266.6     10239856.38
#Sta/Elev= 30
  4852.8   292.5  4871.9  291.21  4887.5  287.99  4895.4  288.71  4903.1  288.72
    4909  286.46  4916.3   284.7  4924.5  284.99  4930.4   288.2  4939.5  288.79
    4946  288.44  4951.8  286.43  4967.4  282.94    4983  282.69  4988.8   283.2
  4994.7  280.33  4997.5  279.83  5000.7  280.33  5010.2  281.93  5055.9  285.15
  5062.8  286.69  5068.6  286.84  5078.4  289.36  5090.8  288.07  5099.8  288.57
  5105.6  287.92  5121.2   289.6    5127  288.79  5136.8  289.95  5142.6  289.27
#Mann= 4 ,-1 , 0
  4852.8      .1       0  4895.4     .16       0  4994.7     .07       0
  5000.7     .16       0
Bank Sta=4994.7,5000.7
XS Rating Curve= 0 ,0
Exp/Cntr=0.3,0.1

Type RM Length L Ch R = 1 ,2478    ,216,216,216
BEGIN DESCRIPTION:
Mapping XS 9915f34f
END DESCRIPTION:
XS GIS Cut Line= 2
      3577081.49     10240145.72      3577337.44     10239881.45
#Sta/Elev= 30
  4847.7  293.04  4915.8   291.5    4936  290.34  4950.1  287.21  4957.1  283.51
  4992.6  280.81  4996.5  278.23  4999.3  277.73  5002.5  278.23  5027.8  284.85
    5042  284.21  5048.9  281.67  5063.1  283.38  5070.3  286.52  5077.2  284.57
  5084.4  288.45  5098.6  290.19  5105.5  286.96  5119.7  286.71  5126.9  289.28
  5133.8  285.68    5141  289.81    5148  287.07  5155.2  290.35  5162.1  286.28
  5169.3  286.01  5176.3  288.99  5183.4  287.79  5204.6  289.78  5215.6  292.85
#Mann= 4 ,-1 , 0
  4847.7      .1       0  4915.8     .16       0  4996.5     .07       0
  5002.5     .16       0
Bank Sta=4996.5,5002.5
XS Rating Curve= 0 ,0
Exp/Cntr=0.3,0.1

Type RM Length L Ch R = 1 ,2262    ,234,234,234
BEGIN DESCRIPTION:
UNT05250 IN WICK 15.0
END DESCRIPTION:
XS GIS Cut Line= 3
       3577148.5     10240244.85      3577323.63     10240124.81
      3577396.46     10240042.13
#Sta/Elev= 30
  4842.5  292.13  4847.7  292.13  4878.4  291.07  4911.8  290.36  4926.7  289.54
  4941.6  289.05  4947.7   289.2  4977.5  287.34  4983.6     286  4986.3  283.52
  4992.4  281.04  4995.5  278.19  4998.2  277.69  5001.5  278.19  5004.5  279.23
  5013.4  280.68  5028.3   280.4  5034.3  281.06  5049.2  281.71  5053.2  282.78
  5062.9  283.02  5070.5  284.27  5077.1  284.23  5091.3  286.22  5098.9  287.78
  5105.6  288.18  5112.3   289.1  5119.8   289.7  5126.5  289.76    5165  291.57
#Mann= 4 ,-1 , 0
  4842.5      .1       0  4878.4     .16       0  4995.5     .07       0
  5001.5     .16       0
Bank Sta=4995.5,5001.5
XS Rating Curve= 0 ,0
Exp/Cntr=0.3,0.1

Type RM Length L Ch R = 1 ,2028    ,222,222,222
BEGIN DESCRIPTION:
Mapping XS a4427047
END DESCRIPTION:
XS GIS Cut Line= 3
      3577205.42     10240313.45        3577382.     10240258.76
      3577497.62     10240172.17
#Sta/Elev= 30
  4755.7  290.71  4778.6  289.54  4804.6  288.99  4827.7  288.02    4836  287.66
  4843.8  286.98    4849  287.09  4876.4  285.52  4881.6  285.58  4888.3  285.17
    4909  284.77  4914.2  285.19  4919.7  285.16  4930.2  284.98  4940.6  284.48
  4953.2  281.97  4960.1  280.24  4966.3  279.12  4980.9   278.8  4989.3  278.15
  5000.2  276.89  5002.9  276.39  5006.2  276.89  5010.1  281.39  5016.4  283.64
  5024.7     287  5030.9  288.26  5039.3  289.66  5045.5  290.26    5085  292.69
#Mann= 4 ,-1 , 0
  4755.7      .1       0  4827.7     .16       0  5000.2     .07       0
  5006.2     .16       0
Bank Sta=5000.2,5006.2
XS Rating Curve= 0 ,0
Exp/Cntr=0.3,0.1

Type RM Length L Ch R = 1 ,1806    ,588,588,588
BEGIN DESCRIPTION:
UNT05250 IN WICK 14.0
END DESCRIPTION:
XS GIS Cut Line= 3
      3577192.11     10240491.64      3577492.11     10240391.64
      3577642.14     10240241.61
#Sta/Elev= 30
    4746  293.06  4798.7  291.05  4861.9  288.29    4883  287.94  4914.6  286.59
  4925.2  285.96  4935.7  284.85  4944.6  283.05  4956.8  280.61  4977.9  275.13
  5006.5   274.7  5009.3   274.2  5012.5   274.7  5020.1  276.46  5041.1  276.62
  5051.7  281.51  5059.6  283.44  5076.4  283.72  5090.5  282.76  5104.6  284.37
  5118.8   286.4  5132.9  287.64  5147.1  288.59  5175.4  289.62  5189.5  290.54
  5203.6  290.98  5217.8  291.73  5260.2  293.19  5270.8  293.91  5274.4  293.91
#Mann= 4 ,-1 , 0
    4746      .1       0  4944.6     .16       0  5006.5     .07       0
  5012.5     .16       0
Bank Sta=5006.5,5012.5
XS Rating Curve= 0 ,0
Exp/Cntr=0.3,0.1

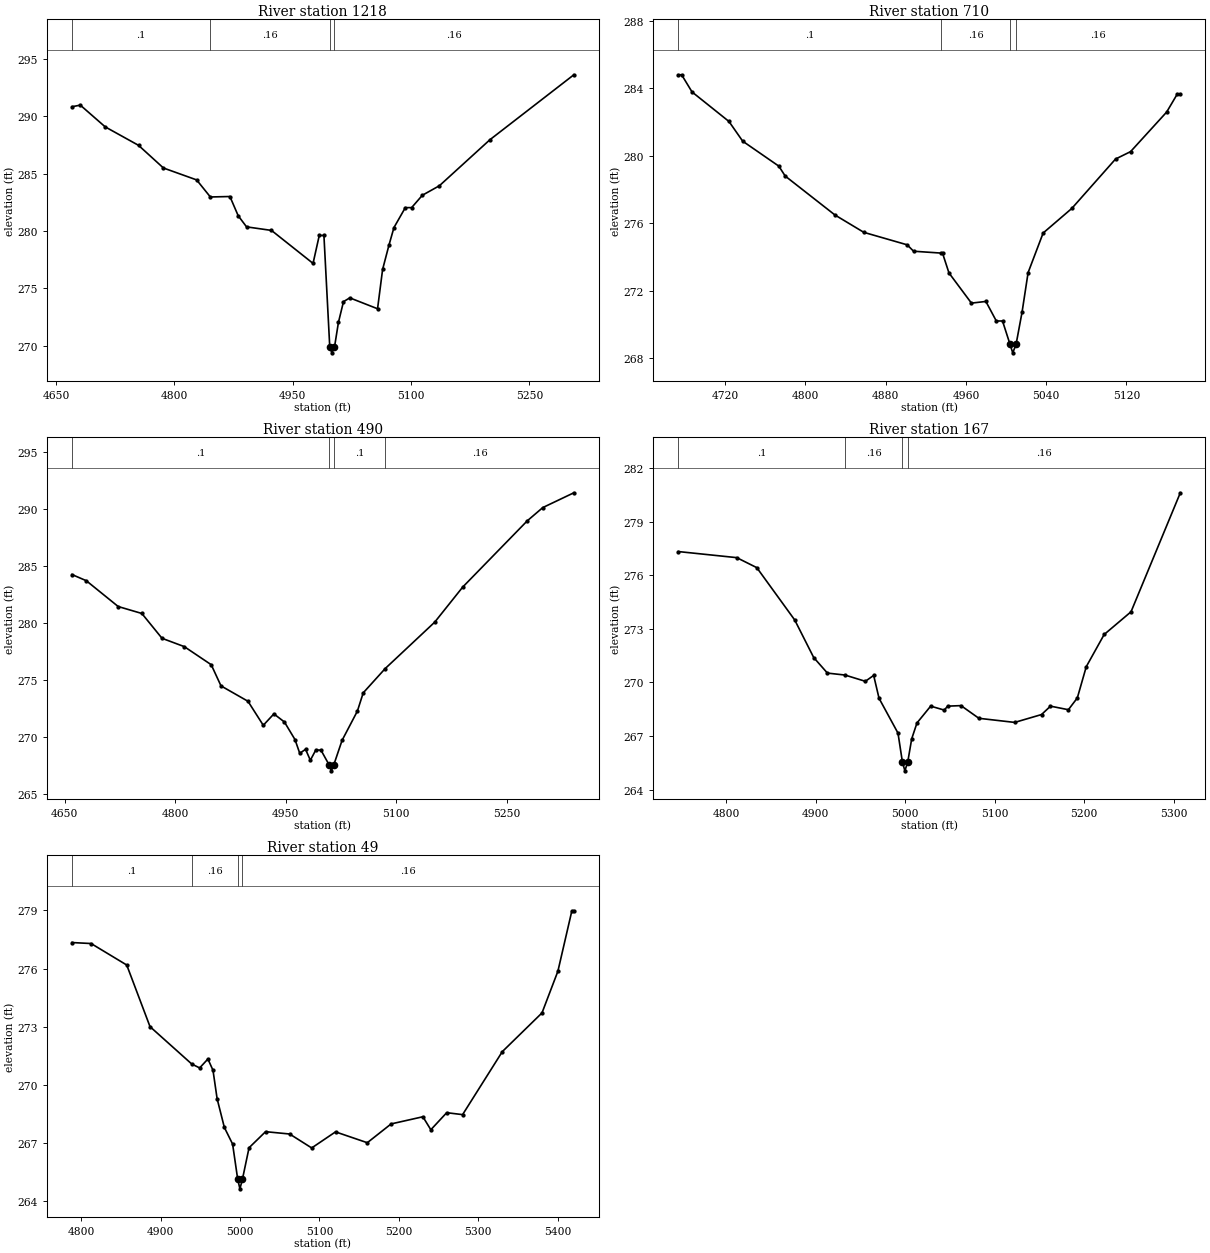
Type RM Length L Ch R = 1 ,1218    ,508,508,508
BEGIN DESCRIPTION:
UNT05250 IN WICK 13.0
END DESCRIPTION:
XS GIS Cut Line= 3
      3577392.08     10240891.65      3577692.11     10240791.64
      3577942.09     10240591.65
#Sta/Elev= 30
    4670  290.85  4680.6  290.99  4712.2  289.09  4754.4  287.48    4786   285.5
  4828.1  284.46  4845.5  282.97  4870.3  283.01  4880.8  281.33  4891.4  280.36
    4923  280.05  4975.7  277.17  4983.6  279.61  4989.5  279.61  4996.9  269.86
  4999.6  269.36  5002.9  269.86  5007.9  272.02  5014.3  273.83  5022.3  274.16
  5057.5  273.21  5063.9  276.64  5071.9  278.75  5078.3   280.3  5092.7  282.04
  5100.7  282.04  5114.3  283.12  5135.9  283.95    5200  287.97  5306.4  293.64
#Mann= 4 ,-1 , 0
    4670      .1       0  4845.5     .16       0  4996.9     .07       0
  5002.9     .16       0
Bank Sta=4996.9,5002.9
XS Rating Curve= 0 ,0
Exp/Cntr=0.3,0.1

Type RM Length L Ch R = 1 ,710     ,220,220,220
BEGIN DESCRIPTION:
UNT05250 IN WICK 12.0
END DESCRIPTION:
XS GIS Cut Line= 3
      3577792.09     10241341.66      3577992.11     10241091.64
      3578092.13     10240941.61
#Sta/Elev= 30
  4673.3  284.81  4676.5  284.81  4686.9  283.79  4723.7  282.04  4737.4  280.87
  4773.4  279.39  4779.8   278.8  4829.4  276.49  4858.2  275.46  4901.4  274.72
  4907.8  274.34    4935  274.23  4936.7  274.22  4943.1  273.05  4965.5  271.26
  4979.9  271.36  4990.3   270.2  4996.5   270.2    5004  268.81  5006.7  268.31
    5010  268.81    5016  270.73    5022  273.07    5037  275.42  5065.6  276.88
  5109.2  279.81  5124.2  280.25  5160.2   282.6  5170.8  283.67  5173.8  283.67
#Mann= 4 ,-1 , 0
  4673.3      .1       0    4935     .16       0    5004     .07       0
    5010     .16       0
Bank Sta=5004,5010
XS Rating Curve= 0 ,0
Exp/Cntr=0.3,0.1

Type RM Length L Ch R = 1 ,490     ,323,323,323
BEGIN DESCRIPTION:
UNT05250 IN WICK 12.0.a
END DESCRIPTION:
XS GIS Cut Line= 4
      3577888.76     10241435.25      3578048.45     10241346.61
      3578227.27     10241127.86       3578291.5      10240921.3
#Sta/Elev= 30
  4659.8  284.28  4679.2  283.74  4722.6  281.47  4754.7  280.86  4782.1  278.68
  4812.3  277.95  4848.9  276.36  4862.2   274.5  4898.8  273.15  4919.6  271.04
    4934  272.04  4948.3  271.33  4962.7  269.78  4969.1  268.58    4977  268.93
  4983.5  267.97  4990.9  268.87  4997.9  268.86  5009.2  267.54    5012  267.04
  5015.2  267.54  5026.6  269.72  5047.4  272.29  5055.3  273.89  5085.1  276.02
  5152.4   280.1  5190.4  283.18  5278.1     289  5299.1  290.16  5341.3  291.46
#Mann= 4 ,-1 , 0
  4659.8      .1       0  5009.2     .07       0  5015.2      .1       0
  5085.1     .16       0
Bank Sta=5009.2,5015.2
XS Rating Curve= 0 ,0
Exp/Cntr=0.3,0.1

Type RM Length L Ch R = 1 ,167     ,118,118,118
BEGIN DESCRIPTION:
UNT05250 IN WICK 11.0
END DESCRIPTION:
XS GIS Cut Line= 3
      3578136.92     10241585.74      3578393.45     10241424.27
      3578396.05      10241166.5
#Sta/Elev= 30
  4746.7  277.32  4811.9  276.98  4834.3  276.42  4876.7  273.49  4897.9  271.39
  4913.2  270.52  4932.9  270.41  4955.6  270.06  4964.9  270.39  4970.9  269.11
  4992.1  267.16    4997  265.55  4999.8  265.05    5003  265.55  5007.4  266.84
  5013.3  267.73  5028.6  268.67  5043.8  268.45  5047.6  268.67  5062.5   268.7
  5082.5  267.99  5122.5  267.76  5152.5   268.2  5162.5  268.67  5182.5  268.47
  5192.5  269.13  5202.5  270.88  5222.5  272.68  5252.5  273.95  5307.6  280.61
#Mann= 4 ,-1 , 0
  4746.7      .1       0  4932.9     .16       0    4997     .07       0
    5003     .16       0
Bank Sta=4997,5003
XS Rating Curve= 0 ,0
Exp/Cntr=0.3,0.1

Type RM Length L Ch R = 1 ,49      ,0,0,0
BEGIN DESCRIPTION:
UNT05250 IN WICK 11.0a
END DESCRIPTION:
XS GIS Cut Line= 3
      3578166.97     10241613.86      3578428.66     10241542.25
      3578429.97     10241181.57
#Sta/Elev= 30
  4788.3  277.34  4812.4  277.29  4857.3  276.18  4886.6     273  4939.2  271.07
  4949.1  270.87  4959.5  271.33  4965.9  270.75  4971.1  269.28  4980.2   267.8
  4990.6  266.94    4997  265.13  4999.8  264.63    5003  265.13  5011.3  266.75
  5032.1  267.58  5062.4  267.46  5090.2  266.74  5120.2  267.57  5160.2  267.01
  5190.2  267.98  5230.2  268.35  5240.2  267.68  5260.2  268.56  5280.2  268.46
  5330.2  271.71  5380.2  273.71  5400.2  275.86  5417.8  278.98  5420.3  278.98
#Mann= 4 ,-1 , 0
  4788.3      .1       0  4939.2     .16       0    4997     .07       0
    5003     .16       0
Bank Sta=4997,5003
XS Rating Curve= 0 ,0
Exp/Cntr=0.3,0.1

Chan Stop Cuts=-1
Use User Specified Reach Order=0
Composite Channel Slope=5