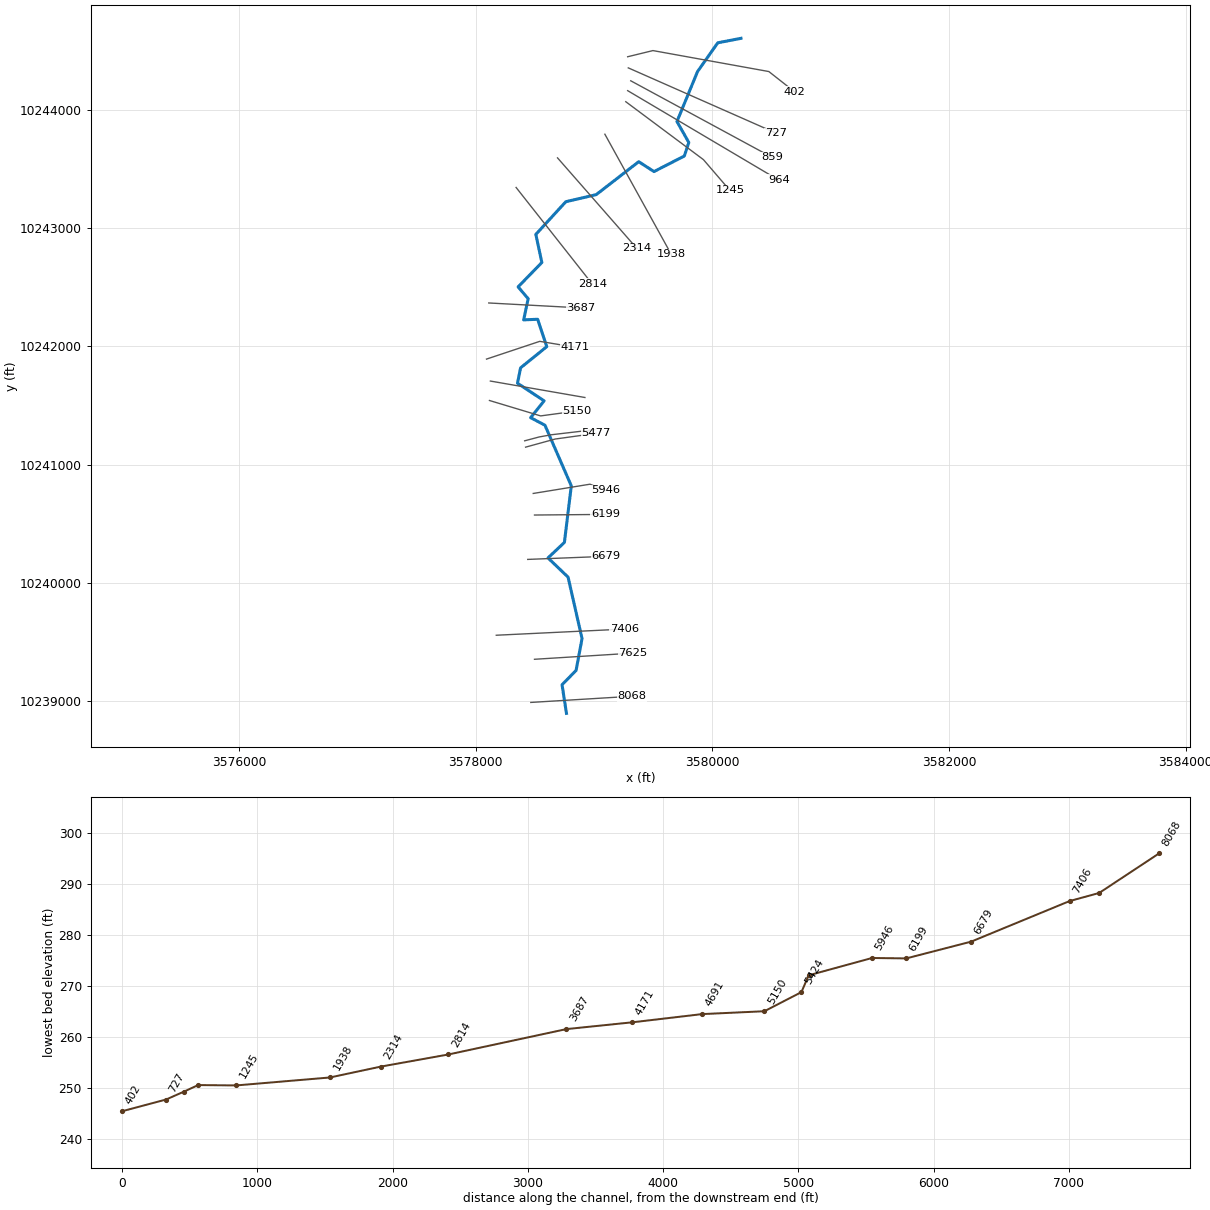
--- STEEPHOLLOWBRANCH.prj (project) ---

Proj Title=STEEP HOLLOW BRANCH TRIB 1
Current Plan=p01
Default Exp/Contr=0.3,0.1
English Units
Geom File=g01
Flow File=f01
Plan File=p01
Y Axis Title=Elevation
X Axis Title(PF)=Main Channel Distance
X Axis Title(XS)=Station
BEGIN DESCRIPTION:
UNT05250 IN WICK
END DESCRIPTION:
DSS Export Rating Curves= 0
DSS Export Rating Curve Sorted= 0
DSS Export Volume Flow Curves= 0
DXF OffsetX= 0
DXF OffsetY= 0
DXF ScaleX= 1
DXF ScaleY= 10

--- STEEPHOLLOWBRANCH.p01 (plan) ---

Plan Title=Multiple Run
Short Identifier=Multiple
Geom File=g01
Flow File=f01
Subcritical Flow
K Sum by GR= 0
Std Step Tol= 0.01
Critical Tol= 0.01
Num of Std Step Trials= 20
Max Error Tol= 0.3
Flow Tol Ratio= 0.001
Split Flow NTrial= 30
Split Flow Tol= 0.02
Split Flow Ratio= 0.02
Log Output Level= 0
Friction Slope Method= 1
Unsteady Friction Slope Method= 2
Unsteady Bridges Friction Slope Method= 1
Parabolic Critical Depth
Global Vel Dist=  1 , 1 , 1
Global Log Level= 0
CheckData=True
Encroach Param= -1, 0, 0, 0
BEGIN DESCRIPTION:
Multiple Run
END DESCRIPTION:

--- STEEPHOLLOWBRANCH.f01 (steady flow) ---

Flow Title=Multiple
Program Version=4.10
Number of Profiles= 7
Profile Names=10-year,25-year,50-year,1pct_min,100-year,1pct_plu,500-year
River Rch & RM=STEEPHOLLOWBRTR1,Reach-1         ,8068
     177     222     256     219     296     400     392
River Rch & RM=STEEPHOLLOWBRTR1,Reach-1         ,5150
     484     647     780     690     933    1262    1338
River Rch & RM=STEEPHOLLOWBRTR1,Reach-1         ,4691
     484     647     780     690     933    1262    1338
Boundary for River Rch & Prof#=STEEPHOLLOWBRTR1,Reach-1         , 1
Up Type= 0
Dn Type= 3
Dn Slope=0.005
Boundary for River Rch & Prof#=STEEPHOLLOWBRTR1,Reach-1         , 2
Up Type= 0
Dn Type= 3
Dn Slope=0.005
Boundary for River Rch & Prof#=STEEPHOLLOWBRTR1,Reach-1         , 3
Up Type= 0
Dn Type= 3
Dn Slope=0.005
Boundary for River Rch & Prof#=STEEPHOLLOWBRTR1,Reach-1         , 4
Up Type= 0
Dn Type= 3
Dn Slope=0.005
Boundary for River Rch & Prof#=STEEPHOLLOWBRTR1,Reach-1         , 5
Up Type= 0
Dn Type= 3
Dn Slope=0.005
Boundary for River Rch & Prof#=STEEPHOLLOWBRTR1,Reach-1         , 6
Up Type= 0
Dn Type= 3
Dn Slope=0.005
Boundary for River Rch & Prof#=STEEPHOLLOWBRTR1,Reach-1         , 7
Up Type= 0
Dn Type= 3
Dn Slope=0.005
DSS Import GetInterval= 0
DSS Import GetPeak= 0
DSS Import FillOption= 0

--- STEEPHOLLOWBRANCH.g01 (geometry) ---

Geom Title=Existing Conditions
Program Version=4.10

River Reach=STEEPHOLLOWBRTR1,Reach-1
Reach XY= 30
      3578767.56     10238898.43      3578730.24     10239140.26
      3578848.83     10239261.33      3578899.18     10239530.43
      3578781.12     10240049.53      3578611.64     10240211.79
      3578750.16     10240342.67      3578808.44     10240820.79
      3578585.75      10241333.1      3578464.83     10241396.75
      3578578.79     10241539.19      3578353.96     10241687.63
      3578380.11      10241817.7      3578601.04     10241996.61
      3578524.06     10242228.13      3578406.01     10242223.15
      3578444.04     10242401.81      3578359.07     10242501.76
      3578559.71      10242707.8      3578508.81     10242945.04
      3578762.19     10243221.29      3579018.77     10243280.97
      3579378.22     10243559.39      3579507.11     10243475.99
       3579763.3     10243607.25      3579801.25     10243721.64
      3579701.07     10243898.89      3579874.93     10244320.66
      3580045.97     10244563.97      3580242.11     10244601.64

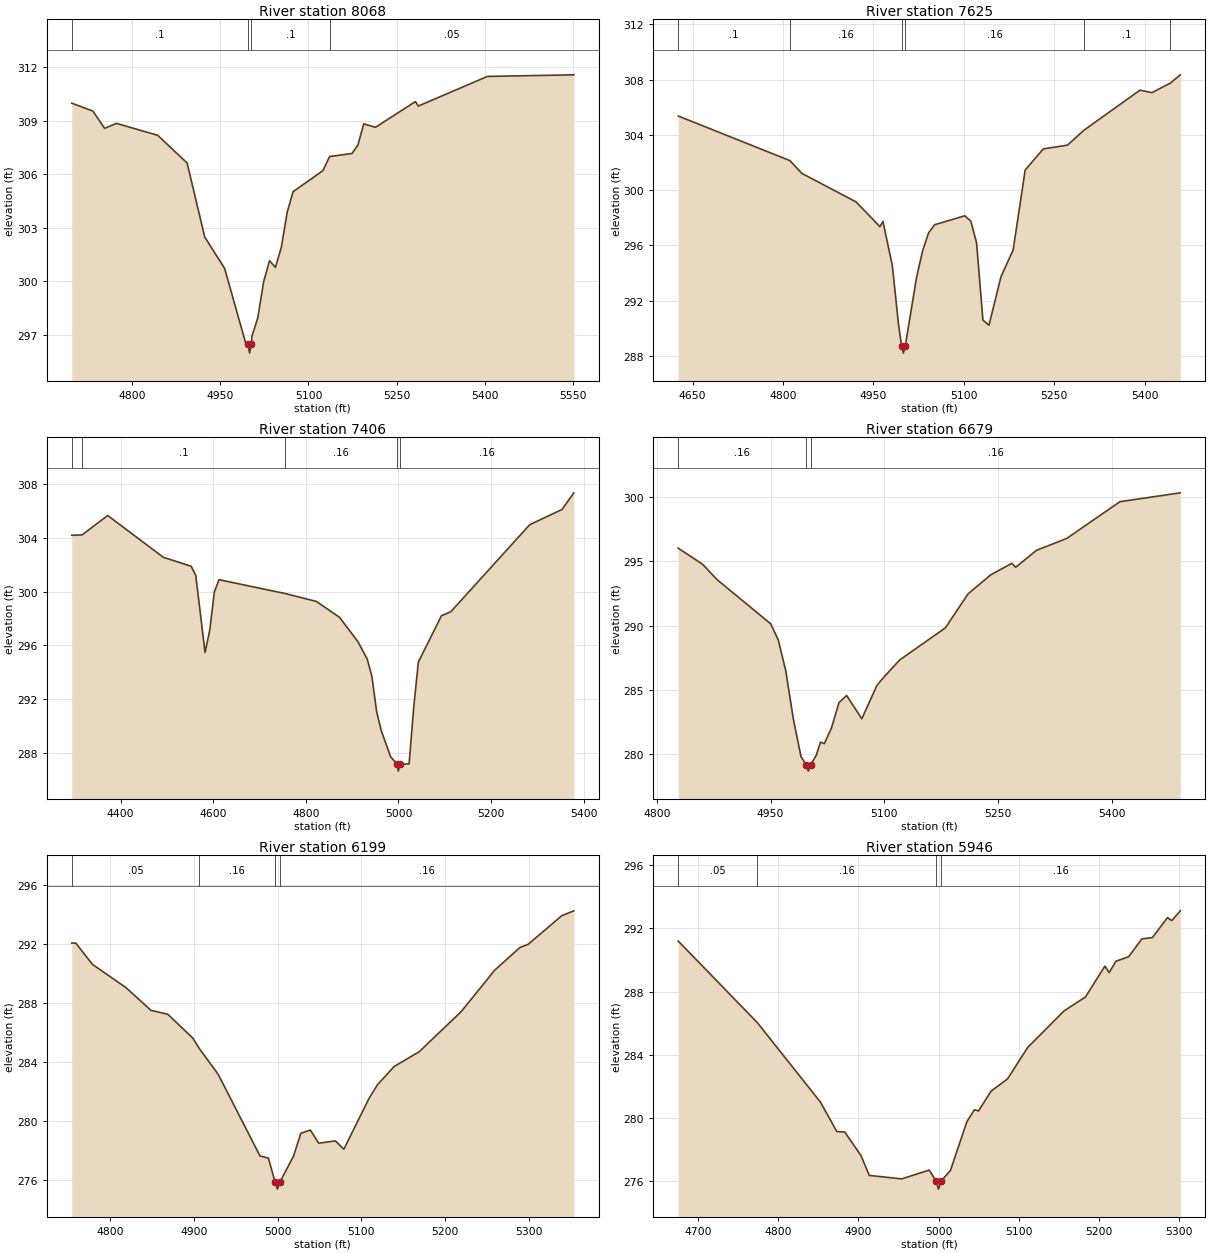
Type RM Length L Ch R = 1 ,8068    ,443,443,443
BEGIN DESCRIPTION:
UNT05251 IN WICK 7.0
END DESCRIPTION:
XS GIS Cut Line= 2
      3578466.29      10238990.9       3579318.8     10239042.88
#Sta/Elev= 30
  4697.3  309.98  4733.2  309.54  4753.2  308.57  4773.3  308.85  4843.4  308.18
  4893.5  306.63  4923.5  302.48  4957.3  300.72  4993.7  296.47    4997  296.47
  4999.8  295.97    5003  296.47  5003.7  296.91  5013.7  297.94  5023.7  299.97
  5033.7  301.15  5043.8  300.78  5053.8   301.9  5063.8  303.87  5073.8  305.02
  5124.6   306.2  5135.9  306.99    5174  307.16    5184  307.63    5194  308.82
  5214.1  308.63  5281.9  310.07  5286.9  309.82  5404.4  311.48  5551.4  311.57
#Mann= 4 ,-1 , 0
  4697.3      .1       0    4997     .07       0    5003      .1       0
  5135.9     .05       0
Bank Sta=4997,5003
XS Rating Curve= 0 ,0
Exp/Cntr=0.3,0.1

Type RM Length L Ch R = 1 ,7625    ,219,219,219
BEGIN DESCRIPTION:
UNT05251 IN WICK 6.0
END DESCRIPTION:
XS GIS Cut Line= 2
      3578497.52     10239355.48        3579329.     10239407.45
#Sta/Elev= 30
  4626.3  305.37  4811.7  302.14  4831.3  301.22  4921.5  299.15    4961  297.36
    4966  297.74  4981.6  294.54  4991.6  290.37    4997  288.71  4999.8  288.21
    5003  288.71  5021.7  293.68  5031.7   295.6  5041.7  296.91  5051.7   297.5
  5101.8  298.15  5111.8  297.76  5121.3   296.2  5131.9   290.6  5141.9  290.23
  5161.9  293.75    5182  295.67    5202  301.46  5232.1  302.99  5272.1  303.26
  5299.8  304.35  5392.4  307.24  5412.4  307.06  5442.8  307.75  5459.4  308.35
#Mann= 6 ,-1 , 0
  4626.3      .1       0  4811.7     .16       0    4997     .07       0
    5003     .16       0  5299.8      .1       0  5442.8     .05       0
Bank Sta=4997,5003
XS Rating Curve= 0 ,0
Exp/Cntr=0.3,0.1

Type RM Length L Ch R = 1 ,7406    ,727,727,727
BEGIN DESCRIPTION:
UNT05251 IN WICK 5.0
END DESCRIPTION:
XS GIS Cut Line= 2
      3578174.59     10239558.61      3579257.54     10239610.67
#Sta/Elev= 30
  4294.5  304.19  4316.5  304.21  4372.1  305.66  4492.2  302.55  4552.3  301.88
  4562.3  301.19  4582.3  295.46  4592.4   297.1  4602.4  299.96  4612.4  300.88
  4755.1  299.85  4822.6  299.26  4872.7  298.08  4912.7  296.25  4932.8  294.94
  4942.8  293.64  4952.8  291.06  4962.8  289.64  4982.8  287.71    4997  287.12
  4999.8  286.62    5003  287.12  5022.9  287.16  5032.9  291.35  5042.9  294.74
  5092.9   298.2    5113  298.49  5283.2  304.97  5353.2  306.11  5378.7  307.35
#Mann= 5 ,-1 , 0
  4294.5     .05       0  4316.5      .1       0  4755.1     .16       0
    4997     .07       0    5003     .16       0
Bank Sta=4997,5003
XS Rating Curve= 0 ,0
Exp/Cntr=0.3,0.1

Type RM Length L Ch R = 1 ,6679    ,480,480,480
BEGIN DESCRIPTION:
UNT05251 IN WICK 4.0
END DESCRIPTION:
XS GIS Cut Line= 2
       3578440.3     10240199.23      3579101.68     10240225.27
#Sta/Elev= 30
  4828.3  296.03  4860.1  294.79  4880.1  293.55  4950.2  290.14  4960.2  288.88
  4970.2  286.44  4980.2  282.68  4990.2  279.79    4997  279.17  4999.8  278.67
    5003  279.17  5010.2  279.89  5015.9  280.93  5020.9  280.81  5030.3  282.03
  5040.3  284.01  5050.3  284.56  5070.3  282.75  5090.3  285.35  5100.3  286.05
  5120.3  287.33  5180.4  289.82  5210.4  292.47  5240.4  293.96  5268.1  294.85
  5273.1  294.54  5300.5  295.86  5340.5  296.79  5410.6  299.65  5490.2  300.34
#Mann= 3 ,-1 , 0
  4828.3     .16       0    4997     .07       0    5003     .16       0
Bank Sta=4997,5003
XS Rating Curve= 0 ,0
Exp/Cntr=0.3,0.1

Type RM Length L Ch R = 1 ,6199    ,253,253,253
BEGIN DESCRIPTION:
UNT05251 IN WICK 3.0
END DESCRIPTION:
XS GIS Cut Line= 2
      3578497.54     10240574.23      3579096.52     10240579.44
#Sta/Elev= 30
  4754.5  292.08  4759.3  292.08  4779.1  290.64  4819.1  289.06  4849.1  287.51
  4869.1  287.25  4899.1  285.62  4906.7  284.92  4929.1  283.18  4979.1  277.63
  4989.1  277.48    4997  275.88  4999.8  275.38    5003  275.88  5019.1  277.62
  5027.8  279.17  5039.1  279.39  5049.1   278.5  5069.1  278.65  5079.1  278.09
  5109.1  281.53  5119.1  282.46  5139.1   283.7  5169.1  284.71  5219.1  287.43
  5259.1  290.24  5289.1  291.78  5299.1     292  5339.1  293.94  5353.5  294.27
#Mann= 4 ,-1 , 0
  4754.5     .05       0  4906.7     .16       0    4997     .07       0
    5003     .16       0
Bank Sta=4997,5003
XS Rating Curve= 0 ,0
Exp/Cntr=0.3,0.1

Type RM Length L Ch R = 1 ,5946    ,469,469,469
BEGIN DESCRIPTION:
UNT05251 IN WICK 2.0
END DESCRIPTION:
XS GIS Cut Line= 3
      3578487.09     10240756.52       3578966.3     10240834.65
      3579096.53     10240782.56
#Sta/Elev= 30
  4675.4   291.2  4773.9  286.03  4852.7  280.98    4873  279.12  4883.1  279.08
  4903.4  277.57  4913.5  276.33    4954  276.11  4988.2  276.67    4997  275.96
  4999.8  275.46    5003  275.96  5014.8  276.66  5035.1  279.73  5044.6   280.5
  5049.7  280.42  5065.5  281.69  5085.8  282.45  5111.1  284.46  5156.3  286.77
  5182.9  287.65  5207.2  289.61  5212.5   289.2    5221  289.92  5236.8  290.21
  5253.3  291.34  5266.4  291.42  5285.2  292.69  5290.6   292.5  5301.2  293.12
#Mann= 4 ,-1 , 0
  4675.4     .05       0  4773.9     .16       0    4997     .07       0
    5003     .16       0
Bank Sta=4997,5003
XS Rating Curve= 0 ,0
Exp/Cntr=0.3,0.1

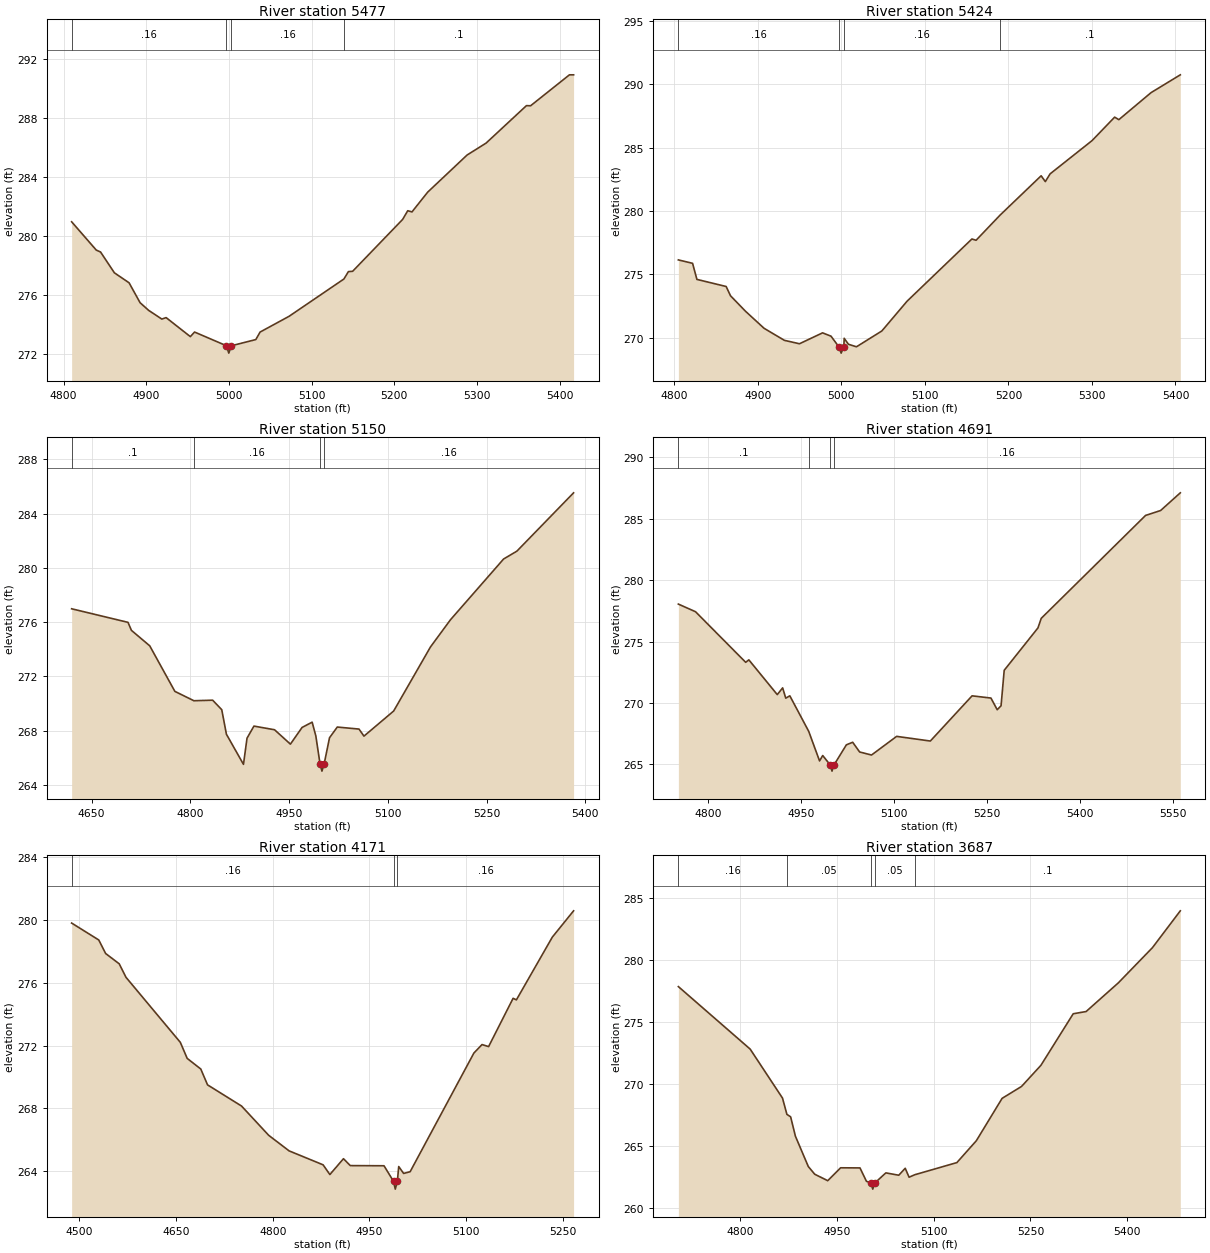
Type RM Length L Ch R = 1 ,5477    ,53,53,53
BEGIN DESCRIPTION:
Mapping XS f47e2c7d
END DESCRIPTION:
XS GIS Cut Line= 3
      3578422.24     10241147.68      3578672.25     10241216.26
      3579016.91     10241264.01
#Sta/Elev= 30
  4809.7  280.97  4839.5  279.05  4844.7  278.92  4861.4  277.51  4879.2  276.83
  4892.5  275.48  4902.9  274.96  4918.8  274.37    4924  274.47  4953.3  273.18
  4958.4  273.49    4997  272.56  4999.8  272.06    5003  272.56  5032.5  272.98
  5037.7  273.49  5072.8  274.56  5139.1  277.09  5144.5  277.59  5149.6  277.61
  5210.1  281.13  5216.3  281.72  5221.4  281.64  5240.4  282.98  5288.1   285.5
  5311.1  286.31  5359.9  288.85  5364.9  288.84  5411.9  290.94  5416.9  290.94
#Mann= 4 ,-1 , 0
  4809.7     .16       0    4997     .07       0    5003     .16       0
  5139.1      .1       0
Bank Sta=4997,5003
XS Rating Curve= 0 ,0
Exp/Cntr=0.3,0.1

Type RM Length L Ch R = 1 ,5424    ,274,274,274
BEGIN DESCRIPTION:
Mapping XS ab5035d8
END DESCRIPTION:
XS GIS Cut Line= 4
      3578414.51     10241201.24      3578537.15      10241233.8
      3578639.14     10241252.25      3579006.95     10241295.65
#Sta/Elev= 30
  4804.9  276.13  4821.9  275.86  4827.1  274.59  4862.1  274.03  4867.3   273.3
  4885.2  272.08  4907.5  270.73  4931.8  269.78  4949.9  269.51  4977.5  270.37
  4987.6  270.11    4997  269.27  4999.8  268.77    5003  269.27  5003.4  269.94
  5008.5  269.47  5018.1  269.27  5048.5  270.52  5078.7  272.87  5156.3  277.78
  5161.3  277.68  5190.1  279.67  5239.2  282.77  5244.2  282.31  5249.9  282.92
  5300.2  285.55  5327.2   287.4  5332.2   287.2  5370.7  289.33  5405.8  290.74
#Mann= 4 ,-1 , 0
  4804.9     .16       0    4997     .07       0    5003     .16       0
  5190.1      .1       0
Bank Sta=4997,5003
XS Rating Curve= 0 ,0
Exp/Cntr=0.3,0.1

Type RM Length L Ch R = 1 ,5150    ,459,459,459
BEGIN DESCRIPTION:
UNT05251 IN WICK 1.0
END DESCRIPTION:
XS GIS Cut Line= 3
      3578117.01     10241541.88      3578549.27     10241411.68
      3578857.44     10241453.29
#Sta/Elev= 30
  4619.6  276.99  4705.2  275.99  4710.4   275.4  4738.2  274.26  4776.4   270.9
  4805.3  270.21  4833.8  270.25  4847.6  269.55  4854.7  267.74  4880.6  265.52
    4886  267.45  4896.5  268.34  4927.8  268.07  4951.9  267.01  4969.6  268.24
  4984.9  268.63  4990.5  267.62    4997  265.52  4999.8  265.02    5003  265.52
  5011.3  267.48  5023.1  268.27  5056.1  268.12  5063.6   267.6  5108.7  269.45
  5164.7  274.18    5195  276.18  5275.7  280.66  5295.9  281.24    5382  285.54
#Mann= 4 ,-1 , 0
  4619.6      .1       0  4805.3     .16       0    4997     .07       0
    5003     .16       0
#XS Ineff= 2 , 0
       0  4984.9   268.6               0
Permanent Ineff=
       T       F
Bank Sta=4997,5003
XS Rating Curve= 0 ,0
Exp/Cntr=0.3,0.1

Type RM Length L Ch R = 1 ,4691    ,520,520,520
BEGIN DESCRIPTION:
UNT05250 IN WICK 10.0
END DESCRIPTION:
XS GIS Cut Line= 2
       3578124.8     10241706.11      3578923.42     10241567.22
#Sta/Elev= 30
  4751.7  278.06  4779.4  277.44  4860.4  273.32  4865.5  273.52  4911.4  270.69
  4920.1  271.24  4925.1   270.4  4931.7  270.59  4962.2   267.7  4979.7  265.29
  4984.8  265.73    4997  264.96  4999.8  264.46    5003  264.96    5023   266.6
  5033.2  266.81  5044.4  266.02  5063.6  265.77  5104.2  267.29  5158.6  266.91
    5226  270.59  5256.5  270.41  5266.6  269.46  5272.8  269.78  5277.9  272.67
  5332.4  276.12  5337.7   276.9  5506.2  285.28  5530.5  285.68  5562.3  287.12
#Mann= 4 ,-1 , 0
  4751.7      .1       0  4962.2     .16       0    4997     .07       0
    5003     .16       0
Bank Sta=4997,5003
XS Rating Curve= 0 ,0
Exp/Cntr=0.3,0.1

Type RM Length L Ch R = 1 ,4171    ,484,484,484
BEGIN DESCRIPTION:
UNT05250 IN WICK 9.0
END DESCRIPTION:
XS GIS Cut Line= 3
      3578092.12     10241891.65      3578542.11     10242041.64
      3578842.14     10241991.64
#Sta/Elev= 30
  4488.1  279.81  4530.2  278.73  4540.8  277.87  4561.9  277.21  4572.4  276.35
  4656.7   272.2  4667.3  271.18  4688.4   270.5  4698.9  269.49  4751.6  268.14
  4793.8  266.27  4825.4  265.28  4878.1  264.39  4888.6  263.77  4909.7  264.78
  4920.3  264.34  4972.6  264.33  4987.3  263.34  4990.1  262.84  4993.3  263.34
  4995.4  264.28    5003  263.84  5013.1  263.95    5112  271.52  5124.6  272.06
  5134.8  271.93  5172.8  275.01  5177.9  274.91  5233.6  278.91  5266.6  280.59
#Mann= 3 ,-1 , 0
  4488.1     .16       0  4987.3     .07       0  4993.3     .16       0
Bank Sta=4987.3,4993.3
XS Rating Curve= 0 ,0
Exp/Cntr=0.3,0.1

Type RM Length L Ch R = 1 ,3687    ,873,873,873
BEGIN DESCRIPTION:
UNT05250 IN WICK 8.0
END DESCRIPTION:
XS GIS Cut Line= 2
      3578110.98     10242365.83      3578887.87     10242324.21
#Sta/Elev= 30
  4704.4  277.85  4815.7  272.81  4865.8  268.86  4872.6  267.55  4878.4  267.35
  4885.8  265.79  4905.8  263.34  4915.8  262.72  4935.9   262.2  4955.9  263.24
  4985.9  263.23  4995.9  262.15    5003  262.02  5005.7  261.52    5009  262.02
    5026  262.83    5046  262.64    5056   263.2    5062  262.48  5070.8  262.68
  5136.1  263.66  5166.2  265.42  5206.2  268.84  5236.3   269.8  5266.3   271.5
  5316.4  275.66  5336.4  275.84  5386.5  278.16  5439.2  280.99  5482.4  283.96
#Mann= 5 ,-1 , 0
  4704.4     .16       0  4872.6     .05       0    5003     .03       0
    5009     .05       0  5070.8      .1       0
Bank Sta=5003,5009
XS Rating Curve= 0 ,0
Exp/Cntr=0.3,0.1

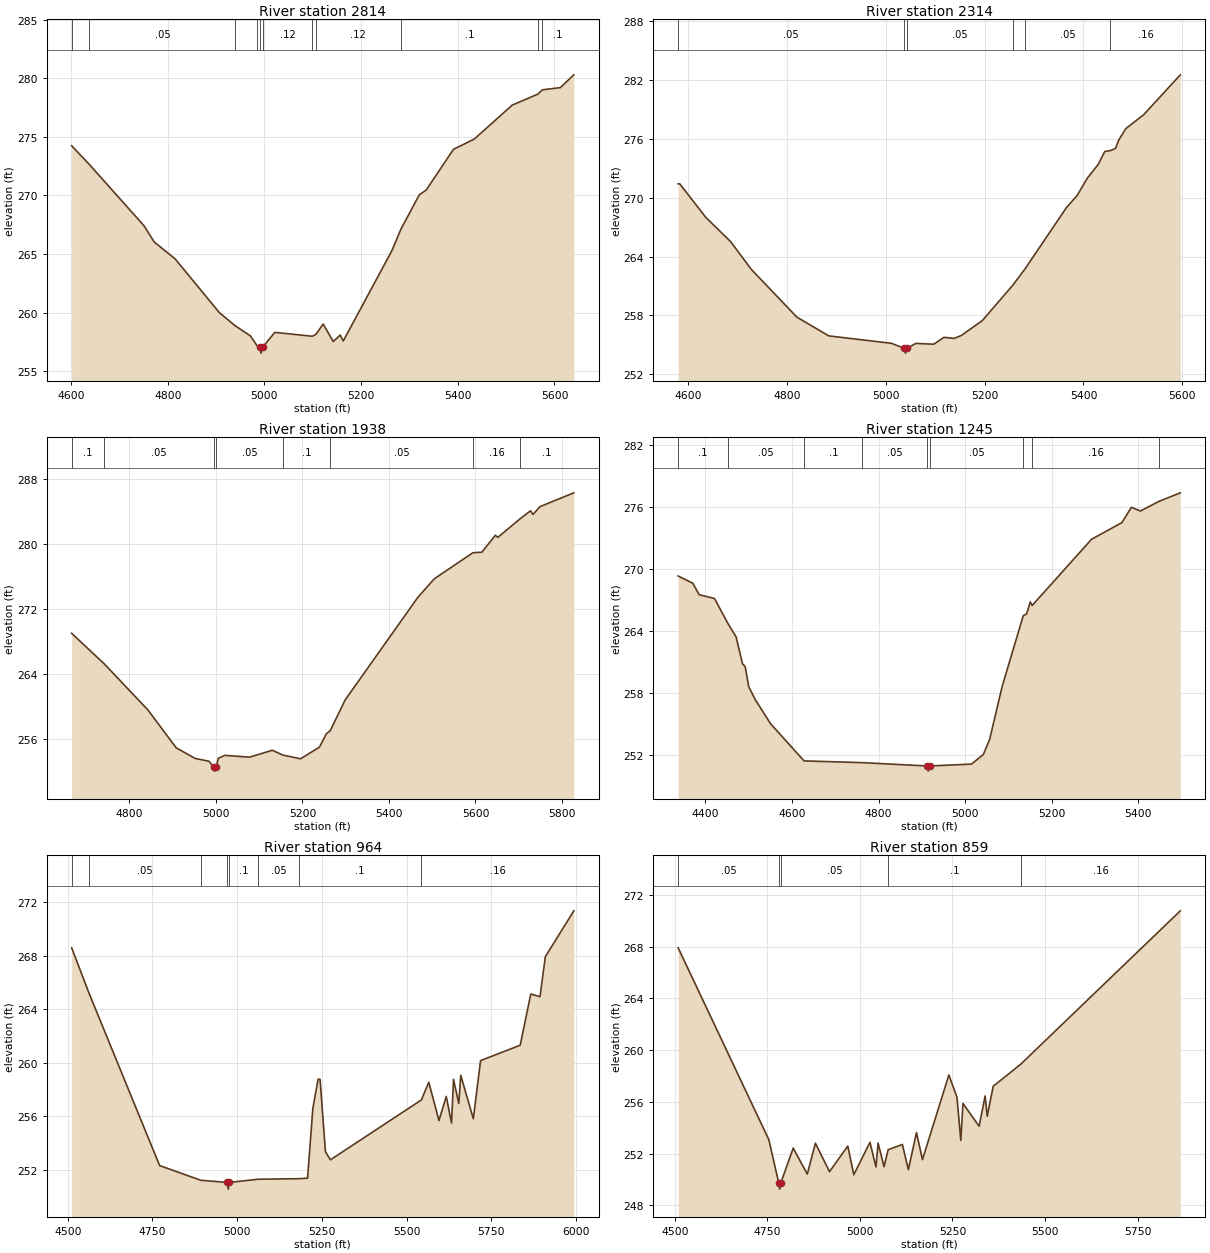
Type RM Length L Ch R = 1 ,2814    ,500,500,500
BEGIN DESCRIPTION:
UNT05250 IN WICK 6.0
END DESCRIPTION:
XS GIS Cut Line= 2
       3578342.1     10243341.65      3578985.52      10242526.1
#Sta/Elev= 30
  4601.3  274.24  4637.7  272.65  4751.2   267.4    4772  266.03  4815.4  264.58
    4907  259.99  4940.1  258.86  4970.8  258.02  4985.1  257.16  4990.3  257.04
  4993.1  256.54  4996.3  257.04  5021.6  258.31  5099.2  257.98  5106.5  258.14
  5121.6  259.02  5142.4  257.53  5156.8  258.08  5163.2  257.58  5263.7  265.28
  5282.3  267.11  5320.4  270.05  5334.8  270.46    5391  273.93  5434.2  274.81
  5512.8  277.71  5565.6  278.64  5575.1  279.01  5612.2   279.2  5640.1  280.29
#Mann= 11 ,-1 , 0
  4601.3     .16       0  4637.7     .05       0  4940.1     .16       0
  4985.1     .12       0  4990.3     .07       0  4996.3     .12       0
  5099.2     .05       0  5106.5     .12       0  5282.3      .1       0
  5565.6     .16       0  5575.1      .1       0
Bank Sta=4990.3,4996.3
XS Rating Curve= 0 ,0
Exp/Cntr=0.3,0.1

Type RM Length L Ch R = 1 ,2314    ,376,376,376
BEGIN DESCRIPTION:
UNT05250 IN WICK 5.0
END DESCRIPTION:
XS GIS Cut Line= 2
      3578692.13     10243591.62      3579362.52     10242826.59
#Sta/Elev= 30
    4579  271.43  4582.3  271.43  4635.4  267.99  4685.3  265.54  4727.5  262.69
  4819.6  257.83  4884.1  255.92  5011.3  255.16  5036.7  254.66  5039.5  254.16
  5042.7  254.66  5060.6  255.15  5096.7  255.07  5117.5  255.77  5138.4  255.66
  5152.7  255.96  5195.4  257.49  5257.1   261.1  5281.9  262.77  5365.2  268.98
  5387.1  270.23  5407.9  272.01  5429.8   273.4  5443.2  274.73  5454.7  274.82
  5464.9  275.04  5471.5   275.9  5485.8  277.06  5521.8  278.47  5596.2  282.55
#Mann= 6 ,-1 , 0
    4579     .05       0  5036.7     .03       0  5042.7     .05       0
  5257.1      .1       0  5281.9     .05       0  5454.7     .16       0
Bank Sta=5036.7,5042.7
XS Rating Curve= 0 ,0
Exp/Cntr=0.3,0.1

Type RM Length L Ch R = 1 ,1938    ,693,693,693
BEGIN DESCRIPTION:
UNT05250 IN WICK 4.0
END DESCRIPTION:
XS GIS Cut Line= 2
      3579092.11     10243791.64       3579653.6     10242775.56
#Sta/Elev= 30
  4666.5     269  4741.7  265.25  4842.9  259.56  4908.2   254.9  4952.1  253.59
  4983.8  253.25  4994.8  252.53  4997.6  252.03  5000.8  252.53  5005.6  253.62
  5020.7  253.97  5077.8  253.75  5130.5   254.6  5154.5  254.01  5195.7  253.55
  5239.3  254.98  5255.3  256.63  5264.4  257.02  5298.8   260.8  5467.2  273.46
    5505  275.72    5594  278.92  5614.8  278.99    5646  281.08  5651.7  280.81
  5703.8  283.13  5727.3  284.09    5733  283.63  5749.1   284.6  5827.4   286.3
#Mann= 8 ,-1 , 0
  4666.5      .1       0  4741.7     .05       0  4994.8     .03       0
  5000.8     .05       0  5154.5      .1       0  5264.4     .05       0
    5594     .16       0  5703.8      .1       0
Bank Sta=4994.8,5000.8
XS Rating Curve= 0 ,0
Exp/Cntr=0.3,0.1

Type RM Length L Ch R = 1 ,1245    ,281,281,281
BEGIN DESCRIPTION:
UNT05250 IN WICK 2.0
END DESCRIPTION:
XS GIS Cut Line= 3
      3579268.74     10244066.19      3579925.02     10243576.59
      3580147.83      10243317.5
#Sta/Elev= 30
  4336.8  269.36  4370.8  268.66  4385.4  267.55  4420.9  267.18  4451.9  264.76
  4470.9  263.46  4485.5  260.87  4491.8  260.59  4500.1  258.63  4514.7  257.42
  4550.2  255.07  4627.9  251.46  4762.8  251.29  4911.9  250.97  4914.7  250.47
  4917.9  250.97  5014.7  251.15  5042.2  252.08  5056.8  253.56    5086  258.72
  5134.4  265.52  5142.2  265.69  5150.6  266.85  5154.9   266.5  5292.1  272.91
  5362.4  274.53  5384.3  276.01  5405.1  275.65  5447.9  276.58  5497.3  277.41
#Mann= 9 ,-1 , 0
  4336.8      .1       0  4451.9     .05       0  4627.9      .1       0
  4762.8     .05       0  4911.9    .035       0  4917.9     .05       0
  5134.4      .1       0  5154.9     .16       0  5447.9     .05       0
Bank Sta=4911.9,4917.9
XS Rating Curve= 0 ,0
Exp/Cntr=0.3,0.1

Type RM Length L Ch R = 1 ,964     ,105,105,105
BEGIN DESCRIPTION:
Mapping XS da0250d7
END DESCRIPTION:
XS GIS Cut Line= 2
      3579284.64     10244159.63       3580560.7     10243404.41
#Sta/Elev= 30
  4511.3  268.59    4562  265.23  4771.1   252.3  4893.1   251.2  4970.9  251.04
  4973.6  250.54  4976.9  251.04  5062.1  251.28  5181.7  251.32  5207.9  251.36
  5223.5  256.58  5239.1  258.77  5244.9  258.74  5260.6  253.35  5275.3  252.73
    5544  257.21  5565.8  258.53  5595.9  255.67  5617.4  257.47    5633  255.48
  5638.8  258.75  5654.4  256.94  5660.2  259.05  5697.3   255.8  5718.7  260.15
  5835.7   261.3    5867  265.13  5894.2  264.93  5909.9  267.92  5994.1  271.35
#Mann= 8 ,-1 , 0
  4511.3      .1       0    4562     .05       0  4893.1      .1       0
  4970.9     .07       0  4976.9      .1       0  5062.1     .05       0
  5181.7      .1       0    5544     .16       0
Bank Sta=4970.9,4976.9
XS Rating Curve= 0 ,0
Exp/Cntr=0.3,0.1

Type RM Length L Ch R = 1 ,859     ,132,132,132
BEGIN DESCRIPTION:
Mapping XS 6e066a7f
END DESCRIPTION:
XS GIS Cut Line= 2
      3579310.65     10244242.98      3580503.41     10243597.12
#Sta/Elev= 30
    4509  267.91  4754.2  253.07  4780.6  249.76  4783.3  249.26  4786.6  249.76
  4819.9  252.43  4857.9  250.42  4879.8  252.81  4917.9  250.61  4967.3  252.59
  4983.5  250.37  5027.2  252.88  5043.4  250.97  5049.1  252.82  5065.3  250.99
  5076.2   252.3  5114.7  252.71  5130.9  250.76  5152.8  253.63    5169  251.54
  5240.3  258.08  5262.1  256.37  5272.6  253.02  5278.3  255.88  5322.1  254.12
  5338.2  256.46  5343.9  254.89  5360.1  257.21    5434   258.9  5865.4  270.76
#Mann= 5 ,-1 , 0
    4509     .05       0  4780.6     .03       0  4786.6     .05       0
  5076.2      .1       0    5434     .16       0
Bank Sta=4780.6,4786.6
XS Rating Curve= 0 ,0
Exp/Cntr=0.3,0.1

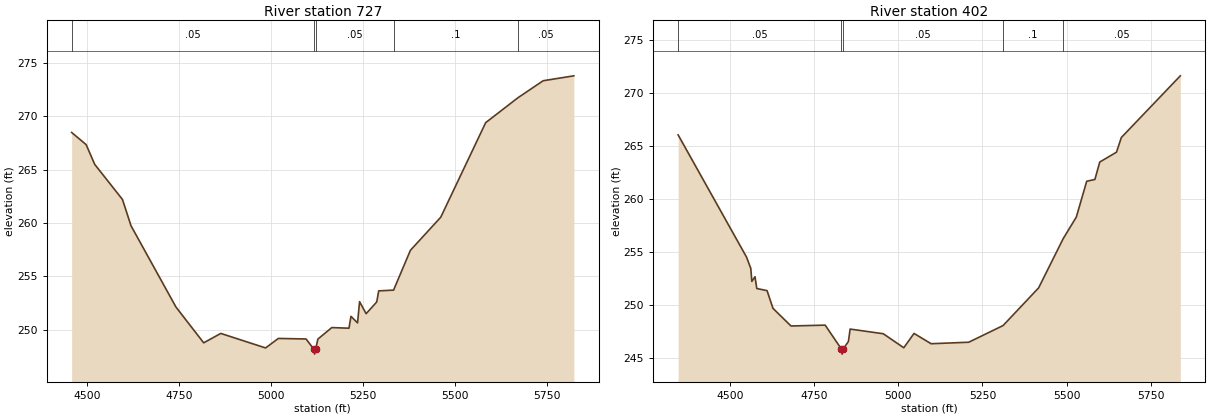
Type RM Length L Ch R = 1 ,727     ,325,325,325
BEGIN DESCRIPTION:
Mapping XS af21e219
END DESCRIPTION:
XS GIS Cut Line= 2
      3579289.91     10244352.02      3580538.47     10243800.86
#Sta/Elev= 30
  4457.9  268.49  4497.3  267.35  4520.6   265.5    4596  262.21  4619.3  259.74
  4741.3  252.13  4816.7  248.77  4863.3  249.65    4985  248.29  5019.6  249.18
    5095  249.13  5115.3  248.21  5118.1  247.71  5121.3  248.21  5127.1  249.12
    5165   250.2  5211.6  250.14    5217  251.25  5234.9  250.64  5240.4  252.63
  5258.2   251.5    5287   252.6  5292.4  253.64  5332.8  253.71  5378.5  257.44
  5461.1  260.55  5583.1  269.41    5671  271.75  5739.4  273.34  5822.7   273.8
#Mann= 5 ,-1 , 0
  4457.9     .05       0  5115.3     .03       0  5121.3     .05       0
  5332.8      .1       0    5671     .05       0
Bank Sta=5115.3,5121.3
XS Rating Curve= 0 ,0
Exp/Cntr=0.3,0.1

Type RM Length L Ch R = 1 ,402     ,0,0,0
BEGIN DESCRIPTION:
UNT05250 IN WICK 1.0
END DESCRIPTION:
XS GIS Cut Line= 4
      3579284.65     10244446.09      3579498.18     10244498.17
      3580477.35     10244321.09      3580696.07     10244149.23
#Sta/Elev= 30
  4345.1  266.06  4548.3  254.56  4561.1  253.49  4564.3  252.26  4573.7   252.7
    4579  251.59  4609.5  251.39  4627.2  249.72  4680.7  248.06  4782.3  248.14
  4830.1  245.91  4832.8  245.41  4836.1  245.91  4851.4   246.6  4856.5  247.77
    4955  247.33    5016  246.01  5046.5  247.36  5097.3  246.39  5209.1  246.53
  5311.2   248.1  5416.9  251.65    5490  256.29    5529  258.32  5559.8  261.69
  5584.2  261.86  5598.6   263.5  5648.4  264.43  5662.8  265.81  5838.1  271.62
#Mann= 5 ,-1 , 0
  4345.1     .05       0  4830.1     .03       0  4836.1     .05       0
  5311.2      .1       0    5490     .05       0
Bank Sta=4830.1,4836.1
XS Rating Curve= 0 ,0
Exp/Cntr=0.3,0.1

Chan Stop Cuts=-1
Use User Specified Reach Order=0
Composite Channel Slope=5