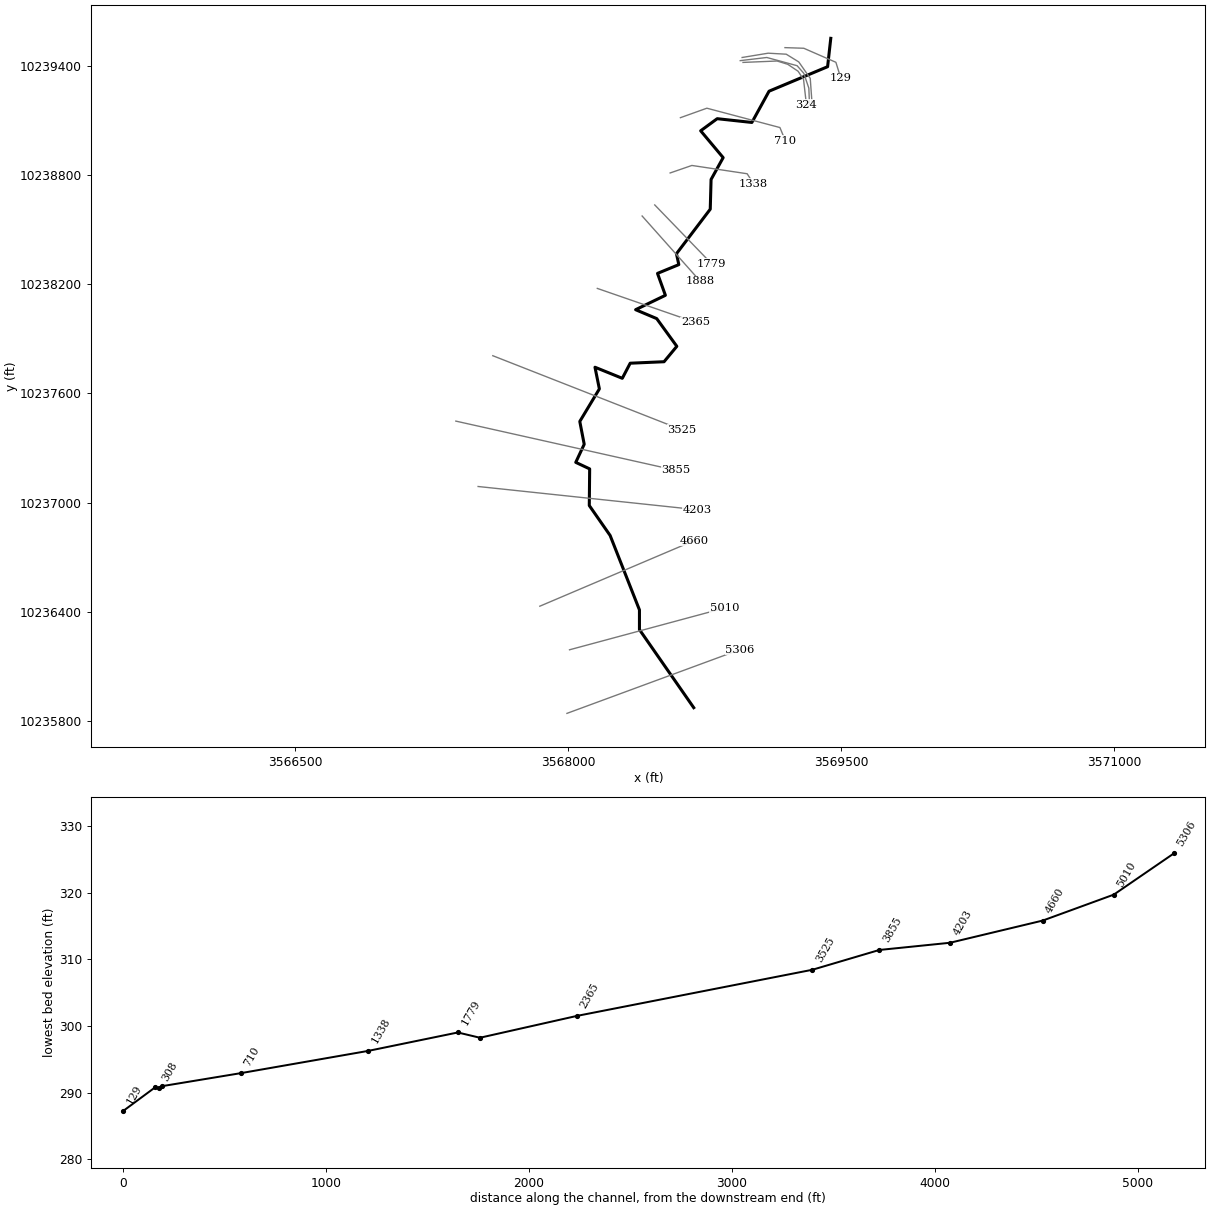
--- STEEPHOLLOWBRANCH.prj (project) ---

Proj Title=STEEP HOLLOW BRANCH TRIB 10
Current Plan=p01
Default Exp/Contr=0.3,0.1
English Units
Geom File=g01
Flow File=f01
Plan File=p01
Y Axis Title=Elevation
X Axis Title(PF)=Main Channel Distance
X Axis Title(XS)=Station
BEGIN DESCRIPTION:
UNT05242 IN WICK
END DESCRIPTION:
DSS Export Rating Curves= 0
DSS Export Rating Curve Sorted= 0
DSS Export Volume Flow Curves= 0
DXF OffsetX= 0
DXF OffsetY= 0
DXF ScaleX= 1
DXF ScaleY= 10

--- STEEPHOLLOWBRANCH.p01 (plan) ---

Plan Title=Multiple Run
Short Identifier=Multiple
Geom File=g01
Flow File=f01
Subcritical Flow
K Sum by GR= 0
Std Step Tol= 0.01
Critical Tol= 0.01
Num of Std Step Trials= 20
Max Error Tol= 0.3
Flow Tol Ratio= 0.001
Split Flow NTrial= 30
Split Flow Tol= 0.02
Split Flow Ratio= 0.02
Log Output Level= 0
Friction Slope Method= 1
Unsteady Friction Slope Method= 2
Unsteady Bridges Friction Slope Method= 1
Parabolic Critical Depth
Global Vel Dist=  1 , 1 , 1
Global Log Level= 0
CheckData=True
Encroach Param= -1, 0, 0, 0
BEGIN DESCRIPTION:
Multiple Run
END DESCRIPTION:

--- STEEPHOLLOWBRANCH.f01 (steady flow) ---

Flow Title=Multiple
Program Version=4.10
Number of Profiles= 7
Profile Names=10-year,25-year,50-year,1pct_min,100-year,1pct_plu,500-year
River Rch & RM=UNT05242 IN WICK,Reach-1         ,5306
     218     275     319     272     367     497     488
River Rch & RM=TEEPHOLLOWBRTR10,Reach-1         ,5306
     218     275     319     272     367     497     488
Boundary for River Rch & Prof#=TEEPHOLLOWBRTR10,Reach-1         , 1
Up Type= 0
Dn Type= 3
Dn Slope=0.005
Boundary for River Rch & Prof#=TEEPHOLLOWBRTR10,Reach-1         , 2
Up Type= 0
Dn Type= 3
Dn Slope=0.005
Boundary for River Rch & Prof#=TEEPHOLLOWBRTR10,Reach-1         , 3
Up Type= 0
Dn Type= 3
Dn Slope=0.005
Boundary for River Rch & Prof#=TEEPHOLLOWBRTR10,Reach-1         , 4
Up Type= 0
Dn Type= 3
Dn Slope=0.005
Boundary for River Rch & Prof#=TEEPHOLLOWBRTR10,Reach-1         , 5
Up Type= 0
Dn Type= 3
Dn Slope=0.005
Boundary for River Rch & Prof#=TEEPHOLLOWBRTR10,Reach-1         , 6
Up Type= 0
Dn Type= 3
Dn Slope=0.005
Boundary for River Rch & Prof#=TEEPHOLLOWBRTR10,Reach-1         , 7
Up Type= 0
Dn Type= 3
Dn Slope=0.005
DSS Import GetInterval= 0
DSS Import GetPeak= 0
DSS Import FillOption= 0

--- STEEPHOLLOWBRANCH.g01 (geometry) ---

Geom Title=Existing Conditions
Program Version=4.10

River Reach=TEEPHOLLOWBRTR10,Reach-1
Reach XY= 30
      3568688.92     10235872.98      3568390.61     10236301.99
      3568390.61     10236410.32       3568229.5     10236819.35
      3568114.92     10236983.93        3568117.     10237185.32
      3568040.58     10237221.23      3568087.02     10237320.62
      3568062.71     10237446.05      3568170.35     10237624.87
      3568146.22     10237744.05      3568296.32     10237683.17
      3568339.78     10237766.16      3568525.79     10237774.28
      3568596.04     10237858.95      3568485.47      10238011.3
      3568369.37     10238060.24      3568533.22     10238139.34
      3568489.81     10238259.78        3568607.     10238307.96
      3568593.98     10238367.85      3568779.72     10238612.64
      3568784.28     10238776.02      3568850.67     10238895.95
       3568727.1     10239043.48       3568817.8     10239110.02
      3569008.57     10239089.34      3569102.92     10239261.08
      3569424.67     10239395.77      3569442.11     10239551.64

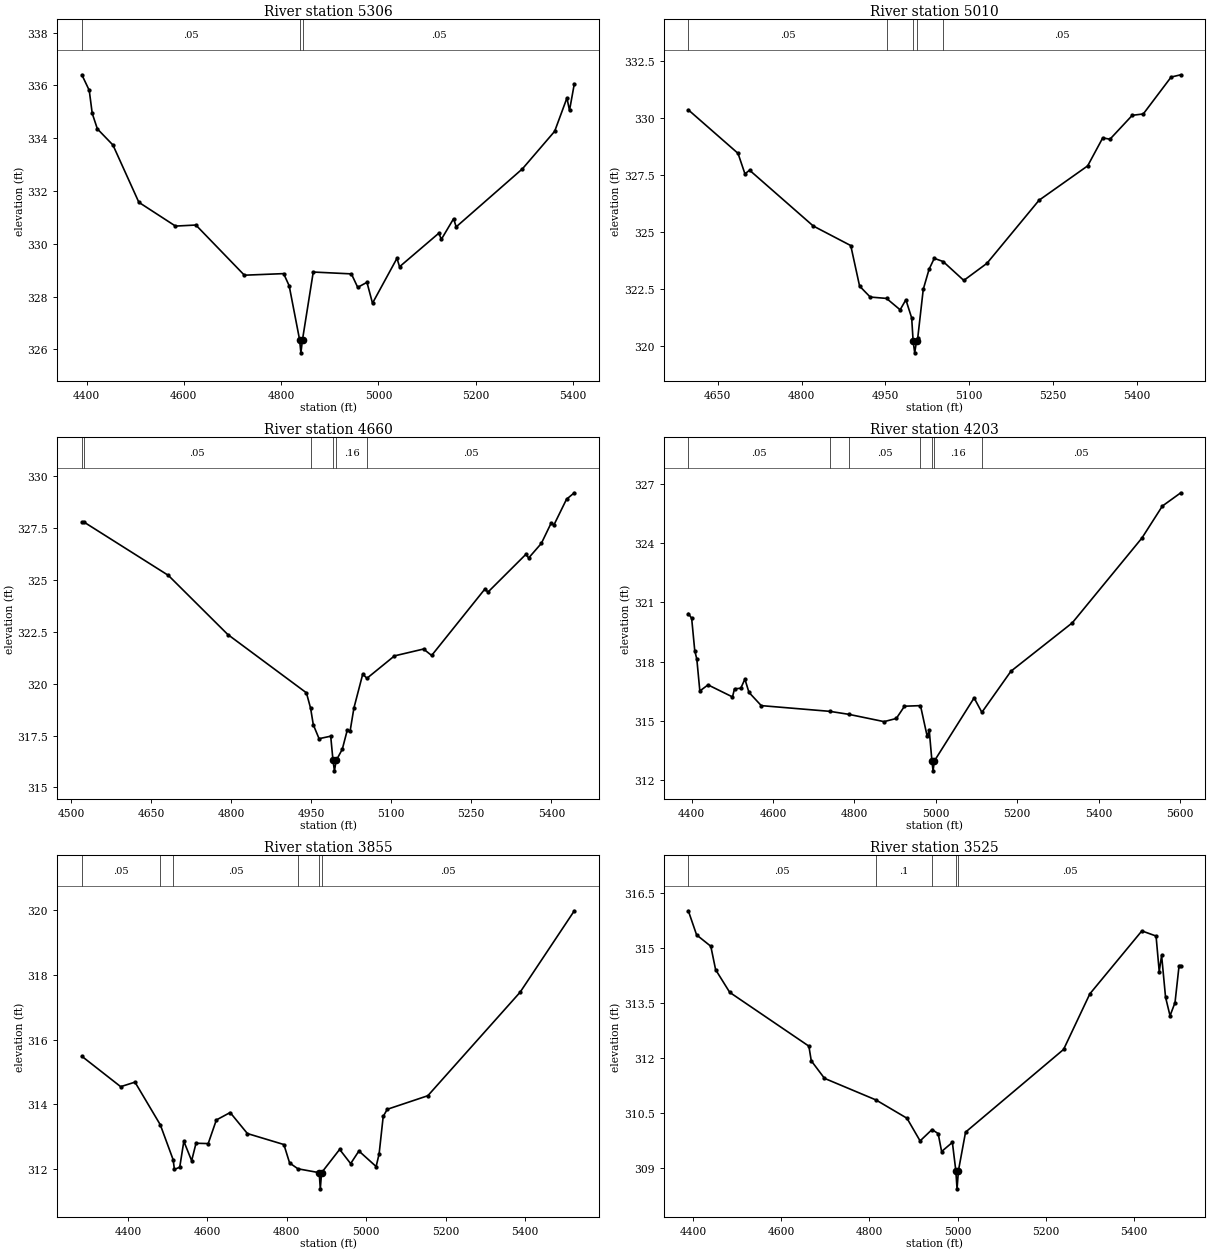
Type RM Length L Ch R = 1 ,5306    ,296,296,296
BEGIN DESCRIPTION:
UNT05242 IN WICK 7.0
END DESCRIPTION:
XS GIS Cut Line= 2
      3567992.15     10235841.66      3568942.13     10236191.65
#Sta/Elev= 30
  4390.4   336.4  4405.6  335.81  4411.7  334.94  4422.3  334.35  4454.3  333.74
  4507.6  331.57  4582.9  330.67  4624.8  330.71  4724.5  328.81  4805.2  328.87
  4816.6  328.41    4838  326.37  4840.7  325.87    4844  326.37  4866.1  328.93
  4944.5  328.86  4957.5  328.35  4976.5  328.54  4987.9  327.75  5038.2  329.45
  5043.5  329.13  5124.2   330.4  5129.5  330.17  5154.6  330.95  5159.9  330.64
  5296.2  332.84  5362.4  334.26  5387.6  335.52  5392.9  335.05  5402.8  336.06
#Mann= 3 ,-1 , 0
  4390.4     .05       0    4838     .03       0    4844     .05       0
Bank Sta=4838,4844
XS Rating Curve= 0 ,0
Exp/Cntr=0.3,0.1

Type RM Length L Ch R = 1 ,5010    ,350,350,350
BEGIN DESCRIPTION:
UNT05242 IN WICK 6.0
END DESCRIPTION:
XS GIS Cut Line= 2
      3568006.26     10236191.12      3568856.94     10236420.28
#Sta/Elev= 30
  4597.5  330.36  4686.4  328.45  4698.8  327.55  4707.1  327.71    4821  325.26
  4888.1   324.4  4903.9  322.62  4922.9  322.14  4952.1  322.08  4976.4  321.58
  4986.7  322.02  4997.1  321.22  4999.7  320.19  5002.5  319.69  5005.7  320.19
  5007.9  320.34  5017.8  322.48  5028.2  323.36  5037.5  323.84  5053.3   323.7
  5090.3  322.87  5131.7  323.62  5224.9  326.39  5311.9   327.9  5338.9  329.13
  5351.8  329.07  5391.7  330.12  5411.4  330.18  5461.2   331.8  5478.5   331.9
#Mann= 5 ,-1 , 0
  4597.5     .05       0  4952.1     .16       0  4999.7     .07       0
  5005.7     .16       0  5053.3     .05       0
Bank Sta=4999.7,5005.7
XS Rating Curve= 0 ,0
Exp/Cntr=0.3,0.1

Type RM Length L Ch R = 1 ,4660    ,457,457,457
BEGIN DESCRIPTION:
UNT05242 IN WICK 5.0
END DESCRIPTION:
XS GIS Cut Line= 2
      3567843.06      10236430.7      3568692.12     10236791.65
#Sta/Elev= 30
  4520.4  327.79  4523.6   327.8  4682.4  325.22  4793.8  322.37  4941.1  319.56
    4949  318.81    4954  318.02  4964.8  317.35  4986.6  317.47  4990.9   316.3
  4993.6   315.8  4996.9   316.3  5008.3  316.84  5017.5  317.75  5022.9  317.71
  5030.1  318.83  5046.6  320.46  5054.5  320.26  5106.1  321.34  5160.5  321.67
  5175.7  321.36  5275.7  324.57  5281.1  324.41  5352.1  326.23  5357.5  326.06
  5381.2  326.76  5399.4  327.73  5404.8  327.65  5428.4  328.89    5443   329.2
#Mann= 6 ,-1 , 0
  4520.4     .16       0  4523.6     .05       0    4949     .16       0
  4990.9     .07       0  4996.9     .16       0  5054.5     .05       0
Bank Sta=4990.9,4996.9
XS Rating Curve= 0 ,0
Exp/Cntr=0.3,0.1

Type RM Length L Ch R = 1 ,4203    ,348,348,348
BEGIN DESCRIPTION:
UNT05242 IN WICK 4.0
END DESCRIPTION:
XS GIS Cut Line= 2
      3567503.93     10237088.59      3568707.08     10236960.98
#Sta/Elev= 30
  4392.1  320.43  4400.3  320.19  4407.9  318.55    4413  318.12  4420.4  316.51
  4440.5  316.82  4500.6  316.21  4505.6  316.62    4521  316.65  4531.1  317.11
  4541.1  316.44  4571.3  315.77  4739.9  315.48  4786.2  315.33    4873  314.96
  4903.1  315.12  4923.2  315.74  4962.5  315.77    4979  314.21    4984  314.52
  4990.6  312.97  4993.4  312.47  4996.6  312.97  5094.2  316.16  5113.3  315.43
  5184.7  317.51  5335.5  319.96  5506.5  324.25  5556.8  325.87    5602  326.54
#Mann= 7 ,-1 , 0
  4392.1     .05       0  4739.9      .1       0  4786.2     .05       0
  4962.5     .16       0  4990.6     .07       0  4996.6     .16       0
  5113.3     .05       0
Bank Sta=4990.6,4996.6
XS Rating Curve= 0 ,0
Exp/Cntr=0.3,0.1

Type RM Length L Ch R = 1 ,3855    ,330,330,330
BEGIN DESCRIPTION:
Mapping XS 80dc98cd
END DESCRIPTION:
XS GIS Cut Line= 2
      3567381.54     10237447.96      3568591.81     10237177.15
#Sta/Elev= 30
  4284.2  315.49    4382  314.55    4418  314.69  4481.8  313.37  4514.1  312.29
  4517.3  311.99  4530.7  312.06    4541  312.86  4560.7  312.26  4571.7   312.8
  4602.4  312.79  4622.9  313.52  4657.7  313.75  4701.1   313.1    4793  312.76
  4807.4  312.19  4828.3  312.01  4881.9  311.89  4884.7  311.39  4887.9  311.89
  4933.4  312.61  4961.1  312.17  4981.9  312.56  5025.3  312.08  5032.8  312.47
  5043.1  313.63  5053.3  313.85  5155.5  314.27  5387.8  317.47  5524.4  319.99
#Mann= 6 ,-1 , 0
  4284.2     .05       0  4481.8      .1       0  4514.1     .05       0
  4828.3      .1       0  4881.9     .03       0  4887.9     .05       0
Bank Sta=4881.9,4887.9
XS Rating Curve= 0 ,0
Exp/Cntr=0.3,0.1

Type RM Length L Ch R = 1 ,3525    ,1160,1160,1160
BEGIN DESCRIPTION:
UNT05242 IN WICK 3.0
END DESCRIPTION:
XS GIS Cut Line= 2
      3567584.65     10237807.33       3568624.3     10237399.45
#Sta/Elev= 30
  4389.4  316.02  4408.2  315.36  4440.4  315.05  4451.3  314.41  4483.3  313.79
  4662.8  312.32  4668.2  311.92  4698.2  311.44  4814.9  310.85  4885.2  310.35
    4915  309.73    4942  310.04    4956  309.93  4963.8  309.44  4988.2  309.69
    4996  308.92  4998.8  308.42    5002  308.92  5018.1  309.97  5240.4  312.23
    5300  313.75  5417.9  315.47  5450.1  315.33  5457.3  314.36  5462.7   314.8
  5471.6  313.66  5481.8  313.15  5493.1  313.51  5502.3  314.52  5506.2  314.52
#Mann= 5 ,-1 , 0
  4389.4     .05       0  4814.9      .1       0    4942     .05       0
    4996     .03       0    5002     .05       0
Bank Sta=4996,5002
XS Rating Curve= 0 ,0
Exp/Cntr=0.3,0.1

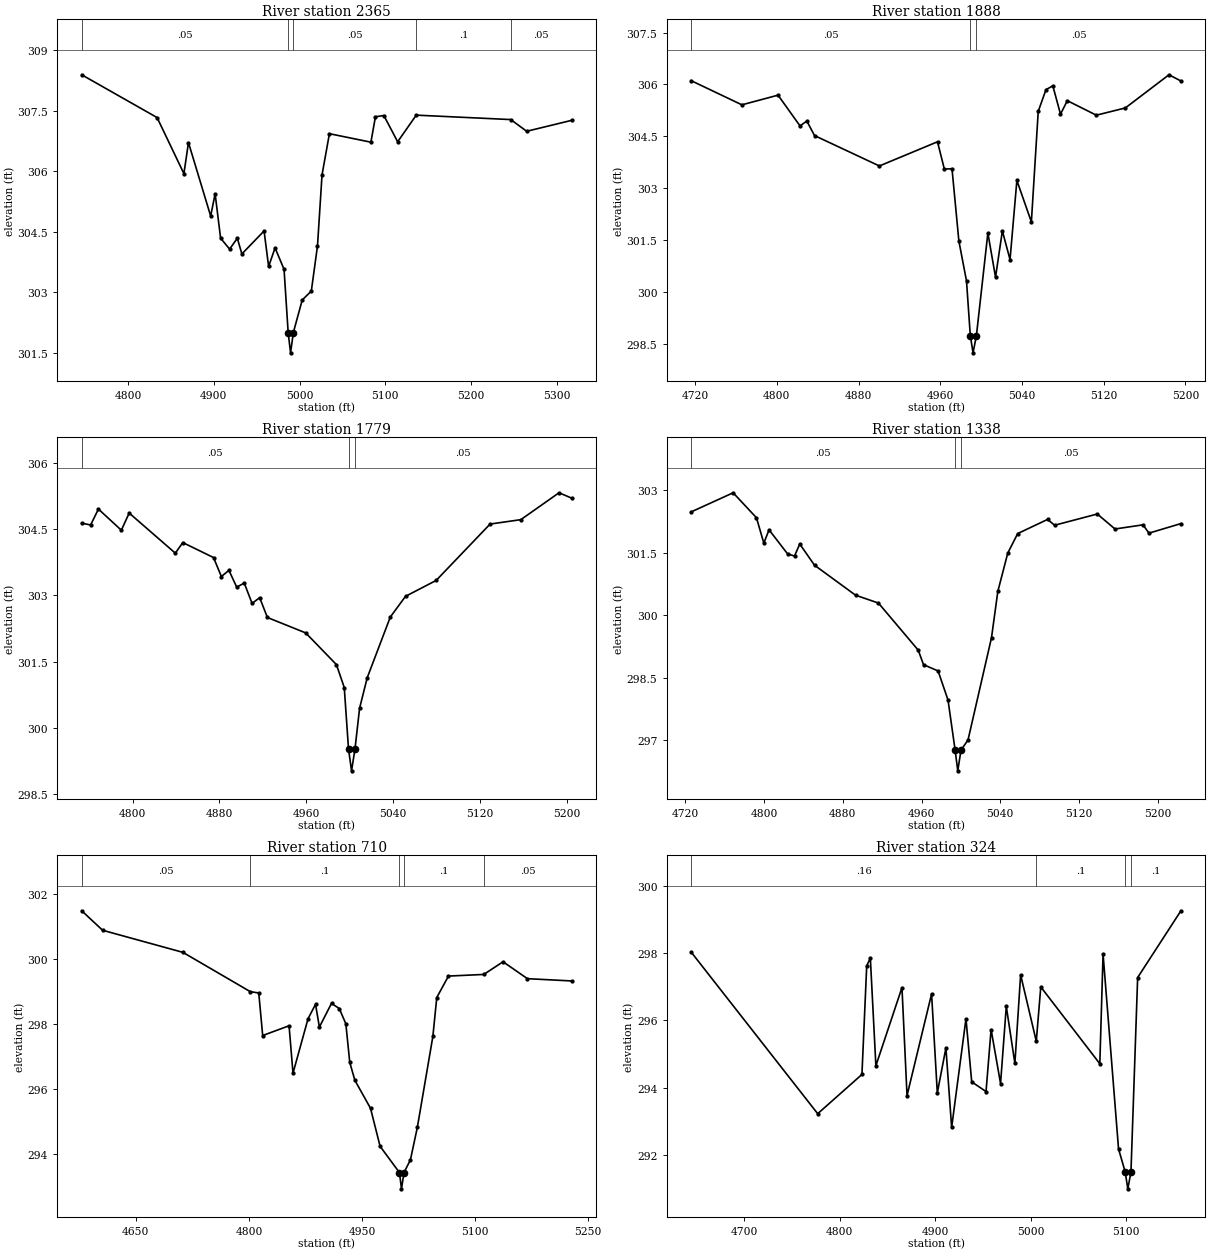
Type RM Length L Ch R = 1 ,2365    ,477,477,477
BEGIN DESCRIPTION:
UNT0504 IN WICK 1.0
END DESCRIPTION:
XS GIS Cut Line= 2
      3568159.05     10238177.22      3568698.92     10237990.34
#Sta/Elev= 30
  4745.9  308.39  4833.8  307.33  4865.1  305.94  4870.4  306.71  4896.3  304.89
  4901.5  305.44  4907.9  304.34  4918.4  304.07  4927.4  304.34  4932.7  303.95
  4958.6  304.52  4963.9  303.64  4971.4   304.1  4981.9  303.57  4986.7     302
  4989.5   301.5  4992.7     302  5003.1  302.81  5013.7  303.03  5020.9  304.15
  5026.2  305.91  5034.8  306.93  5083.2  306.72  5088.5  307.35  5098.3  307.38
  5114.4  306.73  5136.1  307.39  5246.3  307.28  5264.9  306.99  5317.2  307.26
#Mann= 5 ,-1 , 0
  4745.9     .05       0  4986.7     .03       0  4992.7     .05       0
  5136.1      .1       0  5246.3     .05       0
Bank Sta=4986.7,4992.7
XS Rating Curve= 0 ,0
Exp/Cntr=0.3,0.1

Type RM Length L Ch R = 1 ,1888    ,109,109,109
BEGIN DESCRIPTION:
Mapping XS 354111f4
END DESCRIPTION:
XS GIS Cut Line= 2
      3568405.33      10238575.2      3568724.29     10238217.18
#Sta/Elev= 30
  4716.1  306.11  4765.8  305.41  4801.2  305.69  4822.7   304.8  4829.4  304.94
  4836.9  304.52  4900.4  303.64  4957.3  304.34    4964  303.55  4971.5  303.56
  4978.2  301.47  4985.7  300.31  4989.4  298.73  4992.1  298.23  4995.4  298.73
  5006.6   301.7  5014.1  300.42  5020.8  301.76  5028.3  300.93    5035  303.22
  5049.2  302.02  5055.9  305.22  5063.5  305.85  5070.2  305.96  5077.7  305.14
  5084.4  305.53  5112.8  305.11  5141.2  305.32  5183.9  306.28  5195.6   306.1
#Mann= 3 ,-1 , 0
  4716.1     .05       0  4989.4     .04       0  4995.4     .05       0
Bank Sta=4989.4,4995.4
XS Rating Curve= 0 ,0
Exp/Cntr=0.3,0.1

Type RM Length L Ch R = 1 ,1779    ,441,441,441
BEGIN DESCRIPTION:
Mapping XS 85167af1
END DESCRIPTION:
XS GIS Cut Line= 2
      3568474.73     10238636.01      3568788.26     10238311.67
#Sta/Elev= 30
  4753.2  304.64  4761.4   304.6  4768.6  304.96  4789.7  304.48  4796.9  304.87
  4839.4  303.96  4846.3   304.2  4874.6  303.86  4881.8  303.43  4888.8  303.57
  4895.9  303.19  4902.9  303.28  4910.1  302.82  4917.1  302.95  4924.2   302.5
  4959.5  302.15  4987.8  301.43    4995  300.91  4998.9  299.52  5001.7  299.02
  5004.9  299.52  5009.1  300.44  5016.1  301.13  5037.4  302.51  5051.4  302.98
  5079.6  303.34  5129.3  304.62  5157.6  304.72  5192.8  305.33  5204.3  305.21
#Mann= 3 ,-1 , 0
  4753.2     .05       0  4998.9     .04       0  5004.9     .05       0
Bank Sta=4998.9,5004.9
XS Rating Curve= 0 ,0
Exp/Cntr=0.3,0.1

Type RM Length L Ch R = 1 ,1338    ,628,628,628
BEGIN DESCRIPTION:
Mapping XS e5c1d94d
END DESCRIPTION:
XS GIS Cut Line= 4
      3568559.37     10238811.77      3568678.74     10238853.01
      3568982.56     10238807.44      3569017.22     10238753.29
#Sta/Elev= 30
  4725.8  302.48  4768.5  302.94  4792.2  302.34  4799.7  301.73    4805  302.05
  4823.9  301.47  4830.9  301.42  4836.2  301.71  4851.2   301.2  4892.9  300.48
  4916.2  300.29  4956.6  299.16    4962  298.81  4976.8  298.66  4986.9  297.96
  4994.1  296.76  4996.8  296.26  5000.1  296.76  5007.2     297  5031.1  299.46
  5037.5  300.57  5047.6  301.49  5057.7  301.96  5088.1   302.3  5095.2  302.16
  5138.6  302.43  5156.6  302.07  5185.1  302.17  5191.1  301.97  5223.6   302.2
#Mann= 3 ,-1 , 0
  4725.8     .05       0  4994.1     .03       0  5000.1     .05       0
Bank Sta=4994.1,5000.1
XS Rating Curve= 0 ,0
Exp/Cntr=0.3,0.1

Type RM Length L Ch R = 1 ,710     ,386,386,386
BEGIN DESCRIPTION:
UNT05242 IN WICK 2.0
END DESCRIPTION:
XS GIS Cut Line= 4
      3568615.79     10239115.59      3568761.21     10239167.68
      3569162.68     10239061.34      3569193.07     10238987.54
#Sta/Elev= 30
  4578.3  301.48    4606  300.88  4712.5   300.2  4801.9  298.99  4813.1  298.95
  4818.3  297.64  4853.3  297.94  4858.5  296.48  4878.5  298.16  4888.4   298.6
  4893.5   297.9  4909.6  298.63  4919.9  298.47  4928.6     298  4933.8  296.81
  4940.6  296.26  4961.3   295.4    4974  294.23  4999.7  293.42  5002.4  292.92
  5005.7  293.42  5014.2  293.81  5023.4  294.81    5044  297.61  5049.2  298.81
  5064.7  299.47  5111.5  299.52  5137.1  299.91  5169.4  299.39  5227.9  299.32
#Mann= 5 ,-1 , 0
  4578.3     .05       0  4801.9      .1       0  4999.7     .07       0
  5005.7      .1       0  5111.5     .05       0
Bank Sta=4999.7,5005.7
XS Rating Curve= 0 ,0
Exp/Cntr=0.3,0.1

Type RM Length L Ch R = 1 ,324     ,16,16,16
BEGIN DESCRIPTION:
Mapping XS dab505f0
END DESCRIPTION:
XS GIS Cut Line= 6
      3568959.76     10239419.31      3569147.31     10239426.95
      3569205.64      10239408.9      3569262.59      10239370.7
      3569292.45     10239325.56      3569308.42     10239186.33
#Sta/Elev= 30
  4644.5  298.04    4777  293.22  4823.3  294.39  4828.3  297.63  4832.1  297.86
  4837.9  294.65  4865.2  296.98  4870.5  293.76  4896.2  296.79  4902.2  293.84
  4911.2  295.18  4917.2  292.81  4932.2  296.05  4938.2  294.17  4953.2  293.88
  4958.5  295.73  4968.4  294.12  4974.4  296.42  4983.4  294.72  4989.4  297.36
  5005.8  295.38  5010.5     297  5072.3  294.71  5075.7  297.98  5091.9  292.17
  5098.9  291.48  5101.6  290.98  5104.9  291.48  5111.9  297.28  5157.2  299.27
#Mann= 4 ,-1 , 0
  4644.5     .16       0  5005.8      .1       0  5098.9     .07       0
  5104.9      .1       0
Bank Sta=5098.9,5104.9
XS Rating Curve= 0 ,0
Exp/Cntr=0.3,0.1

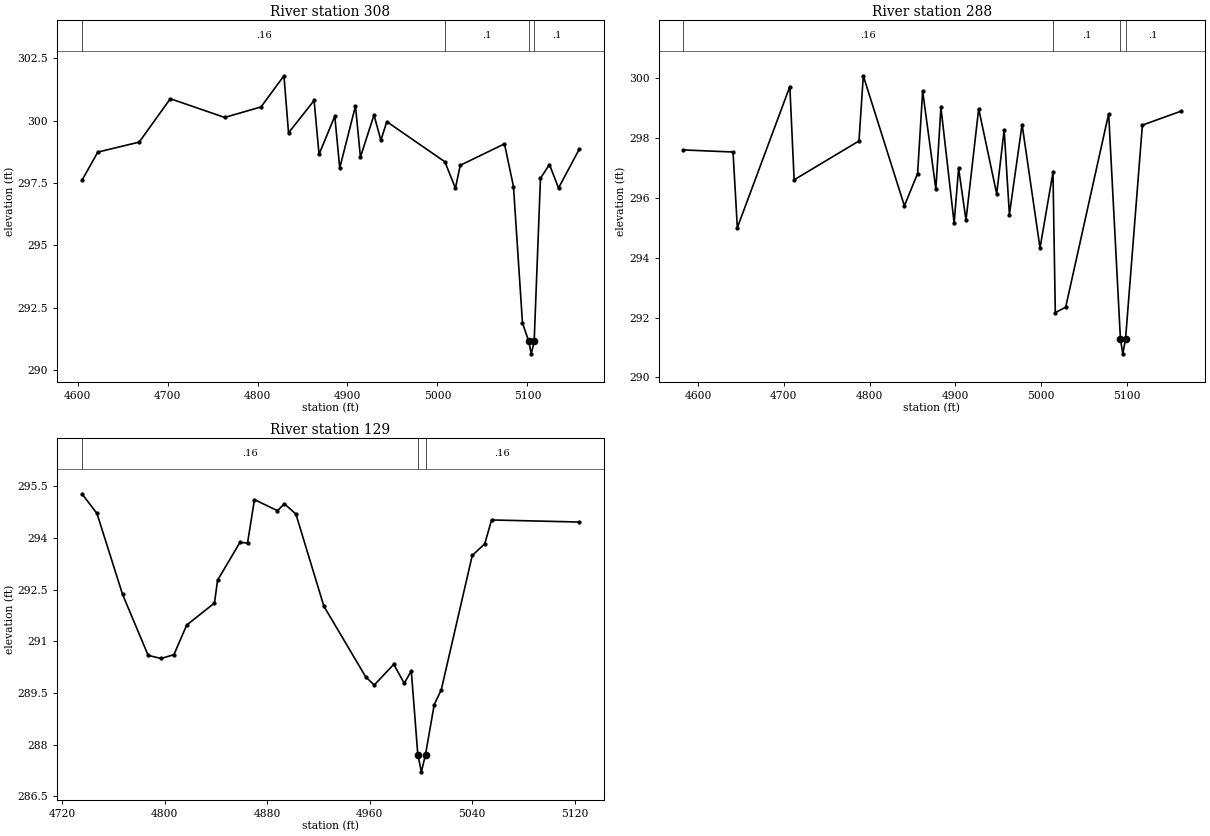
Type RM Length L Ch R = 1 ,308     ,20,20,20
BEGIN DESCRIPTION:
Mapping XS 67f94834
END DESCRIPTION:
XS GIS Cut Line= 6
      3568944.58     10239429.04      3569090.37      10239446.4
      3569257.03     10239401.26      3569293.84     10239359.59
      3569321.62     10239277.65      3569325.09     10239188.71
#Sta/Elev= 30
  4604.9  297.61  4622.5  298.74  4668.5  299.14  4703.1  300.88  4763.5  300.13
  4803.9  300.55  4829.4   301.8  4834.5  299.51  4862.9  300.81  4868.4  298.65
  4885.9  300.18  4891.4   298.1  4908.9  300.59  4914.4  298.54  4929.5  300.23
  4937.1  299.21  4943.7  299.96  5008.3  298.35    5020  297.29  5025.3  298.21
  5074.5  299.07  5084.5  297.36  5094.5  291.89  5101.5  291.15  5104.3  290.65
  5107.5  291.15  5114.5  297.69  5124.5  298.24  5134.6   297.3  5157.5  298.85
#Mann= 4 ,-1 , 0
  4604.9     .16       0  5008.3      .1       0  5101.5     .07       0
  5107.5      .1       0
Bank Sta=5101.5,5107.5
XS Rating Curve= 0 ,0
Exp/Cntr=0.3,0.1

Type RM Length L Ch R = 1 ,288     ,159,159,159
BEGIN DESCRIPTION:
Mapping XS c144ab72
END DESCRIPTION:
XS GIS Cut Line= 6
      3568954.97      10239446.4      3569098.01     10239470.01
      3569197.31     10239464.45      3569266.06     10239422.09
      3569329.26     10239331.81      3569339.67     10239188.08
#Sta/Elev= 30
    4583  297.61  4640.9  297.54  4645.9  295.01  4707.1  299.73  4712.1  296.61
  4787.7  297.91  4792.7  300.09  4840.6  295.74    4856  296.82  4861.9  299.58
  4877.3   296.3  4883.2  299.03  4898.6  295.16  4903.8     297  4912.4  295.26
  4927.2  298.99  4948.2  296.14  4956.9  298.28    4963  295.45  4977.8  298.46
  4998.7  294.33  5013.8  296.86  5016.5  292.17  5028.6  292.35  5078.7  298.82
  5092.4  291.29  5095.2  290.79  5098.4  291.29    5118  298.44  5162.5   298.9
#Mann= 4 ,-1 , 0
    4583     .16       0  5013.8      .1       0  5092.4     .07       0
  5098.4      .1       0
Bank Sta=5092.4,5098.4
XS Rating Curve= 0 ,0
Exp/Cntr=0.3,0.1

Type RM Length L Ch R = 1 ,129     ,0,0,0
BEGIN DESCRIPTION:
UNT05242 IN WICK 1.0
END DESCRIPTION:
XS GIS Cut Line= 4
      3569190.38     10239500.56      3569293.84     10239497.09
      3569470.23     10239420.01      3569497.56     10239331.86
#Sta/Elev= 30
  4735.3  295.28    4747  294.71    4767  292.36    4787  290.59  4797.1   290.5
  4807.1  290.61  4817.1  291.47  4838.8  292.11  4841.2  292.77  4858.7  293.87
  4864.6  293.85    4870  295.11    4888  294.79  4893.4  294.99  4902.4  294.69
  4924.2  292.02    4957  289.96  4963.6  289.73  4978.8  290.33    4987  289.78
  4992.5  290.14  4997.6  287.71  5000.4  287.21  5003.6  287.71  5010.4  289.16
  5015.9  289.59  5040.1  293.49  5049.9  293.83  5055.2  294.52  5123.6  294.46
#Mann= 3 ,-1 , 0
  4735.3     .16       0  4997.6     .07       0  5003.6     .16       0
Bank Sta=4997.6,5003.6
XS Rating Curve= 0 ,0
Exp/Cntr=0.3,0.1

Chan Stop Cuts=-1
Use User Specified Reach Order=0
Composite Channel Slope=5