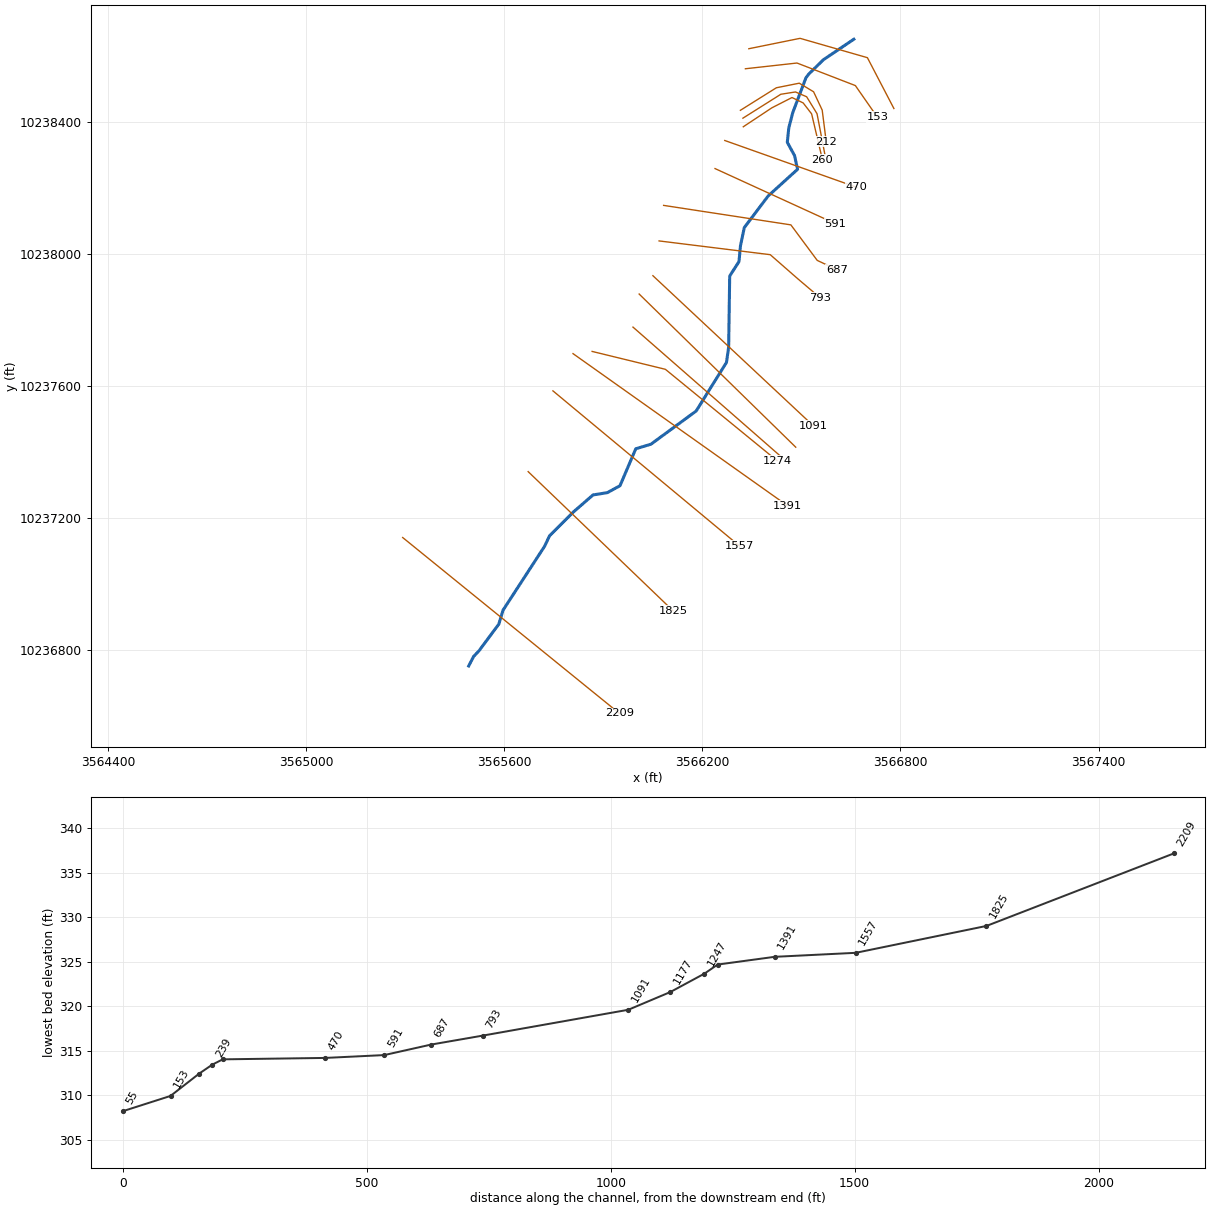
--- STEEPHOLLOWBRANCH.prj (project) ---

Proj Title=STEEP HOLLOW BRANCH TRIB 11 1
Current Plan=p01
Default Exp/Contr=0.3,0.1
English Units
Geom File=g01
Flow File=f01
Plan File=p01
Y Axis Title=Elevation
X Axis Title(PF)=Main Channel Distance
X Axis Title(XS)=Station
BEGIN DESCRIPTION:
UNT005 IN WICK
END DESCRIPTION:
DSS Export Rating Curves= 0
DSS Export Rating Curve Sorted= 0
DSS Export Volume Flow Curves= 0
DXF Filename=UNT005 IN WICK.
DXF OffsetX= 0
DXF OffsetY= 0
DXF ScaleX= 1
DXF ScaleY= 10

--- STEEPHOLLOWBRANCH.p01 (plan) ---

Plan Title=Multiple Run
Short Identifier=Multiple
Geom File=g01
Flow File=f01
Subcritical Flow
K Sum by GR= 0
Std Step Tol= 0.01
Critical Tol= 0.01
Num of Std Step Trials= 20
Max Error Tol= 0.3
Flow Tol Ratio= 0.001
Split Flow NTrial= 30
Split Flow Tol= 0.02
Split Flow Ratio= 0.02
Log Output Level= 0
Friction Slope Method= 1
Unsteady Friction Slope Method= 2
Unsteady Bridges Friction Slope Method= 1
Parabolic Critical Depth
Global Vel Dist=  1 , 1 , 1
Global Log Level= 0
CheckData=True
Encroach Param= -1, 0, 0, 0
BEGIN DESCRIPTION:
Multiple Run
END DESCRIPTION:

--- STEEPHOLLOWBRANCH.f01 (steady flow) ---

Flow Title=Multiple
Program Version=4.10
Number of Profiles= 7
Profile Names=10-year,25-year,50-year,1pct_min,100-year,1pct_plu,500-year
River Rch & RM=UNT005 IN WICK,Reach-1         ,2209
      81      96     106      86     117     158     142
River Rch & RM=UNT005 IN WICK,Reach-1         ,153
     249     319     373     321     434     587     587
River Rch & RM=EPHOLLOWBRTRB111,Reach-1         ,2209
      81      96     106      86     117     158     142
River Rch & RM=EPHOLLOWBRTRB111,Reach-1         ,153
     249     319     373     321     434     587     587
Boundary for River Rch & Prof#=EPHOLLOWBRTRB111,Reach-1         , 1
Up Type= 0
Dn Type= 3
Dn Slope=0.005
Boundary for River Rch & Prof#=EPHOLLOWBRTRB111,Reach-1         , 2
Up Type= 0
Dn Type= 3
Dn Slope=0.005
Boundary for River Rch & Prof#=EPHOLLOWBRTRB111,Reach-1         , 3
Up Type= 0
Dn Type= 3
Dn Slope=0.005
Boundary for River Rch & Prof#=EPHOLLOWBRTRB111,Reach-1         , 4
Up Type= 0
Dn Type= 3
Dn Slope=0.005
Boundary for River Rch & Prof#=EPHOLLOWBRTRB111,Reach-1         , 5
Up Type= 0
Dn Type= 3
Dn Slope=0.005
Boundary for River Rch & Prof#=EPHOLLOWBRTRB111,Reach-1         , 6
Up Type= 0
Dn Type= 3
Dn Slope=0.005
Boundary for River Rch & Prof#=EPHOLLOWBRTRB111,Reach-1         , 7
Up Type= 0
Dn Type= 3
Dn Slope=0.005
DSS Import GetInterval= 0
DSS Import GetPeak= 0
DSS Import FillOption= 0

--- STEEPHOLLOWBRANCH.g01 (geometry) ---

Geom Title=Existing Conditions
Program Version=4.10

River Reach=EPHOLLOWBRTRB111,Reach-1
Reach XY= 30
       3565492.1     10236752.44      3565506.86     10236781.08
      3565523.35     10236798.45      3565583.25     10236879.17
      3565596.27     10236921.71      3565722.14     10237115.29
      3565736.89     10237146.54      3565809.81     10237219.45
      3565868.84     10237270.67      3565912.24     10237277.61
      3565950.43     10237298.45      3565998.18     10237410.42
      3566044.18     10237424.31      3566181.16     10237524.83
      3566272.83     10237671.71       3566279.6     10237718.06
      3566282.73     10237933.69      3566310.85     10237977.44
      3566315.54      10238026.4        3566327.     10238080.56
      3566399.39      10238176.4      3566488.45     10238257.13
      3566479.08     10238298.79       3566457.2      10238338.9
      3566461.89     10238383.17      3566473.87       10238429.
      3566513.45     10238533.69      3566521.79     10238545.15
      3566566.58      10238588.9      3566658.78     10238651.06

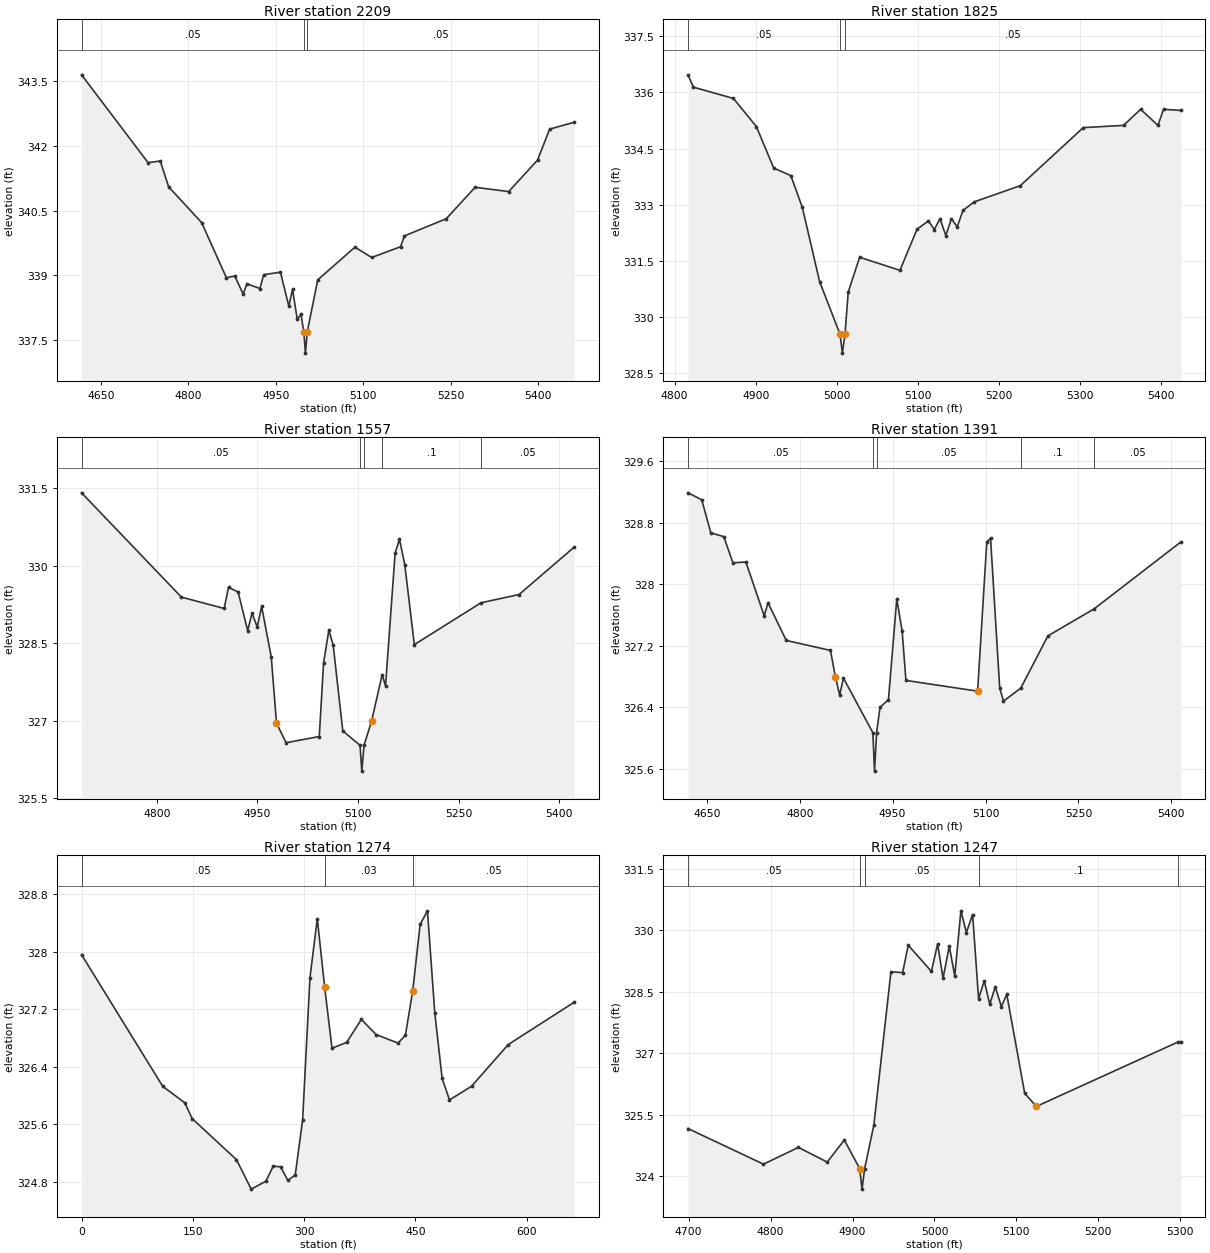
Type RM Length L Ch R = 1 ,2209    ,384,384,384
BEGIN DESCRIPTION:
UNT005 IN WICK 4.0
END DESCRIPTION:
XS GIS Cut Line= 2
      3565292.12     10237141.63      3565948.57     10236608.92
#Sta/Elev= 30
  4616.8  343.65    4731  341.61  4751.8  341.65  4766.2  341.05  4822.8  340.22
  4865.3  338.94  4879.7  338.98  4894.1  338.56  4900.5   338.8  4922.8  338.69
  4929.3  339.01    4958  339.07  4972.4  338.28  4978.8  338.67  4986.8  337.98
  4993.2  338.09  4998.1  337.69  5000.9  337.19  5004.1  337.69    5022  338.89
  5085.9  339.65  5114.6  339.41  5164.2  339.66  5170.6  339.91  5242.5  340.31
  5292.1  341.04  5349.6  340.94  5399.1  341.67  5419.9  342.39  5462.2  342.55
#Mann= 3 ,-1 , 0
  4616.8     .05       0  4998.1     .03       0  5004.1     .05       0
Bank Sta=4998.1,5004.1
XS Rating Curve= 0 ,0
Exp/Cntr=0.3,0.1

Type RM Length L Ch R = 1 ,1825    ,268,268,268
BEGIN DESCRIPTION:
UNT005 IN WICK 3.0
END DESCRIPTION:
XS GIS Cut Line= 2
      3565672.27     10237341.22      3566110.64     10236920.21
#Sta/Elev= 30
  4816.6  336.47  4823.3  336.14  4872.6  335.84  4900.9  335.09  4922.3  333.98
  4943.4  333.78  4957.6  332.93  4978.9  330.95  5004.2  329.54    5007  329.04
  5010.2  329.54  5014.2  330.67  5028.3   331.6    5078  331.25  5099.1  332.35
  5113.2  332.57  5120.4  332.34  5127.4  332.63  5134.6  332.18  5141.5  332.63
  5148.7  332.41  5155.7  332.85  5169.8  333.08  5226.4  333.51  5304.1  335.06
  5353.8  335.12  5374.9  335.55  5396.2  335.12  5403.2  335.55  5424.4  335.52
#Mann= 3 ,-1 , 0
  4816.6     .05       0  5004.2     .03       0  5010.2     .05       0
Bank Sta=5004.2,5010.2
XS Rating Curve= 0 ,0
Exp/Cntr=0.3,0.1

Type RM Length L Ch R = 1 ,1557    ,166,166,166
BEGIN DESCRIPTION:
Mapping XS 8e50cbfc
END DESCRIPTION:
XS GIS Cut Line= 2
      3565747.34     10237585.85      3566312.74     10237115.76
#Sta/Elev= 30
  4687.5  331.41  4836.5  329.39  4900.3  329.17  4906.8  329.58  4921.1  329.49
  4935.4  328.74  4941.9  329.08  4949.7  328.81  4956.2  329.21  4970.6  328.23
  4978.4  326.95  4992.7  326.57  5042.2  326.69  5048.7  328.12  5056.5  328.75
    5063  328.46  5077.3   326.8    5103  326.52  5105.7  326.02    5109  326.52
  5120.3  326.99  5136.1  327.89  5141.1  327.67  5155.4  330.24  5161.9  330.51
  5169.8  330.02  5184.1  328.47  5283.5  329.28  5340.3  329.44  5422.8  330.36
#Mann= 5 ,-1 , 0
  4687.5     .05       0    5103     .03       0    5109     .05       0
  5136.1      .1       0  5283.5     .05       0
Bank Sta=4978.4,5120.3
XS Rating Curve= 0 ,0
Exp/Cntr=0.3,0.1

Type RM Length L Ch R = 1 ,1391    ,117,117,117
BEGIN DESCRIPTION:
Mapping XS 1e757ebb
END DESCRIPTION:
XS GIS Cut Line= 2
       3565808.1     10237698.69      3566457.04     10237238.58
#Sta/Elev= 30
  4619.7  329.19  4641.8   329.1  4656.5  328.67  4677.4  328.62  4692.2  328.28
  4713.1  328.29  4742.7  327.59  4748.8  327.76  4778.3  327.27  4849.7  327.14
  4857.5   326.8  4864.5  326.56  4870.6  326.78  4918.1  326.07  4920.8  325.57
  4924.1  326.07  4929.7   326.4  4943.3   326.5  4956.7  327.81  4965.4  327.39
  4971.5  326.75  5087.2  326.61    5102  328.55  5108.1   328.6  5122.9  326.65
    5129  326.48  5156.9  326.65  5200.8  327.33  5275.2  327.68  5415.2  328.55
#Mann= 5 ,-1 , 0
  4619.7     .05       0  4918.1     .03       0  4924.1     .05       0
  5156.9      .1       0  5275.2     .05       0
Bank Sta=4857.5,5087.2
XS Rating Curve= 0 ,0
Exp/Cntr=0.3,0.1

Type RM Length L Ch R = 1 ,1274    ,27,27,27
XS GIS Cut Line= 3
      3565866.05    10237705.349     3566087.925    10237651.182
     3566425.949    10237374.619
#Sta/Elev= 30
       0  327.96  109.35  326.13  139.17   325.9  149.11  325.68  208.76  325.11
  228.64   324.7  248.43  324.81  258.33  325.02  268.22  325.01  278.12  324.82
  288.02   324.9  297.91  325.66  307.81  327.64  317.71  328.46   327.6  327.51
   337.5  326.66  357.29  326.74  377.08  327.06  396.87  326.85  426.56  326.73
  436.46  326.84  446.35  327.46  456.25  328.38  466.15  328.57  476.04  327.15
  485.94  326.24  495.83  325.94  525.52  326.13     575  326.71  664.07   327.3
#Mann= 3 , 0 , 0
       0     .05       0   327.6     .03       0  446.35     .05       0
#XS Ineff= 2 , 0
       0  317.46  326.64  449.58       0  326.74
Permanent Ineff=
       T       T
Bank Sta=327.6,446.35
XS Rating Curve= 0 ,0
Exp/Cntr=0.3,0.1

Type RM Length L Ch R = 1 ,1247    ,70,70,70
BEGIN DESCRIPTION:
Mapping XS aa1db41e
END DESCRIPTION:
XS GIS Cut Line= 2
      3565989.79       10237779.      3566442.48     10237382.93
#Sta/Elev= 30
  4699.2  325.16  4791.3  324.29    4834   324.7  4869.1  324.34    4890  324.88
  4908.8  324.18  4911.6  323.68  4914.8  324.18    4926  325.24  4946.9  328.99
  4961.2  328.97    4968  329.64  4996.3     329  5003.9  329.67  5010.5  328.83
  5018.1  329.62  5024.8  328.89  5032.3  330.48    5039  329.95  5046.6  330.39
  5053.9  328.33  5060.8  328.77  5067.5   328.2  5074.3  328.62  5081.7  328.14
  5088.3  328.44  5110.2  326.02  5124.4   325.7  5297.9  327.28  5300.7  327.28
#Mann= 5 ,-1 , 0
  4699.2     .05       0  4908.8     .03       0  4914.8     .05       0
  5053.9      .1       0  5297.9     .05       0
Bank Sta=4908.8,5124.4
XS Rating Curve= 0 ,0
Exp/Cntr=0.3,0.1

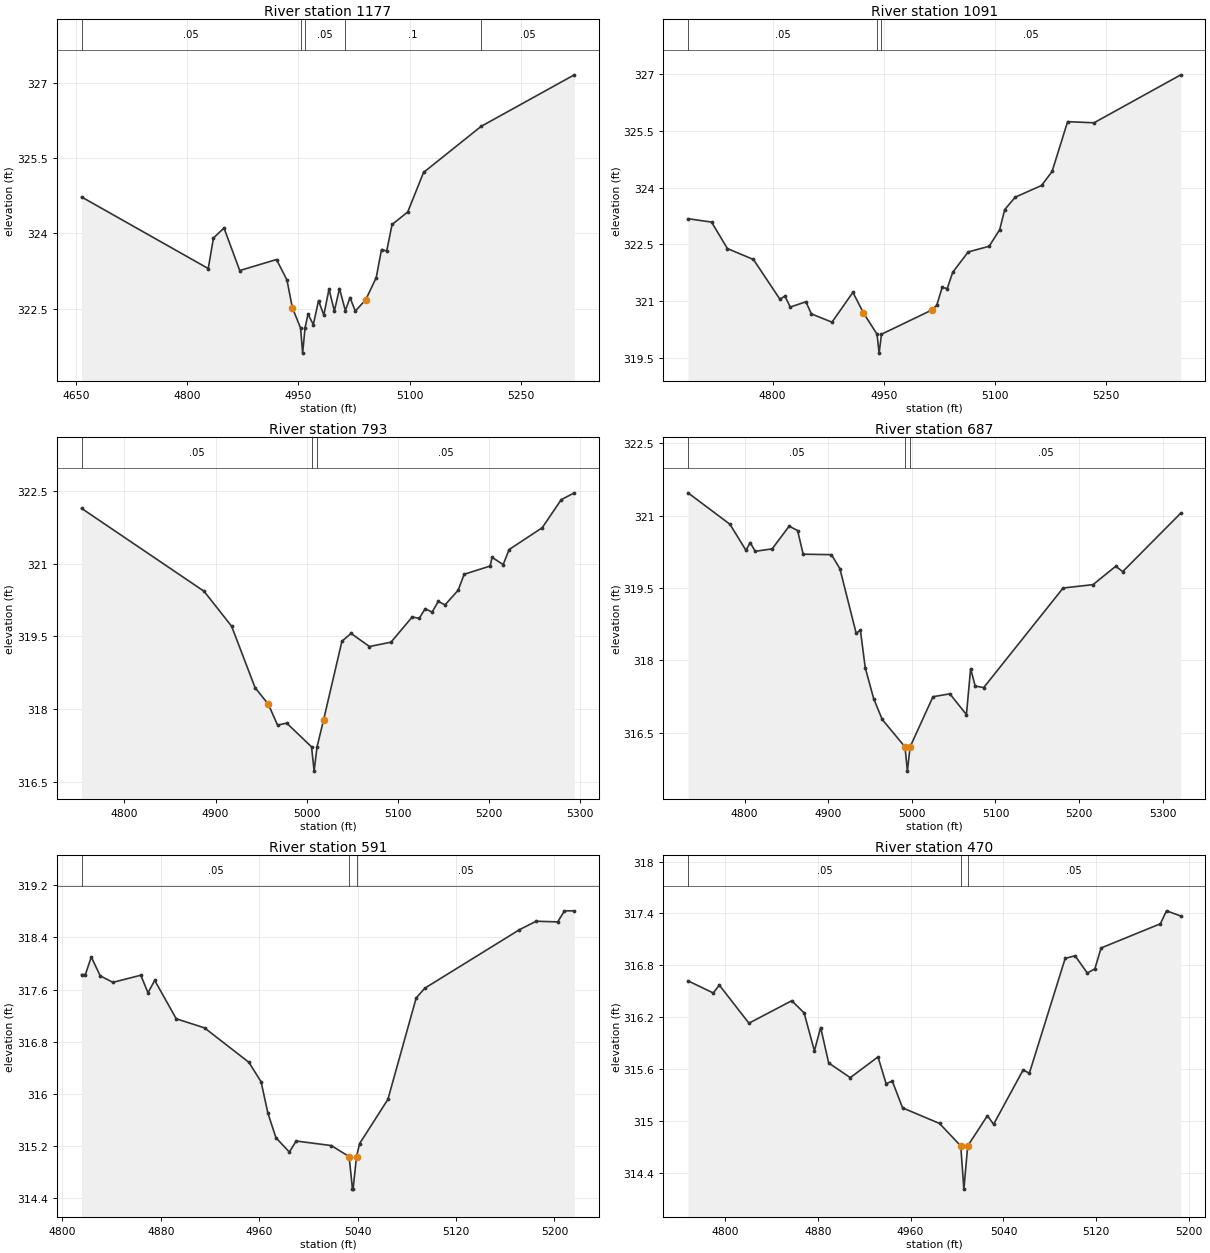
Type RM Length L Ch R = 1 ,1177    ,86,86,86
BEGIN DESCRIPTION:
Mapping XS cce51743
END DESCRIPTION:
XS GIS Cut Line= 2
      3566008.47     10237879.21       3566482.8     10237415.26
#Sta/Elev= 30
  4657.9  324.73  4828.5   323.3  4835.5  323.91  4849.7  324.11  4870.9  323.26
  4920.4  323.48  4934.5  323.07  4941.7  322.52  4952.8  322.11  4955.6  321.61
  4958.8  322.11  4962.8  322.39    4970  322.18    4977  322.66  4984.1  322.37
  4991.1  322.89  4998.3  322.45  5005.2   322.9  5013.1  322.46  5019.4  322.72
  5026.5  322.45  5040.7  322.68  5054.7  323.12  5061.8  323.68  5068.8  323.65
    5076  324.18  5097.1  324.43  5118.4  325.22  5195.9  326.14  5321.4  327.17
#Mann= 5 ,-1 , 0
  4657.9     .05       0  4952.8     .03       0  4958.8     .05       0
  5013.1      .1       0  5195.9     .05       0
Bank Sta=4941.7,5040.7
XS Rating Curve= 0 ,0
Exp/Cntr=0.3,0.1

Type RM Length L Ch R = 1 ,1091    ,298,298,298
BEGIN DESCRIPTION:
UNT005 IN WICK 2.0
END DESCRIPTION:
XS GIS Cut Line= 2
      3566050.11     10237934.79      3566536.27     10237479.89
#Sta/Elev= 30
  4685.7  323.18  4717.5  323.09  4738.9  322.39  4774.1   322.1  4809.8  321.05
  4816.6  321.13  4823.9  320.84    4845  320.98  4852.3  320.66  4880.2  320.44
  4908.5  321.23  4922.6  320.69  4941.1  320.12  4943.9  319.62  4947.1  320.12
  5014.9  320.76  5021.8  320.89  5029.1  321.36    5036  321.33  5043.3  321.76
  5064.3   322.3  5092.6  322.45  5106.8  322.89  5113.6  323.42  5127.8  323.75
  5163.4  324.06  5177.6  324.43  5198.6  325.75  5234.3  325.72  5351.5  326.99
#Mann= 3 ,-1 , 0
  4685.7     .05       0  4941.1     .03       0  4947.1     .05       0
Bank Sta=4922.6,5014.9
XS Rating Curve= 0 ,0
Exp/Cntr=0.3,0.1

Type RM Length L Ch R = 1 ,793     ,106,106,106
BEGIN DESCRIPTION:
Mapping XS f73144a4
END DESCRIPTION:
XS GIS Cut Line= 4
      3566068.81     10238040.08      3566405.58     10237998.42
      3566488.91     10237925.51      3566557.67     10237867.06
#Sta/Elev= 30
    4753  322.14  4887.3  320.43  4917.5  319.71  4943.3  318.44  4957.8   318.1
  4967.9  317.67    4978  317.71  5005.2  317.22    5008  316.72  5011.2  317.22
  5018.3  317.77  5038.5   319.4  5048.5  319.56  5068.7  319.29  5092.3  319.38
  5115.6   319.9  5123.2  319.87  5129.8  320.07  5137.4     320  5144.1  320.22
  5151.6  320.15  5165.9  320.45  5172.5  320.78    5201  320.95  5203.1  321.13
  5215.3  320.98  5221.8  321.29  5258.1  321.74    5279  322.32  5293.3  322.46
#Mann= 3 ,-1 , 0
    4753     .05       0  5005.2     .03       0  5011.2     .05       0
Bank Sta=4957.8,5018.3
XS Rating Curve= 0 ,0
Exp/Cntr=0.3,0.1

Type RM Length L Ch R = 1 ,687     ,96,96,96
BEGIN DESCRIPTION:
Mapping XS ea965330
END DESCRIPTION:
XS GIS Cut Line= 4
      3566082.62     10238147.73      3566468.08      10238088.7
      3566547.94     10237981.06      3566606.95     10237953.29
#Sta/Elev= 30
  4732.4  321.47  4782.5  320.82  4801.7  320.28  4806.7  320.44  4812.8  320.26
    4833  320.31  4853.3  320.78  4863.4  320.69  4870.1   320.2  4903.9  320.19
    4914   319.9  4933.5  318.56  4938.5  318.63  4944.3  317.85  4954.4  317.21
  4964.6  316.78  4991.9  316.21  4994.7  315.71  4997.9  316.21  5025.3  317.25
  5045.5  317.31  5065.3  316.88  5070.3  317.83  5075.8  317.47    5086  317.44
  5180.9   319.5  5216.7  319.57  5243.8  319.95  5252.2  319.84  5321.6  321.05
#Mann= 3 ,-1 , 0
  4732.4     .05       0  4991.9     .03       0  4997.9     .05       0
Bank Sta=4991.9,4997.9
XS Rating Curve= 0 ,0
Exp/Cntr=0.3,0.1

Type RM Length L Ch R = 1 ,591     ,121,121,121
BEGIN DESCRIPTION:
Mapping XS 8bd27d19
END DESCRIPTION:
XS GIS Cut Line= 2
      3566238.32     10238259.23      3566602.69     10238092.52
#Sta/Elev= 30
  4815.5  317.83  4818.6  317.83  4823.4   318.1  4830.7  317.81    4841  317.71
  4863.7  317.82  4869.5  317.55    4875  317.74  4892.5  317.15  4915.5  317.01
  4951.6  316.48  4961.5  316.18    4967   315.7  4973.6  315.32  4984.5   315.1
    4990  315.27  5018.6   315.2  5033.1  315.03  5035.8  314.53  5036.3  314.53
  5039.1  315.03  5041.6  315.23  5064.6  315.91  5087.6  317.47  5094.6  317.62
  5171.6  318.52  5185.2  318.65  5202.7  318.64  5208.2  318.81  5216.2  318.81
#Mann= 3 ,-1 , 0
  4815.5     .05       0  5033.1     .03       0  5039.1     .05       0
Bank Sta=5033.1,5039.1
XS Rating Curve= 0 ,0
Exp/Cntr=0.3,0.1

Type RM Length L Ch R = 1 ,470     ,210,210,210
BEGIN DESCRIPTION:
Mapping XS 47c7b8b3
END DESCRIPTION:
XS GIS Cut Line= 2
      3566267.84      10238344.3      3566667.98     10238202.26
#Sta/Elev= 30
  4768.2  316.62  4789.9  316.48  4795.2  316.57  4820.7  316.13  4857.6  316.39
  4868.2  316.25  4877.1  315.81  4882.5  316.08  4889.4  315.67    4908   315.5
  4931.9  315.74  4938.9  315.43  4944.2  315.46  4953.1  315.15  4984.9  314.97
  5003.2  314.71  5005.9  314.21  5009.2  314.71  5026.2  315.06  5031.5  314.96
    5057  315.59  5062.3  315.55  5093.2  316.88  5101.7  316.91  5112.3  316.71
  5118.8  316.76  5124.1     317  5175.2  317.28  5180.5  317.43  5192.8  317.37
#Mann= 3 ,-1 , 0
  4768.2     .05       0  5003.2     .03       0  5009.2     .05       0
Bank Sta=5003.2,5009.2
XS Rating Curve= 0 ,0
Exp/Cntr=0.3,0.1

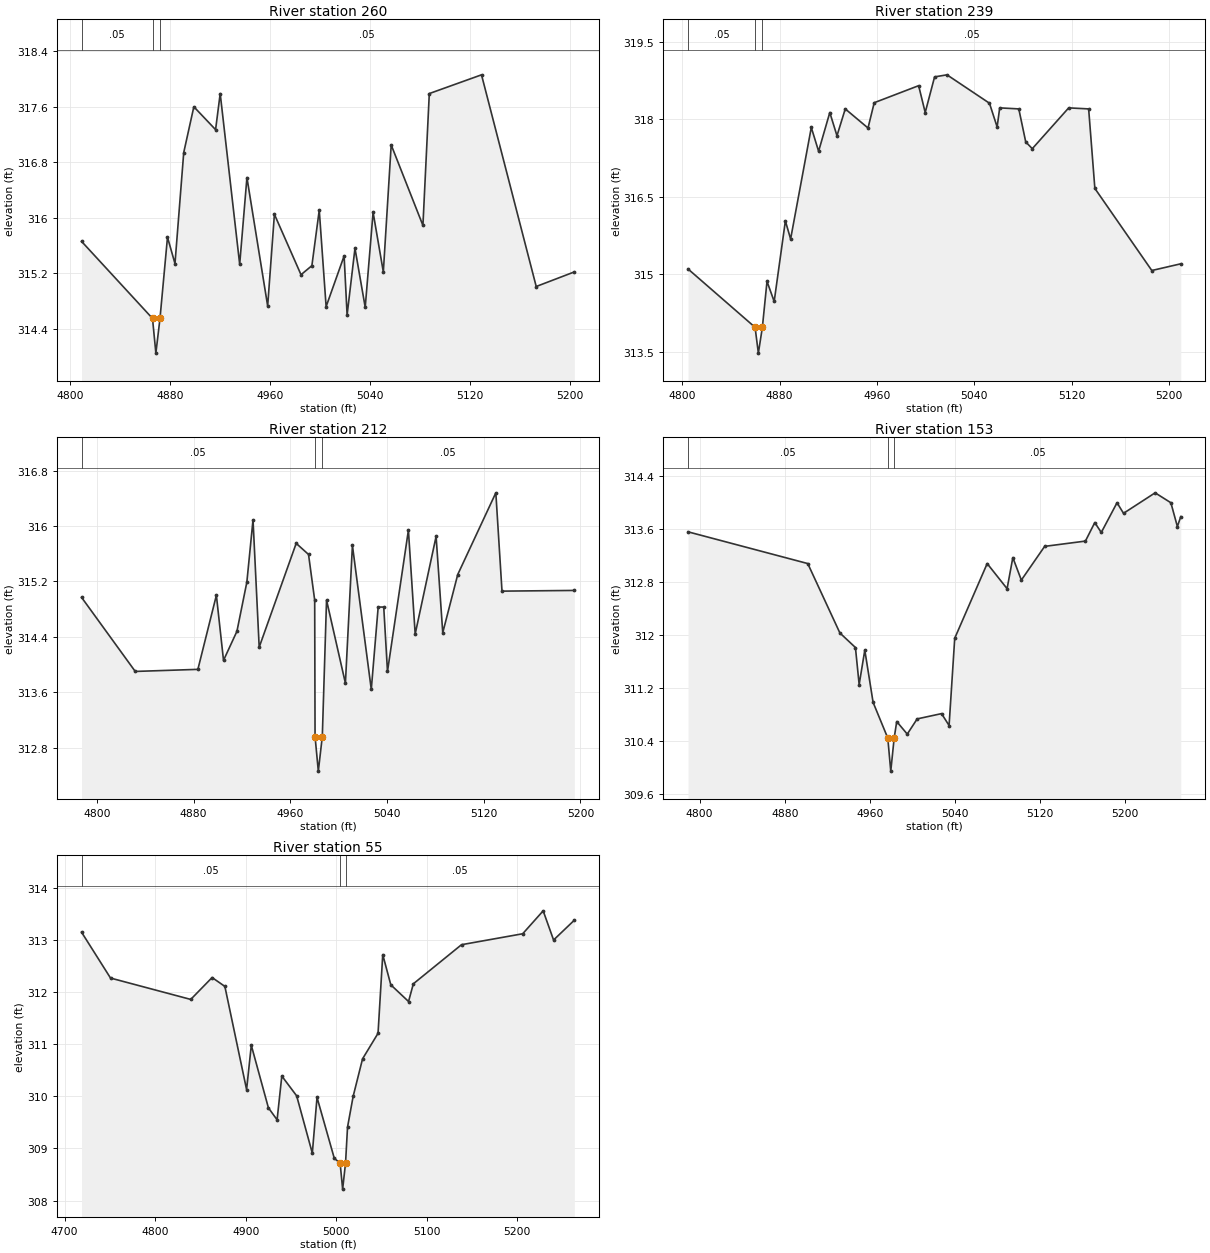
Type RM Length L Ch R = 1 ,260     ,21,21,21
BEGIN DESCRIPTION:
Mapping XS ed2be12b
END DESCRIPTION:
XS GIS Cut Line= 6
      3566323.87     10238385.87      3566410.65     10238443.36
      3566471.49     10238474.46      3566505.31     10238458.13
      3566530.96     10238424.89      3566563.57     10238286.38
#Sta/Elev= 30
    4809  315.66  4865.8  314.55  4868.5  314.05  4871.8  314.55  4877.8  315.72
  4883.8  315.34  4890.8  316.94  4898.9   317.6  4916.3  317.27    4920  317.79
  4935.6  315.33  4941.4  316.58    4958  314.73  4963.4  316.05  4984.7  315.18
  4993.4  315.31  4999.3  316.11  5004.8  314.72  5019.2  315.45  5021.6   314.6
  5027.9  315.56  5036.1  314.71  5042.4  316.08  5050.6  315.22  5056.9  317.05
  5082.3  315.89  5087.4  317.79  5129.2  318.06    5173  315.01  5203.5  315.22
#Mann= 3 ,-1 , 0
    4809     .05       0  4865.8     .03       0  4871.8     .05       0
Bank Sta=4865.8,4871.8
XS Rating Curve= 0 ,0
Exp/Cntr=0.3,0.1

Type RM Length L Ch R = 1 ,239     ,27,27,27
BEGIN DESCRIPTION:
Mapping XS dd22b096
END DESCRIPTION:
XS GIS Cut Line= 6
      3566322.77      10238411.9      3566437.67     10238484.37
      3566481.98     10238491.37       3566515.8     10238476.79
      3566547.29     10238425.48      3566571.23     10238301.25
#Sta/Elev= 30
  4804.8   315.1  4859.9  313.97  4862.6  313.47  4865.9  313.97  4869.7  314.86
  4875.6  314.47  4884.8  316.03  4889.1  315.68  4906.1  317.84  4912.1  317.38
  4921.3  318.13  4927.2  317.68    4934   318.2  4952.7  317.83  4957.8  318.32
  4994.3  318.65  4999.7  318.13  5007.4  318.82  5017.6  318.86  5052.5  318.31
  5058.8  317.85  5060.9  318.22  5076.6   318.2  5082.3  317.56  5087.7  317.43
  5117.6  318.22    5134   318.2  5139.1  316.66  5185.9  315.07  5209.7   315.2
#Mann= 3 ,-1 , 0
  4804.8     .05       0  4859.9     .03       0  4865.9     .05       0
Bank Sta=4859.9,4865.9
XS Rating Curve= 0 ,0
Exp/Cntr=0.3,0.1

Type RM Length L Ch R = 1 ,212     ,59,59,59
BEGIN DESCRIPTION:
Mapping XS fb6a3403
END DESCRIPTION:
XS GIS Cut Line= 6
      3566315.19     10238435.79      3566424.08     10238504.03
      3566493.52     10238517.92      3566536.92     10238491.87
      3566562.97     10238436.32      3566575.11     10238340.88
#Sta/Elev= 30
  4787.4  314.97  4831.8   313.9  4883.6  313.93  4898.9     315  4904.8  314.06
  4915.9  314.48  4924.1  315.19  4929.2  316.09  4934.3  314.25  4964.9  315.75
  4975.1  315.59  4980.2  314.93  4980.5  312.96  4983.2  312.46  4986.5  312.96
    4990  314.93  5005.6  313.73  5011.4  315.72    5027  313.64  5032.7  314.83
  5037.3  314.83  5040.4   313.9  5057.7  315.94  5063.3  314.44  5080.6  315.85
  5086.1  314.46  5098.5   315.3    5130  316.48  5135.1  315.06  5194.9  315.07
#Mann= 3 ,-1 , 0
  4787.4     .05       0  4980.5     .03       0  4986.5     .05       0
Bank Sta=4980.5,4986.5
XS Rating Curve= 0 ,0
Exp/Cntr=0.3,0.1

Type RM Length L Ch R = 1 ,153     ,98,98,98
BEGIN DESCRIPTION:
Mapping XS d9a0be59
END DESCRIPTION:
XS GIS Cut Line= 4
      3566330.31     10238561.63      3566486.61       10238579.
      3566663.47     10238510.64      3566729.85     10238415.35
#Sta/Elev= 30
  4789.1  313.56  4901.6  313.08  4931.8  312.03  4946.4  311.81  4949.9  311.25
  4955.2  311.77    4963  310.98  4976.8  310.44  4979.6  309.94  4982.8  310.44
  4985.2  310.69  4995.1   310.5  5004.4  310.73  5027.3  310.81  5034.4  310.63
  5039.7  311.95  5070.2  313.08  5088.9   312.7  5094.3  313.17  5102.3  312.83
  5124.2  313.34  5162.5  313.42  5171.3   313.7  5177.4  313.55  5192.2     314
  5198.3  313.84    5228  314.15  5242.8     314  5248.9  313.64  5252.1  313.79
#Mann= 3 ,-1 , 0
  4789.1     .05       0  4976.8     .03       0  4982.8     .05       0
Bank Sta=4976.8,4982.8
XS Rating Curve= 0 ,0
Exp/Cntr=0.3,0.1

Type RM Length L Ch R = 1 ,55      ,0,0,0
BEGIN DESCRIPTION:
UNT005 IN WICK 1.0
END DESCRIPTION:
XS GIS Cut Line= 4
      3566340.74      10238622.3      3566495.91     10238653.77
       3566699.9     10238595.17      3566780.19      10238441.1
#Sta/Elev= 30
  4718.7  313.15  4750.7  312.27  4839.3  311.86  4862.9  312.28    4877  312.11
    4901  310.13  4906.2  310.98  4925.1  309.78  4934.7  309.55  4939.9  310.39
  4956.3  310.01  4973.6  308.91  4978.8  309.98  4997.9  308.81  5004.3  308.72
  5007.1  308.22  5010.3  308.72  5012.5  309.41  5018.7     310  5029.1  310.72
  5046.2  311.21  5051.4  312.72  5060.3  312.14  5079.9  311.82  5085.2  312.16
  5138.4  312.91    5206  313.12  5228.6  313.56  5240.1     313    5263  313.38
#Mann= 3 ,-1 , 0
  4718.7     .05       0  5004.3     .03       0  5010.3     .05       0
Bank Sta=5004.3,5010.3
XS Rating Curve= 0 ,0
Exp/Cntr=0.3,0.1

Chan Stop Cuts=-1
Use User Specified Reach Order=0
Composite Channel Slope=5