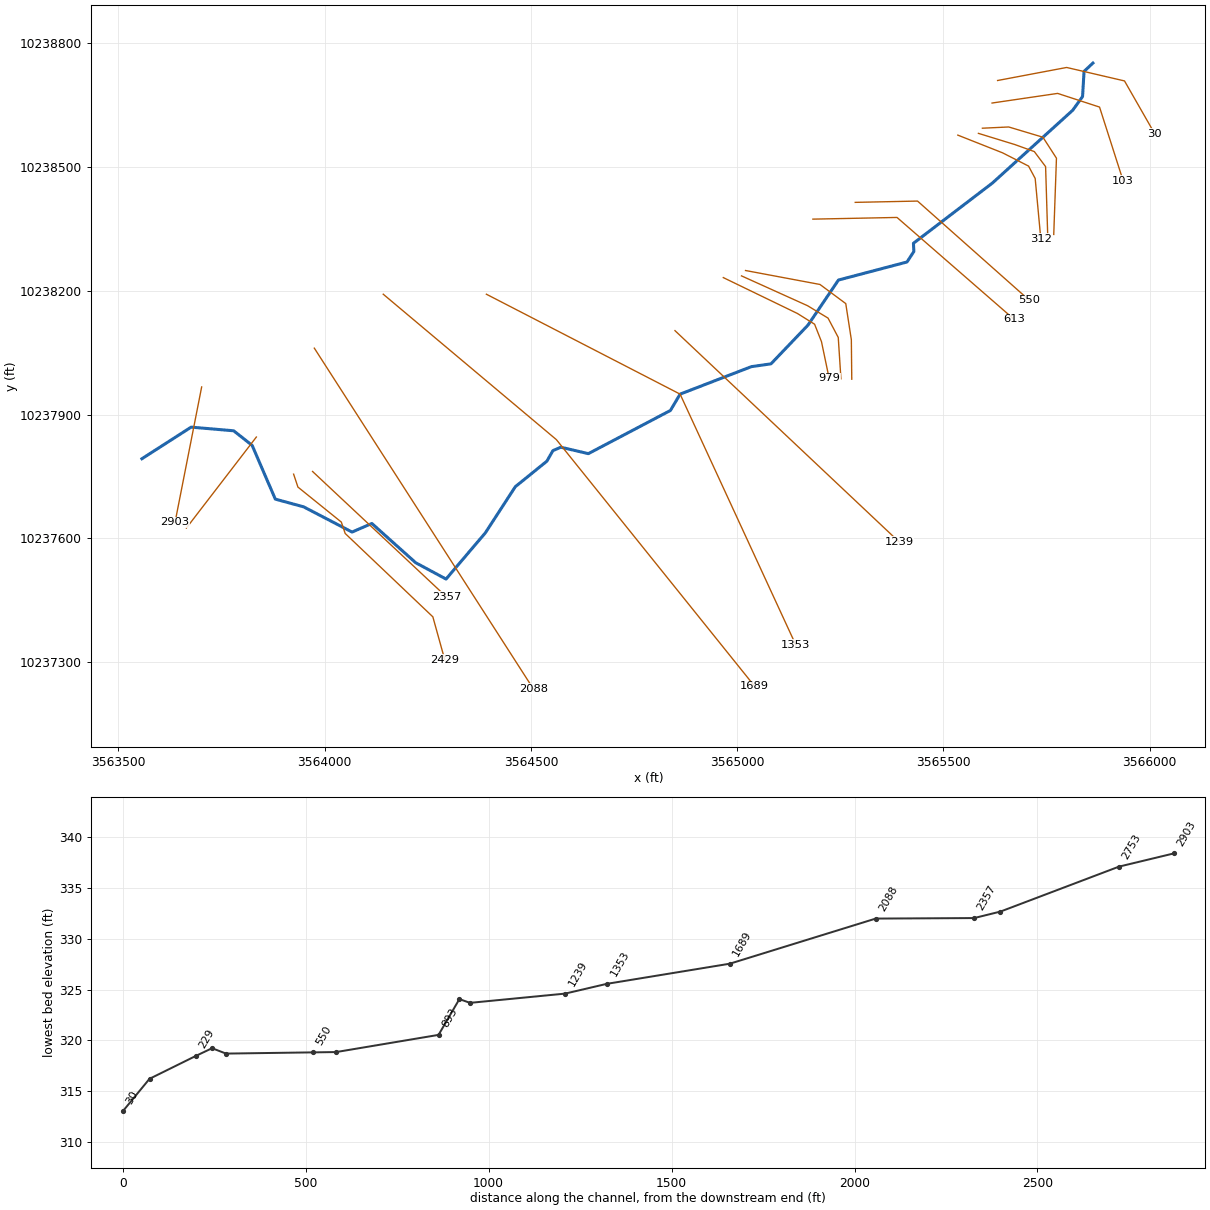
--- STEEPHOLLOWBRANCH.prj (project) ---

Proj Title=STEEP HOLLOW BRANCH TRIB 11 2
Current Plan=p01
Default Exp/Contr=0.3,0.1
English Units
Geom File=g01
Flow File=f01
Plan File=p01
Y Axis Title=Elevation
X Axis Title(PF)=Main Channel Distance
X Axis Title(XS)=Station
BEGIN DESCRIPTION:
UNT05239 IN WICK
END DESCRIPTION:
DSS Export Rating Curves= 0
DSS Export Rating Curve Sorted= 0
DSS Export Volume Flow Curves= 0
DXF Filename=UNT05239 IN WICK.
DXF OffsetX= 0
DXF OffsetY= 0
DXF ScaleX= 1
DXF ScaleY= 10

--- STEEPHOLLOWBRANCH.p01 (plan) ---

Plan Title=Multiple Run
Short Identifier=Multiple
Geom File=g01
Flow File=f01
Subcritical Flow
K Sum by GR= 0
Std Step Tol= 0.01
Critical Tol= 0.01
Num of Std Step Trials= 20
Max Error Tol= 0.3
Flow Tol Ratio= 0.001
Split Flow NTrial= 30
Split Flow Tol= 0.02
Split Flow Ratio= 0.02
Log Output Level= 0
Friction Slope Method= 1
Unsteady Friction Slope Method= 2
Unsteady Bridges Friction Slope Method= 1
Parabolic Critical Depth
Global Vel Dist=  1 , 1 , 1
Global Log Level= 0
CheckData=True
Encroach Param= -1, 0, 0, 0
BEGIN DESCRIPTION:
Multiple Run
END DESCRIPTION:

--- STEEPHOLLOWBRANCH.f01 (steady flow) ---

Flow Title=Multiple
Program Version=4.10
Number of Profiles= 7
Profile Names=10-year,25-year,50-year,1pct_min,100-year,1pct_plu,500-year
River Rch & RM=UNT05239 IN WICK,Reach-1         ,2903
     104     125     140     116     156     212     194
River Rch & RM=EPHOLLOWBRTRB112,Reach-1         ,2903
     104     125     140     116     156     212     194
River Rch & RM=EEPHOLLOWBRTR112,Reach-1         ,2903
     104     125     140     116     156     212     194
Boundary for River Rch & Prof#=EEPHOLLOWBRTR112,Reach-1         , 1
Up Type= 0
Dn Type= 3
Dn Slope=0.02
Boundary for River Rch & Prof#=EEPHOLLOWBRTR112,Reach-1         , 2
Up Type= 0
Dn Type= 3
Dn Slope=0.02
Boundary for River Rch & Prof#=EEPHOLLOWBRTR112,Reach-1         , 3
Up Type= 0
Dn Type= 3
Dn Slope=0.02
Boundary for River Rch & Prof#=EEPHOLLOWBRTR112,Reach-1         , 4
Up Type= 0
Dn Type= 3
Dn Slope=0.02
Boundary for River Rch & Prof#=EEPHOLLOWBRTR112,Reach-1         , 5
Up Type= 0
Dn Type= 3
Dn Slope=0.02
Boundary for River Rch & Prof#=EEPHOLLOWBRTR112,Reach-1         , 6
Up Type= 0
Dn Type= 3
Dn Slope=0.02
Boundary for River Rch & Prof#=EEPHOLLOWBRTR112,Reach-1         , 7
Up Type= 0
Dn Type= 3
Dn Slope=0.02
DSS Import GetInterval= 0
DSS Import GetPeak= 0
DSS Import FillOption= 0

--- STEEPHOLLOWBRANCH.g01 (geometry) ---

Geom Title=Existing Conditions
Program Version=4.10

River Reach=EEPHOLLOWBRTR112,Reach-1
Reach XY= 30
      3563557.18     10237792.89      3563676.46     10237869.45
      3563779.58      10237860.6      3563824.37     10237825.18
      3563880.45     10237694.97       3563949.2     10237676.22
      3564066.56     10237615.11      3564114.48     10237635.94
      3564220.73      10237540.8      3564294.34     10237501.22
      3564389.48     10237613.03      3564462.18     10237724.96
      3564538.74     10237786.94      3564553.32     10237812.46
      3564572.59     10237820.79      3564639.26     10237805.17
      3564838.22     10237909.86      3564861.66     10237949.44
      3565034.57     10238016.11      3565081.97     10238022.88
      3565171.55     10238116.63      3565245.51       10238226.
      3565411.65     10238269.75      3565428.32     10238295.27
      3565427.28     10238315.07      3565618.43      10238460.9
      3565813.22     10238637.46      3565837.18     10238670.79
      3565840.82     10238731.73      3565862.35     10238751.95

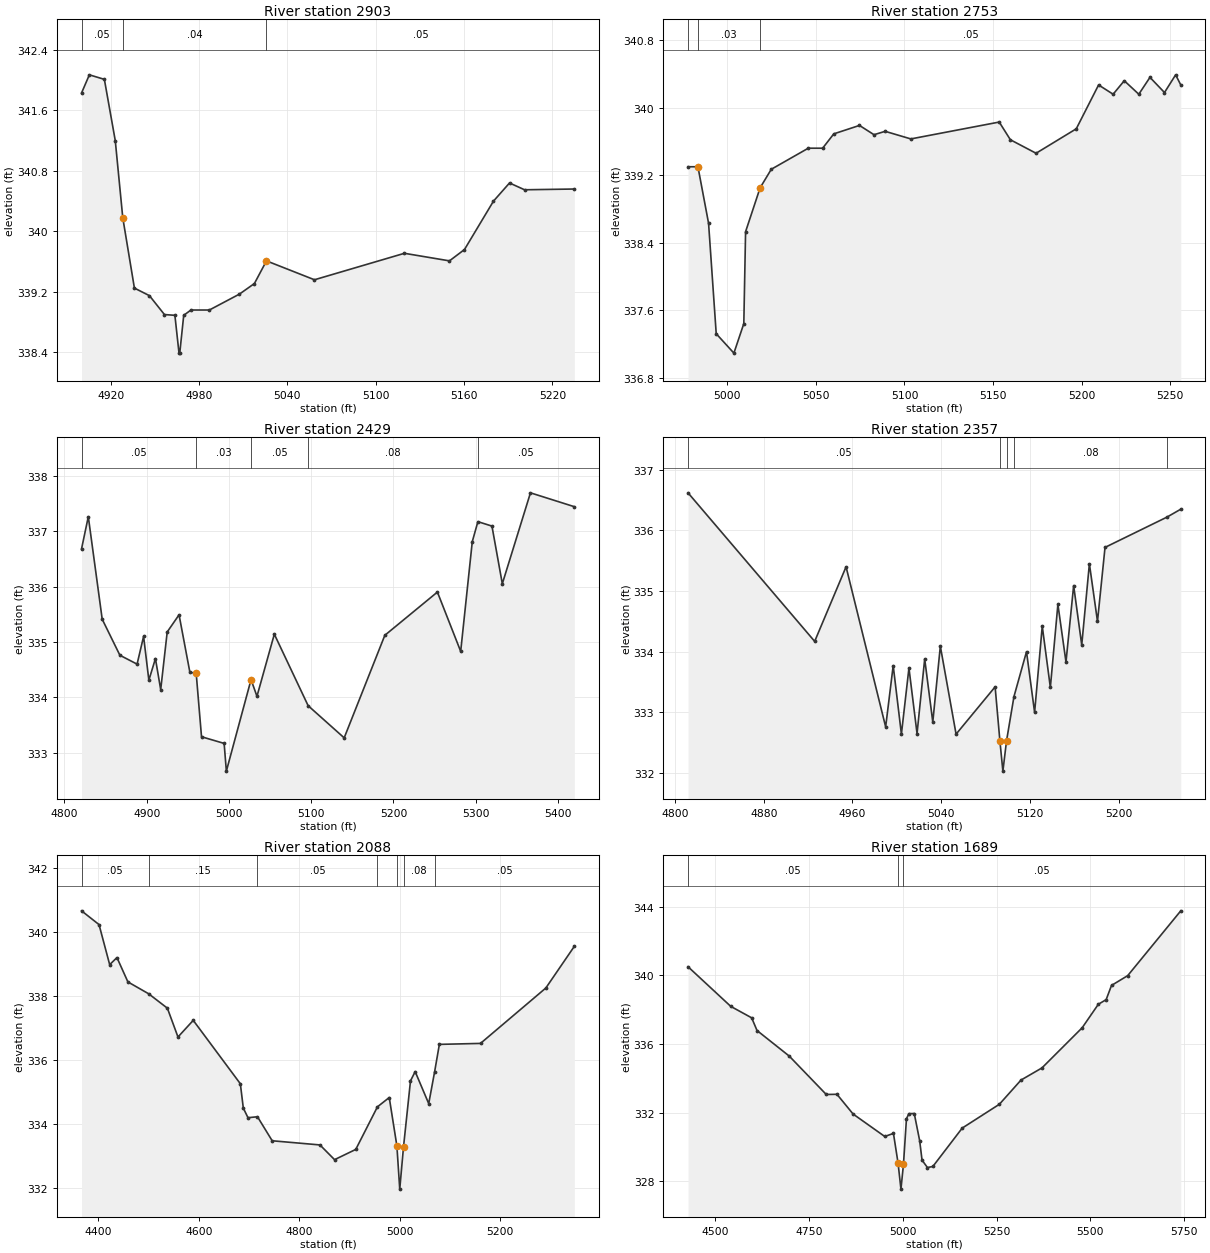
Type RM Length L Ch R = 1 ,2903    ,150,150,150
BEGIN DESCRIPTION:
UNT05239 IN WICK 5.0
END DESCRIPTION:
XS GIS Cut Line= 2
      3563701.96     10237966.84      3563637.36     10237638.43
#Sta/Elev= 25
  4900.2  341.83  4905.5  342.07  4915.7  342.01  4923.1   341.2  4928.2  340.18
  4936.1  339.25  4946.3  339.15  4956.5   338.9  4963.6  338.89  4966.4  338.39
  4966.9  338.39  4969.6  338.89  4974.5  338.96    4987  338.96  5007.4  339.17
  5017.6  339.31  5025.8  339.61  5058.4  339.36  5119.5  339.71  5150.1  339.61
  5160.3  339.76    5180   340.4  5190.9  340.64  5201.1  340.55  5234.9  340.56
#Mann= 3 , 0 , 0
  4900.2     .05       0  4928.2     .04       0  5025.8     .05       0
Bank Sta=4928.2,5025.8
XS Rating Curve= 0 ,0
Exp/Cntr=0.3,0.1

Type RM Length L Ch R = 1 ,2753    ,324,324,324
BEGIN DESCRIPTION:
Mapping XS 662d20bd
END DESCRIPTION:
XS GIS Cut Line= 2
      3563834.52     10237845.46      3563664.97     10237624.89
#Sta/Elev= 28
  4977.8   339.3  4983.4   339.3  4989.4  338.63 4993.72  337.32  5003.7  337.09
  5009.3  337.44  5010.3  338.53  5018.5  339.05  5024.8  339.27  5045.7  339.52
  5053.8  339.52  5060.1  339.69  5074.6  339.79  5082.8  339.68  5089.1  339.72
  5103.6  339.63  5153.5  339.83  5159.8  339.62  5174.3  339.46    5197  339.75
  5209.6  340.27  5217.8  340.16  5224.1  340.32  5232.3  340.16  5238.6  340.36
  5246.8  340.18  5253.1  340.39    5256  340.27
#Mann= 3 , 0 , 0
  4977.8     .05       0  4983.4     .03       0  5018.5     .05       0
Bank Sta=4983.4,5018.5
XS Rating Curve= 0 ,0
Exp/Cntr=0.3,0.1

Type RM Length L Ch R = 1 ,2429    ,72,72,72
BEGIN DESCRIPTION:
Mapping XS 98899efd
END DESCRIPTION:
XS GIS Cut Line= 6
      3563924.85     10237755.49      3563935.28     10237724.19
      3564040.49      10237639.3      3564049.86     10237611.69
      3564262.36     10237409.61      3564291.31     10237305.22
#Sta/Elev= 30
  4820.9  336.68  4829.1  337.26    4846  335.41  4867.5  334.76  4888.4   334.6
  4896.3   335.1  4902.7  334.31  4910.7   334.7  4917.1  334.14    4925  335.18
  4939.4  335.49  4952.6  334.45  4960.2  334.44  4966.7  333.29  4994.2  333.17
  4996.9  332.67  5026.9  334.32  5034.1  334.02  5055.2  335.14  5096.3  333.85
  5140.1  333.27  5189.5  335.12  5253.4   335.9  5281.7  334.83  5295.8  336.81
  5302.6  337.17  5319.7  337.09  5332.3  336.05  5366.5  337.69  5419.8  337.44
#Mann= 5 ,-1 , 0
  4820.9     .05       0  4960.2     .03       0  5026.9     .05       0
  5096.3     .08       0  5302.6     .05       0
Bank Sta=4960.2,5026.9
XS Rating Curve= 0 ,0
Exp/Cntr=0.3,0.1

Type RM Length L Ch R = 1 ,2357    ,269,269,269
BEGIN DESCRIPTION:
Mapping XS 31eddead
END DESCRIPTION:
XS GIS Cut Line= 2
      3563970.79     10237761.95      3564295.05     10237458.21
#Sta/Elev= 30
  4811.7  336.62  4925.9  334.17  4954.2   335.4  4989.9  332.76  4996.7  333.77
  5004.1  332.64  5010.9  333.73  5018.2  332.65  5025.1  333.88  5032.4  332.84
  5039.2  334.09  5053.4  332.64  5088.6  333.42  5092.9  332.53  5095.6  332.03
  5098.9  332.53  5105.6  333.26  5116.9     334  5124.2     333  5131.1  334.42
  5138.4  333.41  5145.2  334.78  5152.5  333.83  5159.4  335.09  5166.7  334.11
  5173.6  335.45  5180.9   334.5  5187.7  335.72  5243.6  336.22    5256  336.35
#Mann= 5 ,-1 , 0
  4811.7     .05       0  5092.9     .04       0  5098.9     .05       0
  5105.6     .08       0  5243.6     .05       0
Bank Sta=5092.9,5098.9
XS Rating Curve= 0 ,0
Exp/Cntr=0.3,0.1

Type RM Length L Ch R = 1 ,2088    ,399,399,399
BEGIN DESCRIPTION:
Mapping XS 83214ece
END DESCRIPTION:
XS GIS Cut Line= 2
      3563975.03     10238060.92      3564505.62     10237235.55
#Sta/Elev= 30
  4366.4  340.67  4401.2  340.24  4422.4  338.99  4436.9  339.21  4458.7  338.45
    4500  338.08  4537.3  337.63  4558.4  336.73  4588.8  337.25  4682.6  335.27
  4688.5  334.51  4697.8  334.21  4716.7  334.24    4746  333.49  4841.1  333.36
  4870.2   332.9  4912.4  333.22  4955.6  334.55  4979.1  334.84  4994.3  333.33
    5000  331.98  5007.5   333.3  5021.4  335.36  5030.7  335.65  5057.7  334.65
  5069.5  335.65  5078.9   336.5  5160.8  336.53  5290.9  338.26  5347.6  339.56
#Mann= 7 ,-1 , 0
  4366.4     .05       0    4500     .15       0  4716.7     .05       0
  4955.6     .08       0  4994.3     .07       0  5007.5     .08       0
  5069.5     .05       0
Bank Sta=4994.3,5007.5
XS Rating Curve= 0 ,0
Exp/Cntr=0.3,0.1

Type RM Length L Ch R = 1 ,1689    ,336,336,336
BEGIN DESCRIPTION:
UNT05239 IN WICK 4.0
END DESCRIPTION:
XS GIS Cut Line= 3
      3564142.07     10238191.67      3564561.74     10237839.17
      3565042.08     10237241.68
#Sta/Elev= 30
  4426.9  340.51  4540.8   338.2  4596.7  337.53    4611  336.79  4696.9   335.3
  4795.7  333.06  4824.3  333.07  4867.3  331.92  4951.8  330.61    4975  330.79
  4987.3  329.06    4995  327.54  5001.7  328.98  5009.7  331.64  5016.1  331.94
  5030.5  331.95  5044.9  330.37  5051.3  329.23  5065.7   328.8  5080.1  328.86
  5158.5   331.1  5257.7  332.49  5315.3   333.9  5371.3  334.61  5478.5  336.95
  5521.6  338.32  5542.5  338.59  5556.8  339.42    5600  339.99  5741.6  343.77
#Mann= 3 , 0 , 0
  4426.9     .05       0  4987.3     .04       0  5001.7     .05       0
Bank Sta=4987.3,5001.7
XS Rating Curve= 0 ,0
Exp/Cntr=0.3,0.1

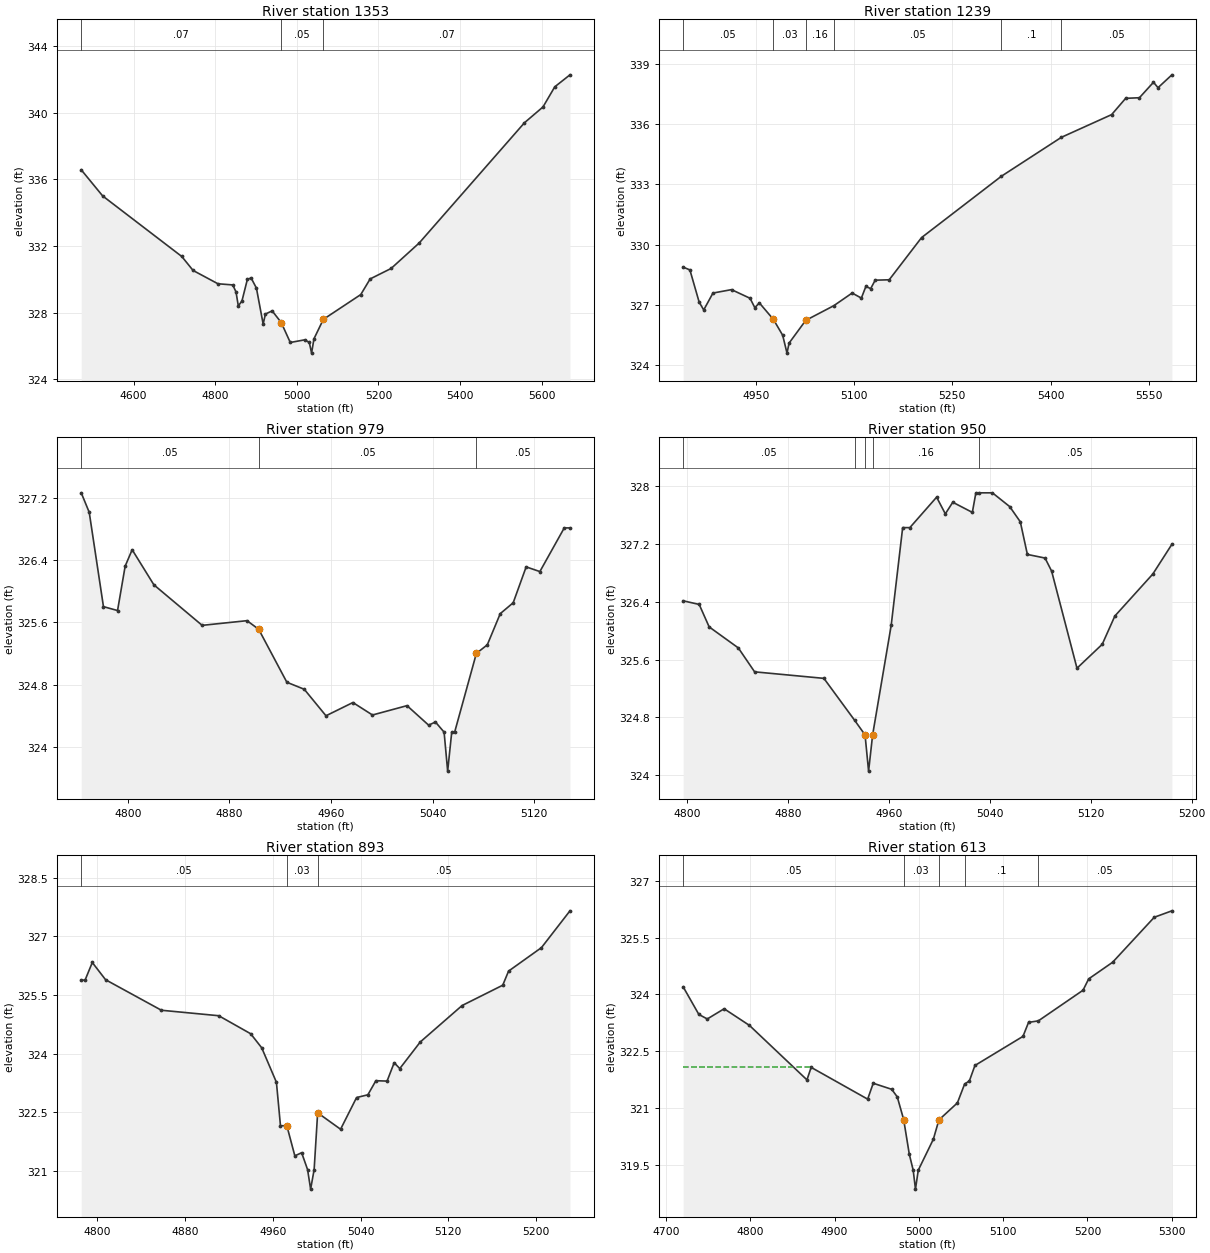
Type RM Length L Ch R = 1 ,1353    ,114,114,114
BEGIN DESCRIPTION:
UNT05239 IN WICK 3.0
END DESCRIPTION:
XS GIS Cut Line= 3
      3564392.14     10238191.63      3564861.66     10237949.44
      3565142.11     10237341.63
#Sta/Elev= 30
  4471.7  336.58  4524.2  335.01  4718.1  331.37  4745.8  330.53  4806.7  329.73
    4843  329.66    4851  329.24  4856.6   328.4  4865.5  328.69  4878.8  329.99
    4888  330.08    4901  329.47  4917.5  327.31  4923.1  327.91  4939.6   328.1
  4961.8   327.4    4984   326.2  5019.6  326.36  5030.6   326.2  5036.2  325.56
    5042  326.42    5065  327.59  5156.7  329.08  5179.7  330.02  5231.1  330.65
  5299.9  332.18  5557.9  339.41  5603.3  340.36  5632.2  341.57  5669.4  342.29
#Mann= 3 , 0 , 0
  4471.7     .07       0  4961.8     .05       0    5065     .07       0
Bank Sta=4961.8,5065
XS Rating Curve= 0 ,0
Exp/Cntr=0.3,0.1

Type RM Length L Ch R = 1 ,1239    ,260,260,260
BEGIN DESCRIPTION:
UNT05239 IN WICK 2.0
END DESCRIPTION:
XS GIS Cut Line= 2
      3564849.25     10238103.33      3565392.11     10237591.64
#Sta/Elev= 30
  4839.2  328.88  4849.5  328.74  4863.6  327.14  4870.6  326.75  4884.7  327.59
    4913  327.76  4941.3  327.33  4948.6  326.86  4955.5   327.1  4976.9  326.28
  4991.1  325.49  4997.7   324.6  5000.9   325.1  5026.3  326.23  5069.1  326.96
  5097.1  327.59  5111.2  327.34  5118.1  327.92  5125.4  327.81  5132.3  328.23
  5153.7  328.25  5203.1  330.35  5324.8   333.4  5416.5  335.34  5493.2  336.47
  5514.6  337.28  5535.6  337.31  5557.1  338.08    5564  337.81  5585.2  338.45
#Mann= 6 ,-1 , 0
  4839.2     .05       0  4976.9     .03       0  5026.3     .16       0
  5069.1     .05       0  5324.8      .1       0  5416.5     .05       0
Bank Sta=4976.9,5026.3
XS Rating Curve= 0 ,0
Exp/Cntr=0.3,0.1

Type RM Length L Ch R = 1 ,979     ,29,29,29
BEGIN DESCRIPTION:
Mapping XS 08a102ac
END DESCRIPTION:
XS GIS Cut Line= 5
       3564966.4     10238231.91      3565146.01     10238144.96
      3565187.67     10238118.92      3565204.34     10238076.73
      3565222.88     10237987.88
#Sta/Elev= 30
  4763.4  327.26  4769.7  327.01  4780.9   325.8    4792  325.75    4798  326.32
  4803.5  326.53  4820.6  326.08  4858.6  325.56  4893.9  325.62  4903.1  325.51
  4925.3  324.83    4939  324.74  4956.1   324.4  4977.3  324.57  4992.7  324.41
  5019.9  324.53  5036.9  324.28  5042.3  324.32  5049.1  324.19  5051.9  323.69
  5055.1  324.19  5057.4  324.19  5074.5   325.2  5083.1  325.31  5093.3  325.71
  5103.5  325.85  5113.7  326.31  5124.5  326.25  5143.7  326.81  5148.2  326.81
#Mann= 3 , 0 , 0
  4763.4     .05       0  4903.1     .05       0  5074.5     .05       0
#XS Ineff= 2 , 0
         4803.52  326.51
Permanent Ineff=
       F       F
Bank Sta=4903.1,5074.5
XS Rating Curve= 0 ,0
Exp/Cntr=0.3,0.1

Type RM Length L Ch R = 1 ,950     ,57,57,57
BEGIN DESCRIPTION:
Mapping XS 591a6b63
END DESCRIPTION:
XS GIS Cut Line= 5
       3565010.5     10238236.07      3565170.79     10238163.68
      3565220.27     10238133.73      3565245.01     10238086.85
      3565251.52     10237986.59
#Sta/Elev= 30
  4797.1  326.41  4809.8  326.36  4817.7  326.05  4840.8  325.76  4853.7  325.43
  4908.6  325.34    4933  324.76  4941.2  324.56    4944  324.06  4947.2  324.56
  4961.9  326.07    4971  327.42  4976.7  327.42  4997.9  327.84  5004.8  327.61
  5010.7  327.77  5026.2  327.63    5029   327.9  5031.1   327.9  5042.1   327.9
  5055.8  327.71  5064.2   327.5  5069.8  327.05  5083.8     327    5089  326.82
  5109.1  325.48  5129.1  325.81  5139.1   326.2  5169.2  326.78  5184.3  327.19
#Mann= 5 ,-1 , 0
  4797.1     .05       0    4933     .16       0  4941.2     .07       0
  4947.2     .16       0  5031.1     .05       0
Bank Sta=4941.2,4947.2
XS Rating Curve= 0 ,0
Exp/Cntr=0.3,0.1

Type RM Length L Ch R = 1 ,893     ,280,280,280
BEGIN DESCRIPTION:
Mapping XS 45eeb038
END DESCRIPTION:
XS GIS Cut Line= 5
      3565020.28     10238249.09       3565200.7     10238215.27
       3565263.2     10238168.92      3565276.74     10238081.42
      3565277.77     10237985.64
#Sta/Elev= 30
  4785.3  325.88  4788.8  325.88  4795.4  326.33  4807.5  325.89  4858.4  325.11
  4910.7  324.97  4939.8  324.51  4949.9  324.15  4963.3  323.27    4967  322.16
  4972.8  322.16  4980.1  321.39  4986.3  321.47  4991.7  321.04  4994.5  320.54
  4997.7  321.04  5000.9  322.49  5021.8  322.07  5036.4  322.88  5046.7  322.95
    5054  323.31  5064.2   323.3  5070.7  323.77  5075.8  323.62  5094.5   324.3
  5132.6  325.23  5169.7  325.75    5175  326.11    5205  326.71    5231  327.65
#Mann= 3 , 0 , 0
  4785.3     .05       0  4972.8     .03       0  5000.9     .05       0
Bank Sta=4972.8,5000.9
XS Rating Curve= 0 ,0
Exp/Cntr=0.3,0.1

Type RM Length L Ch R = 1 ,613     ,63,63,63
BEGIN DESCRIPTION:
Mapping XS 2ae28567
END DESCRIPTION:
XS GIS Cut Line= 3
      3565183.52     10238373.63      3565387.44     10238377.73
      3565670.79     10238131.12
#Sta/Elev= 30
  4720.5   324.2  4739.1  323.47  4749.1  323.35  4769.1  323.62  4799.1  323.18
  4867.3  321.74  4872.3  322.07  4939.3  321.23  4945.9  321.65  4967.8  321.49
  4974.4  321.29    4982  320.69  4988.7  319.77  4993.3  319.35    4996  318.85
  4999.3  319.35  5017.2  320.17  5023.8  320.68  5045.7  321.13  5054.3  321.63
  5059.9  321.71  5066.5  322.12  5123.5  322.89  5130.1  323.26  5141.7   323.3
  5194.7  324.11  5201.4  324.41  5229.8  324.85  5279.2  326.04  5300.1  326.21
#Mann= 5 ,-1 , 0
  4720.5     .05       0    4982     .03       0  5023.8     .05       0
  5054.3      .1       0  5141.7     .05       0
#XS Ineff= 2 , 0
         4873.52  322.08
Permanent Ineff=
       F       F
Bank Sta=4982,5023.8
XS Rating Curve= 0 ,0
Exp/Cntr=0.3,0.1

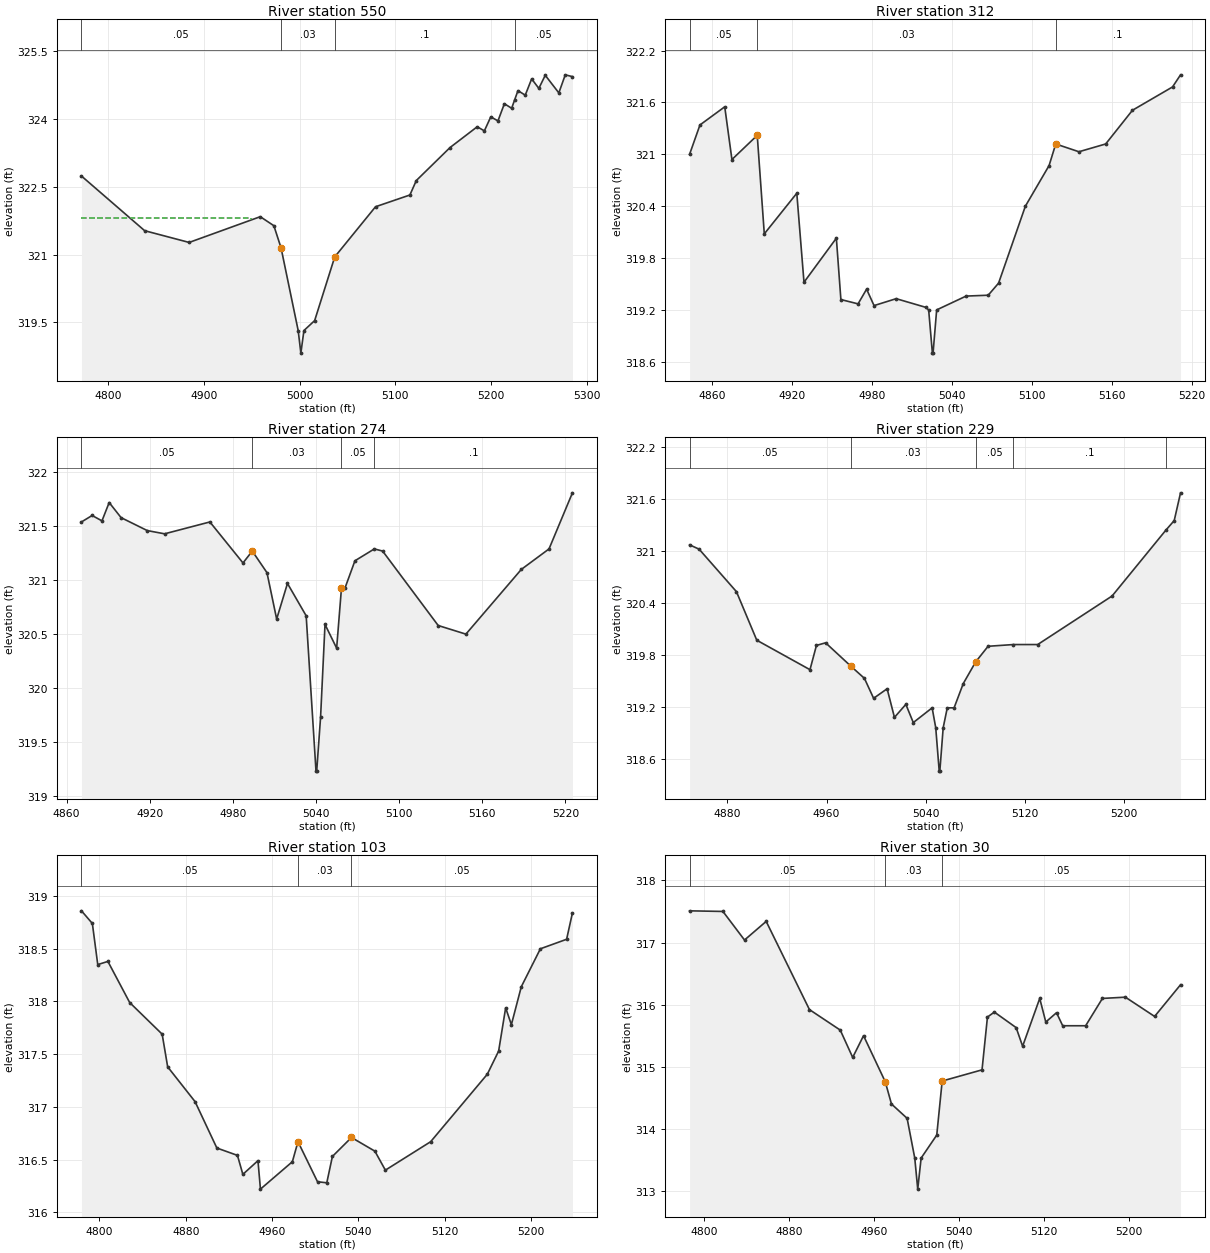
Type RM Length L Ch R = 1 ,550     ,238,238,238
BEGIN DESCRIPTION:
Mapping XS 532c7fac
END DESCRIPTION:
XS GIS Cut Line= 3
      3565286.12     10238414.27      3565437.21     10238417.41
      3565707.77     10238177.25
#Sta/Elev= 30
  4772.1  322.74  4838.1  321.53  4884.6  321.27  4958.9  321.84  4973.1  321.64
  4980.6  321.15  4998.5  319.32  5001.3  318.82  5004.5  319.32  5015.7  319.54
  5036.7  320.95  5079.3  322.06  5115.2  322.32  5121.9  322.64  5157.1  323.37
  5185.5  323.83    5193  323.74  5199.7  324.05  5207.2  323.96  5213.9  324.34
  5221.5  324.24  5224.7  324.43  5228.1  324.63  5235.7  324.53  5242.4  324.89
  5249.9  324.68  5256.6  324.97  5270.8  324.58  5277.5  324.98    5285  324.94
#Mann= 4 ,-1 , 0
  4772.1     .05       0  4980.6     .03       0  5036.7      .1       0
  5224.7     .05       0
#XS Ineff= 2 , 0
          4949.3  321.82
Permanent Ineff=
       F       F
Bank Sta=4980.6,5036.7
XS Rating Curve= 0 ,0
Exp/Cntr=0.3,0.1

Type RM Length L Ch R = 1 ,312     ,38,38,38
BEGIN DESCRIPTION:
Mapping XS 51801433
END DESCRIPTION:
XS GIS Cut Line= 5
      3565534.82     10238577.27      3565643.36     10238534.32
      3565706.29     10238502.21      3565722.35     10238472.26
        3565736.     10238325.66
#Sta/Elev= 30
    4843     321  4850.8  321.34  4869.4  321.55  4874.8  320.94  4893.8  321.22
  4899.1  320.08  4923.5  320.55  4928.9  319.52  4953.2  320.03  4956.6  319.32
  4969.5  319.27  4975.9  319.44  4981.5  319.25  4998.1  319.33  5020.3  319.23
  5022.5   319.2  5025.3   318.7  5025.8   318.7  5028.5   319.2  5050.6  319.36
  5067.2  319.37    5075  319.51  5095.1   320.4  5112.9  320.87  5117.9  321.12
  5135.3  321.03  5155.4  321.12  5175.5  321.51  5205.6  321.78  5211.6  321.92
#Mann= 3 , 0 , 0
    4843     .05       0  4893.8     .03       0  5117.9      .1       0
Bank Sta=4893.8,5117.9
XS Rating Curve= 0 ,0
Exp/Cntr=0.3,0.1

Type RM Length L Ch R = 1 ,274     ,45,45,45
BEGIN DESCRIPTION:
Mapping XS cdff9900
END DESCRIPTION:
XS GIS Cut Line= 5
      3565584.74     10238581.54      3565673.39      10238554.3
      3565720.27     10238537.38      3565747.61     10238500.92
      3565752.71     10238334.75
#Sta/Elev= 29
  4870.7  321.54  4878.4   321.6  4885.5  321.55  4890.7  321.72  4899.3  321.58
  4918.2  321.46  4930.7  321.43  4963.4  321.54  4987.3  321.16    4994  321.27
  5004.6  321.07  5011.6  320.64  5019.4  320.97  5032.9  320.67    5040  319.23
  5040.5  319.23  5043.3  319.73  5046.5  320.59  5054.9  320.37  5058.4  320.93
    5061  320.93  5068.1  321.18  5082.1  321.29  5088.1  321.27  5128.2  320.58
  5148.2   320.5  5188.2   321.1  5208.2  321.29  5225.1  321.81
#Mann= 4 ,-1 , 0
  4870.7     .05       0    4994     .03       0  5058.4     .05       0
  5082.1      .1       0
Bank Sta=4994,5058.4
XS Rating Curve= 0 ,0
Exp/Cntr=0.3,0.1

Type RM Length L Ch R = 1 ,229     ,126,126,126
BEGIN DESCRIPTION:
Mapping XS 35267d82
END DESCRIPTION:
XS GIS Cut Line= 5
      3565594.39     10238594.05      3565658.19     10238597.03
      3565741.17     10238572.16      3565773.92      10238521.3
      3565767.36      10238336.5
#Sta/Elev= 30
  4849.5  321.07  4857.2  321.02  4887.3  320.53  4903.7  319.97  4946.6  319.63
  4951.8  319.91  4959.2  319.94  4979.6  319.67  4990.5  319.53  4997.9   319.3
  5008.8  319.41  5014.7  319.08  5023.9  319.23  5029.9  319.02  5045.1  319.19
    5048  318.96  5050.8  318.46  5051.3  318.46    5054  318.96  5057.3  319.19
  5062.8  319.19  5070.2  319.47  5080.2  319.72  5090.2   319.9  5110.6  319.92
  5130.2  319.92  5190.2  320.48  5233.6  321.24  5240.3  321.35  5245.4  321.67
#Mann= 5 ,-1 , 0
  4849.5     .05       0  4979.6     .03       0  5080.2     .05       0
  5110.6      .1       0  5233.6     .05       0
Bank Sta=4979.6,5080.2
XS Rating Curve= 0 ,0
Exp/Cntr=0.3,0.1

Type RM Length L Ch R = 1 ,103     ,73,73,73
BEGIN DESCRIPTION:
Mapping XS 6b98e2c4
END DESCRIPTION:
XS GIS Cut Line= 4
       3565617.9     10238655.07      3565776.78      10238678.4
      3565878.38     10238645.23       3565935.6     10238466.53
#Sta/Elev= 30
  4783.3  318.86  4793.4  318.74  4798.4  318.35  4807.8  318.38    4828  317.99
  4858.1  317.69  4863.2  317.38  4888.6  317.05  4908.8  316.61  4927.9  316.54
  4932.9  316.36  4946.9  316.49  4949.2  316.22  4978.8  316.48    4984  316.67
  5002.1  316.29  5010.7  316.28  5015.9  316.53  5033.6  316.71  5055.3  316.58
    5065   316.4    5107  316.67  5159.5  317.31    5170  317.53  5176.5  317.94
  5181.8  317.78    5191  318.14  5208.7   318.5    5233  318.59  5238.4  318.84
#Mann= 3 , 0 , 0
  4783.3     .05       0    4984     .03       0  5033.6     .05       0
Bank Sta=4984,5033.6
XS Rating Curve= 0 ,0
Exp/Cntr=0.3,0.1

Type RM Length L Ch R = 1 ,30      ,0,0,0
BEGIN DESCRIPTION:
UNT05239 IN WICK 1.0
END DESCRIPTION:
XS GIS Cut Line= 4
      3565631.29     10238709.68       3565798.6     10238741.27
      3565938.88     10238708.63      3566012.24     10238580.43
#Sta/Elev= 30
  4786.4  317.51  4817.8   317.5  4838.1  317.04  4858.5  317.34  4899.2  315.92
  4928.2  315.59  4939.9  315.15  4950.1   315.5  4970.5  314.76  4976.4   314.4
  4991.1  314.17  4998.3  313.53  5001.1  313.03  5004.3  313.53    5019   313.9
  5024.1  314.77  5061.6  314.95  5066.7   315.8  5073.2  315.88  5093.7  315.63
  5099.8  315.33  5115.9   316.1  5121.6  315.72  5131.7  315.87  5137.5  315.66
  5159.1  315.66  5174.9   316.1  5196.5  316.12    5224  315.81  5248.4  316.32
#Mann= 3 , 0 , 0
  4786.4     .05       0  4970.5     .03       0  5024.1     .05       0
Bank Sta=4970.5,5024.1
XS Rating Curve= 0 ,0
Exp/Cntr=0.3,0.1

Chan Stop Cuts=-1
Use User Specified Reach Order=0
Composite Channel Slope=5