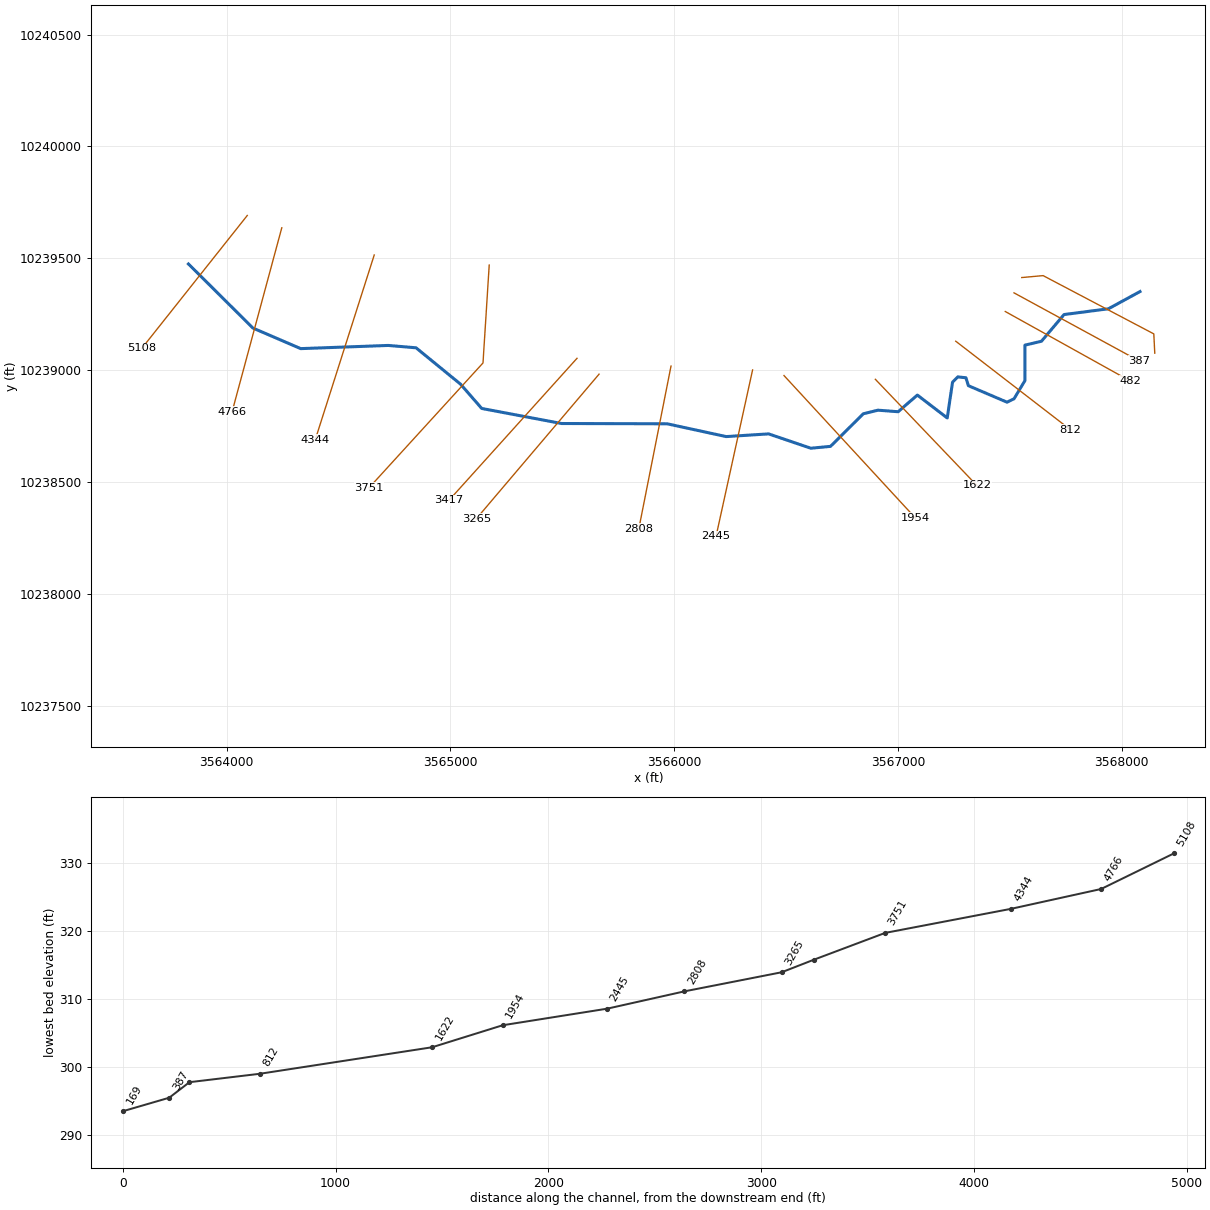
--- STEEPHOLLOWBRANCH.prj (project) ---

Proj Title=STEEP HOLLOW BRANCH TRIB 11
Current Plan=p01
Default Exp/Contr=0.3,0.1
English Units
Geom File=g01
Flow File=f01
Plan File=p01
Y Axis Title=Elevation
X Axis Title(PF)=Main Channel Distance
X Axis Title(XS)=Station
BEGIN DESCRIPTION:
UNT0504 IN WICK
END DESCRIPTION:
DSS Export Rating Curves= 0
DSS Export Rating Curve Sorted= 0
DSS Export Volume Flow Curves= 0
DXF Filename=UNT0504 IN WICK.
DXF OffsetX= 0
DXF OffsetY= 0
DXF ScaleX= 1
DXF ScaleY= 10

--- STEEPHOLLOWBRANCH.p01 (plan) ---

Plan Title=Multiple Run
Short Identifier=Multiple
Geom File=g01
Flow File=f01
Subcritical Flow
K Sum by GR= 0
Std Step Tol= 0.01
Critical Tol= 0.01
Num of Std Step Trials= 20
Max Error Tol= 0.3
Flow Tol Ratio= 0.001
Split Flow NTrial= 30
Split Flow Tol= 0.02
Split Flow Ratio= 0.02
Log Output Level= 0
Friction Slope Method= 1
Unsteady Friction Slope Method= 2
Unsteady Bridges Friction Slope Method= 1
Parabolic Critical Depth
Global Vel Dist=  1 , 1 , 1
Global Log Level= 0
CheckData=True
Encroach Param= -1, 0, 0, 0
BEGIN DESCRIPTION:
Multiple Run
END DESCRIPTION:

--- STEEPHOLLOWBRANCH.f01 (steady flow) ---

Flow Title=Multiple
Program Version=4.10
Number of Profiles= 7
Profile Names=10-year,25-year,50-year,1pct_min,100-year,1pct_plu,500-year
River Rch & RM=UNT0504 IN WICK,Reach-1         ,5108
     152     188     215     181     245     331     316
River Rch & RM=UNT0504 IN WICK,Reach-1         ,2808
     249     319     373     321     434     587     587
River Rch & RM=UNT0504 IN WICK,Reach-1         ,1954
     333     434     513     447     604     817     836
River Rch & RM=TEEPHOLLOWBRTR11,Reach-1         ,5108
     152     188     215     181     245     331     316
River Rch & RM=TEEPHOLLOWBRTR11,Reach-1         ,2808
     249     319     373     321     434     587     587
River Rch & RM=TEEPHOLLOWBRTR11,Reach-1         ,1954
     333     434     513     447     604     817     836
Boundary for River Rch & Prof#=TEEPHOLLOWBRTR11,Reach-1         , 1
Up Type= 0
Dn Type= 3
Dn Slope=0.005
Boundary for River Rch & Prof#=TEEPHOLLOWBRTR11,Reach-1         , 2
Up Type= 0
Dn Type= 3
Dn Slope=0.005
Boundary for River Rch & Prof#=TEEPHOLLOWBRTR11,Reach-1         , 3
Up Type= 0
Dn Type= 3
Dn Slope=0.005
Boundary for River Rch & Prof#=TEEPHOLLOWBRTR11,Reach-1         , 4
Up Type= 0
Dn Type= 3
Dn Slope=0.005
Boundary for River Rch & Prof#=TEEPHOLLOWBRTR11,Reach-1         , 5
Up Type= 0
Dn Type= 3
Dn Slope=0.005
Boundary for River Rch & Prof#=TEEPHOLLOWBRTR11,Reach-1         , 6
Up Type= 0
Dn Type= 3
Dn Slope=0.005
Boundary for River Rch & Prof#=TEEPHOLLOWBRTR11,Reach-1         , 7
Up Type= 0
Dn Type= 3
Dn Slope=0.005
DSS Import GetInterval= 0
DSS Import GetPeak= 0
DSS Import FillOption= 0

--- STEEPHOLLOWBRANCH.g01 (geometry) ---

Geom Title=Existing Conditions
Program Version=4.10

River Reach=TEEPHOLLOWBRTR11,Reach-1
Reach XY= 30
      3563829.21     10239474.91      3564117.26     10239188.57
      3564330.81     10239096.56      3564722.29     10239110.82
      3564846.45     10239100.27      3565045.83     10238937.27
      3565139.83      10238829.2      3565496.81     10238761.86
      3565968.66     10238760.65      3566232.48     10238703.42
      3566422.01     10238715.55      3566610.84      10238651.4
      3566698.69     10238659.71      3566845.34     10238805.42
      3566910.95     10238821.44        3567001.     10238814.54
      3567086.98     10238888.98      3567220.49     10238786.62
      3567244.18     10238946.68      3567267.65     10238970.16
      3567303.98     10238966.38      3567314.96     10238930.98
      3567487.49     10238857.19      3567518.96     10238872.39
      3567567.78     10238953.77      3567567.78     10239112.19
      3567641.57     10239129.55      3567742.48      10239248.9
      3567940.85     10239274.64      3568082.11     10239351.64

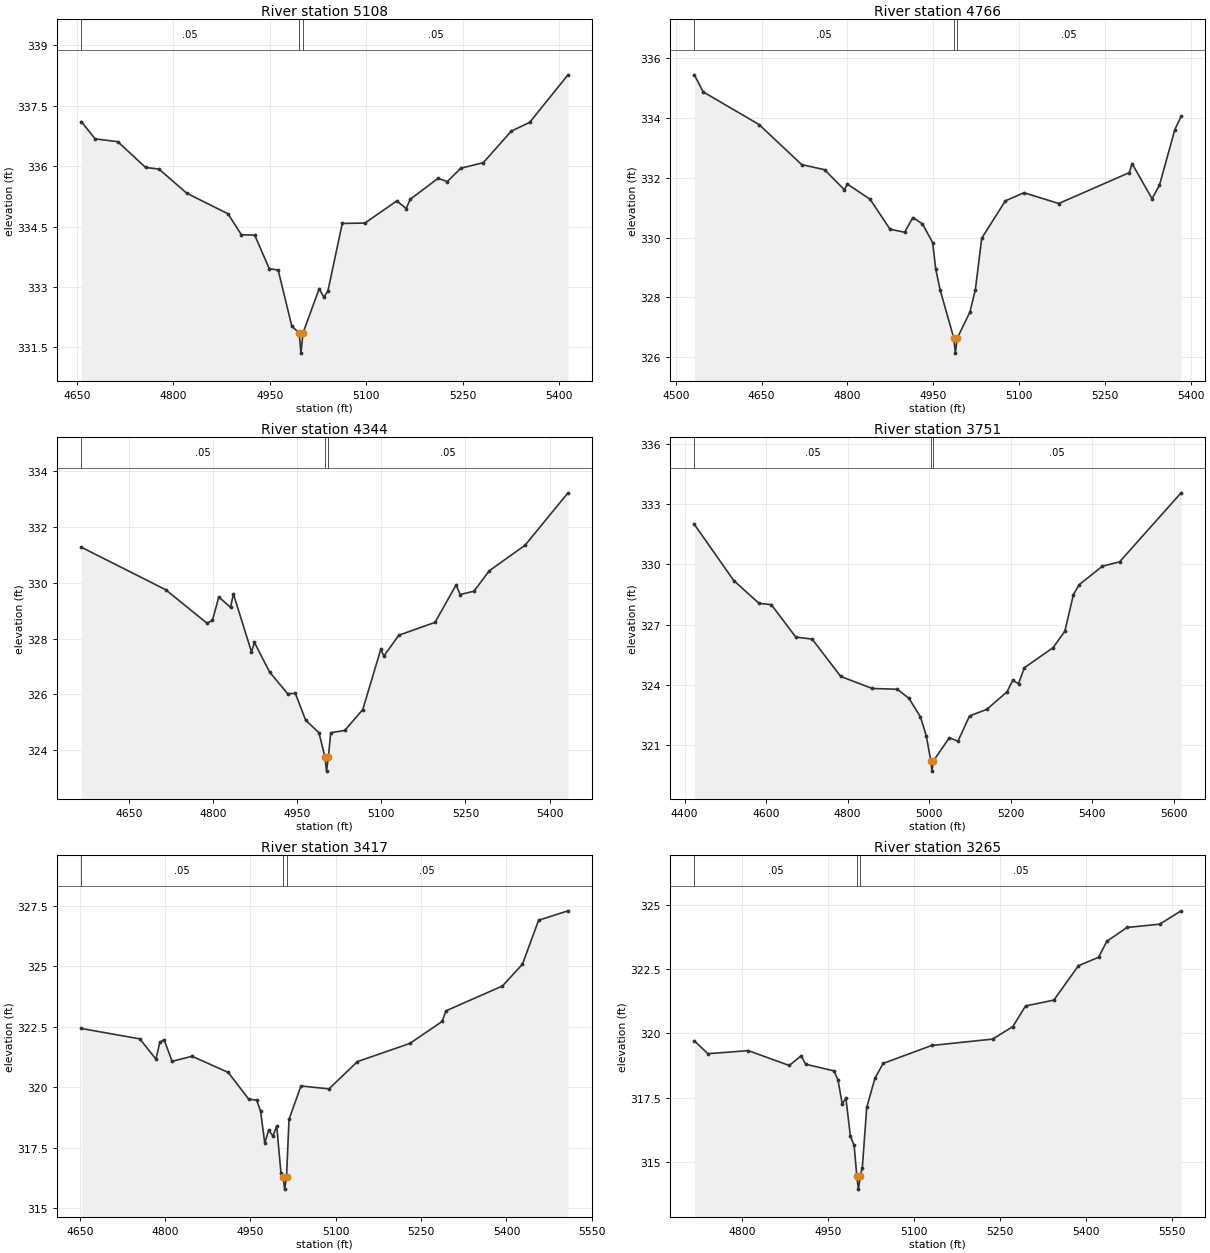
Type RM Length L Ch R = 1 ,5108    ,342,342,342
BEGIN DESCRIPTION:
UNT0504 IN WICK 11.0
END DESCRIPTION:
XS GIS Cut Line= 2
      3564092.08     10239691.61      3563621.32     10239098.41
#Sta/Elev= 30
  4656.6  337.11  4678.2  336.68  4713.4  336.61  4756.7  335.97  4777.5  335.93
  4820.8  335.33  4884.9  334.82  4905.7   334.3  4926.5  334.29    4949  333.46
    4963  333.42  4984.2  332.03  4995.6  331.86  4998.4  331.36  5001.6  331.86
  5026.8  332.96  5033.9  332.75  5040.3   332.9  5062.7  334.58    5098  334.59
  5147.6  335.14  5162.1  334.95  5168.4  335.18  5211.7   335.7  5226.1  335.62
    5247  335.95  5282.2  336.09  5325.5  336.87  5354.3  337.09  5413.9  338.27
#Mann= 3 ,-1 , 0
  4656.6     .05       0  4995.6     .03       0  5001.6     .05       0
Bank Sta=4995.6,5001.6
XS Rating Curve= 0 ,0
Exp/Cntr=0.3,0.1

Type RM Length L Ch R = 1 ,4766    ,422,422,422
BEGIN DESCRIPTION:
UNT0504 IN WICK 10.0
END DESCRIPTION:
XS GIS Cut Line= 2
      3564246.35     10239636.65      3564024.51     10238815.17
#Sta/Elev= 30
  4532.4  335.44  4547.9  334.87  4645.5  333.78  4720.1  332.44    4760  332.27
  4794.7   331.6  4799.9  331.79  4839.8  331.28  4874.5  330.28  4900.1  330.18
  4914.4  330.67  4931.2  330.46  4949.1  329.83  4954.3  328.96  4962.3  328.24
    4986  326.64  4988.7  326.14    4992  326.64  5014.1  327.51  5023.7  328.26
  5034.8  329.98  5076.2  331.23  5108.7   331.5  5169.4  331.14  5292.6  332.17
  5297.8  332.47  5332.5   331.3  5345.5  331.75  5372.4  333.61  5383.3  334.05
#Mann= 3 ,-1 , 0
  4532.4     .05       0    4986     .03       0    4992     .05       0
Bank Sta=4986,4992
XS Rating Curve= 0 ,0
Exp/Cntr=0.3,0.1

Type RM Length L Ch R = 1 ,4344    ,593,593,593
BEGIN DESCRIPTION:
UNT0504 IN WICK 9.0
END DESCRIPTION:
XS GIS Cut Line= 2
      3564659.55     10239515.15      3564395.66     10238688.76
#Sta/Elev= 30
  4565.4  331.28    4716  329.75  4789.5  328.55  4799.2  328.65  4810.5  329.49
  4831.4  329.12  4836.6   329.6  4868.8  327.52    4874  327.86    4901   326.8
  4933.2  326.02    4947  326.03  4965.3  325.07    4989  324.62  4999.8  323.74
  5002.5  323.24  5005.8  323.74    5010  324.62    5035   324.7  5067.1  325.45
  5099.3  327.62  5104.6  327.37  5131.5  328.12  5195.9  328.58  5233.3  329.92
  5240.9  329.58  5265.5   329.7  5292.4  330.43  5356.4  331.35  5432.9  333.23
#Mann= 3 ,-1 , 0
  4565.4     .05       0  4999.8     .03       0  5005.8     .05       0
Bank Sta=4999.8,5005.8
XS Rating Curve= 0 ,0
Exp/Cntr=0.3,0.1

Type RM Length L Ch R = 1 ,3751    ,334,334,334
BEGIN DESCRIPTION:
UNT0504 IN WICK 8.0
END DESCRIPTION:
XS GIS Cut Line= 3
      3565173.43     10239470.03      3565145.65     10239032.48
      3564636.19      10238474.5
#Sta/Elev= 30
  4423.8     332  4520.5   329.2  4582.5  328.06  4612.6     328  4672.7  326.38
  4712.8  326.28  4782.9  324.42  4860.1  323.82  4921.8  323.78  4950.2  323.33
  4978.6   322.4  4992.8  321.46    5004   320.2  5006.7   319.7    5010   320.2
  5049.5  321.37  5070.5  321.19  5098.9  322.45  5141.4  322.78  5190.7  323.65
  5204.9  324.22  5219.1  324.06  5233.3  324.85  5304.2  325.86  5332.6  326.67
  5353.6  328.49  5367.7  328.99  5424.5  329.91    5467  330.13  5617.8  333.57
#Mann= 3 ,-1 , 0
  4423.8     .05       0    5004     .03       0    5010     .05       0
Bank Sta=5004,5010
XS Rating Curve= 0 ,0
Exp/Cntr=0.3,0.1

Type RM Length L Ch R = 1 ,3417    ,152,152,152
BEGIN DESCRIPTION:
Mapping XS b2426032
END DESCRIPTION:
XS GIS Cut Line= 2
      3565565.79     10239053.31      3564992.85     10238417.87
#Sta/Elev= 30
  4652.6  322.43  4755.5     322  4783.9  321.16  4790.6  321.85  4798.1  321.97
  4812.3  321.07  4847.4  321.28    4911  320.61  4946.8  319.51    4961  319.46
  4967.8  319.01  4975.2  317.68    4982  318.22  4989.4  317.98  4996.2  318.39
  5003.6  316.46  5007.4  316.28  5010.1  315.78  5013.4  316.28  5017.8  318.67
  5038.8  320.05  5088.1  319.93  5138.1  321.06  5230.1  321.81  5286.9  322.72
  5293.6  323.16    5393  324.19  5428.1  325.09  5456.5  326.91  5508.2   327.3
#Mann= 3 ,-1 , 0
  4652.6     .05       0  5007.4     .04       0  5013.4     .05       0
Bank Sta=5007.4,5013.4
XS Rating Curve= 0 ,0
Exp/Cntr=0.3,0.1

Type RM Length L Ch R = 1 ,3265    ,457,457,457
BEGIN DESCRIPTION:
UNT0504 IN WICK 7.0
END DESCRIPTION:
XS GIS Cut Line= 2
      3565664.42     10238982.57      3565115.28      10238335.6
#Sta/Elev= 30
  4717.3  319.71  4741.1  319.21  4811.4  319.33  4882.8  318.75  4903.6  319.13
  4911.4   318.8  4960.8  318.54  4967.7  318.19  4975.1  317.26  4981.6  317.47
  4989.4  315.99  4995.9  315.64  5000.6  314.43  5003.4  313.93  5006.6  314.43
  5010.2  314.77  5017.9  317.12  5032.2  318.25  5046.4  318.83    5131  319.53
  5237.6  319.78  5272.7  320.27  5294.7  321.07  5344.1   321.3    5387  322.64
  5422.1  322.97  5436.4  323.59  5471.5  324.13  5528.7  324.26  5565.9  324.78
#Mann= 3 , 0 , 0
  4717.3     .05       0  5000.6     .04       0  5006.6     .05       0
Bank Sta=5000.6,5006.6
XS Rating Curve= 0 ,0
Exp/Cntr=0.3,0.1

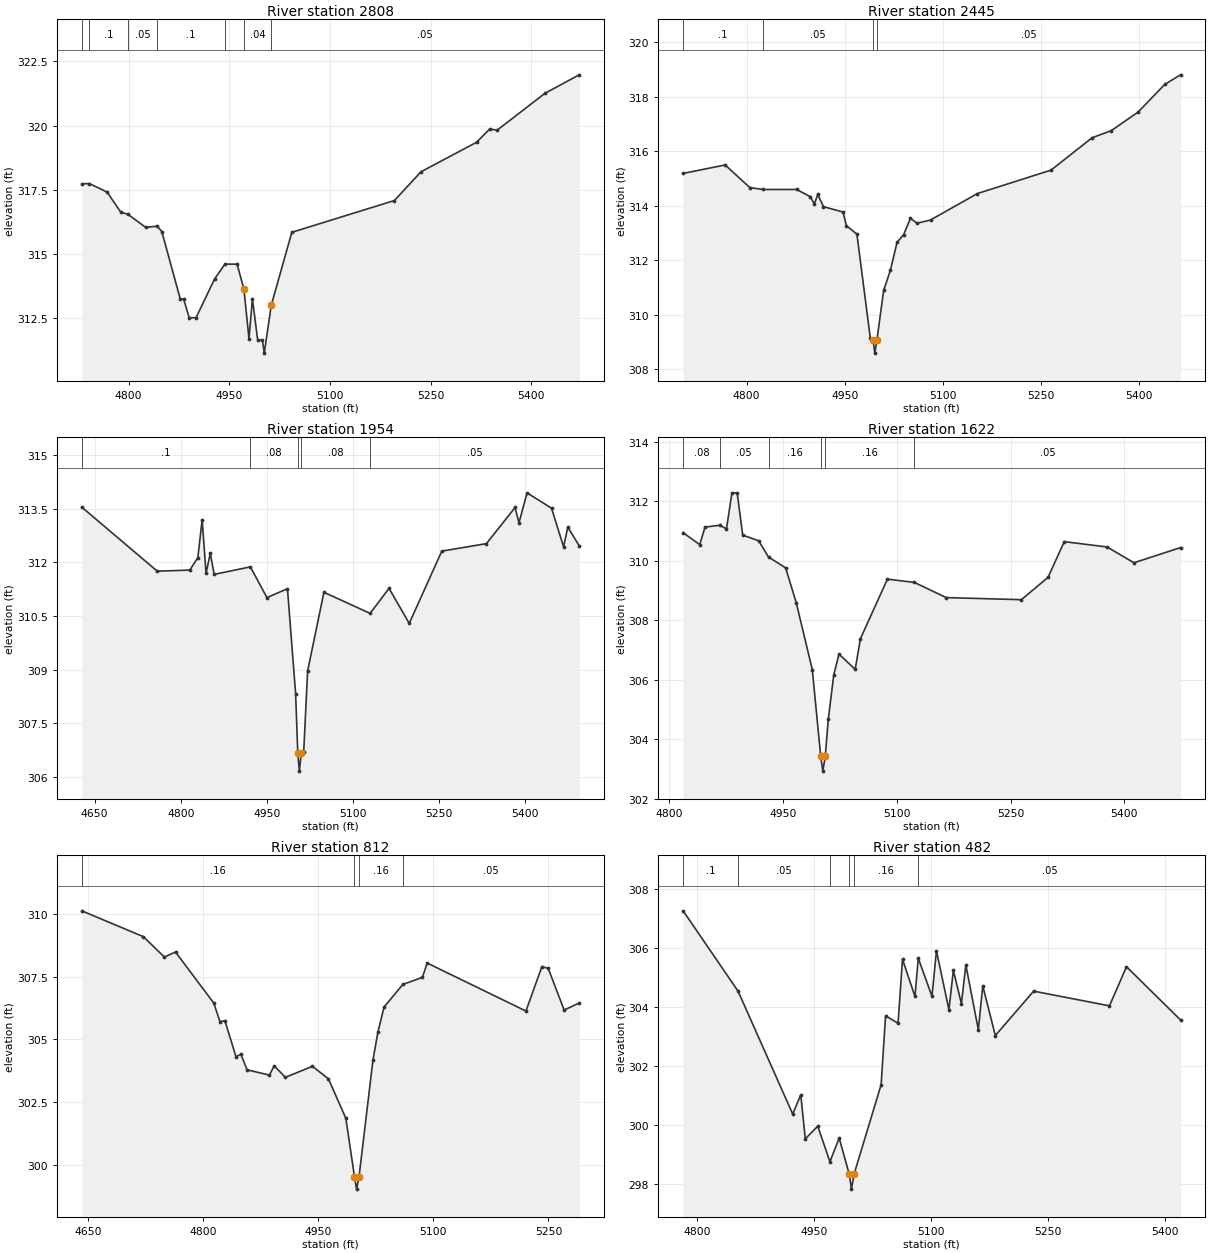
Type RM Length L Ch R = 1 ,2808    ,363,363,363
BEGIN DESCRIPTION:
UNT0504 IN WICK 6.0
END DESCRIPTION:
XS GIS Cut Line= 2
      3565985.93     10239018.56      3565842.11     10238291.65
#Sta/Elev= 30
  4730.2  317.73  4741.6  317.74  4767.8  317.41  4788.2  316.63  4799.1  316.54
  4825.5  316.03  4842.6  316.08  4849.4  315.87  4876.8  313.25  4881.9  313.24
  4890.2  312.51  4900.4  312.51    4928  314.02  4943.5   314.6  4961.5   314.6
  4971.7  313.63  4979.3  311.69  4984.4  313.25  4992.1  311.66  4999.3  311.63
    5002  311.13  5012.5     313  5043.1  315.84    5196  317.08  5235.5   318.2
  5318.3  319.35    5338  319.87  5348.9  319.82  5420.2  321.26  5471.2  321.98
#Mann= 7 ,-1 , 0
  4730.2     .05       0  4741.6      .1       0  4799.1     .05       0
  4842.6      .1       0  4943.5     .05       0  4971.7     .04       0
  5012.5     .05       0
Bank Sta=4971.7,5012.5
XS Rating Curve= 0 ,0
Exp/Cntr=0.3,0.1

Type RM Length L Ch R = 1 ,2445    ,491,491,491
BEGIN DESCRIPTION:
Mapping XS b7b4798f
END DESCRIPTION:
XS GIS Cut Line= 2
      3566350.52     10239001.23      3566187.31     10238258.15
#Sta/Elev= 30
  4702.9  315.19  4767.2   315.5  4804.9  314.67    4825   314.6  4876.5   314.6
    4897  314.34  4903.7  314.07  4908.8  314.42  4917.5  313.97  4947.5  313.77
  4952.6  313.27  4968.7  312.96  4989.2  309.14  4993.4  309.09  4996.1  308.59
  4999.4  309.09  5009.6  310.89  5019.9  311.63  5030.1  312.66  5040.2  312.94
  5050.6  313.54  5060.8  313.36  5081.3  313.48    5153  314.45  5265.6  315.31
  5328.5   316.5  5357.7  316.76  5398.7  317.44  5439.6  318.46  5463.7  318.81
#Mann= 4 ,-1 , 0
  4702.9      .1       0    4825     .05       0  4993.4     .03       0
  4999.4     .05       0
Bank Sta=4993.4,4999.4
XS Rating Curve= 0 ,0
Exp/Cntr=0.3,0.1

Type RM Length L Ch R = 1 ,1954    ,332,332,332
BEGIN DESCRIPTION:
Mapping XS 3fab1043
END DESCRIPTION:
XS GIS Cut Line= 2
      3566490.89     10238976.28      3567078.26     10238339.52
#Sta/Elev= 30
  4627.6  313.54    4759  311.75  4815.7  311.78  4829.8  312.13  4837.2  313.19
    4844  311.69  4851.4  312.25  4858.2  311.66  4921.2  311.87  4950.1  311.01
  4985.8  311.26    5000  308.33  5003.8  306.66  5006.5  306.16  5009.8  306.66
  5014.1   306.7  5020.9  308.96  5049.3  311.16  5129.8  310.57  5162.7  311.27
  5197.9  310.29  5254.6  312.31  5332.3  312.52  5382.2  313.53    5389   313.1
  5403.1  313.94  5445.7  313.51  5466.7  312.43    5474  312.98  5493.9  312.46
#Mann= 5 ,-1 , 0
  4627.6      .1       0  4921.2     .08       0  5003.8     .07       0
  5009.8     .08       0  5129.8     .05       0
Bank Sta=5003.8,5009.8
XS Rating Curve= 0 ,0
Exp/Cntr=0.3,0.1

Type RM Length L Ch R = 1 ,1622    ,810,810,810
BEGIN DESCRIPTION:
UNT0504 IN WICK 5.0
END DESCRIPTION:
XS GIS Cut Line= 2
      3566899.13     10238959.56      3567352.63     10238485.29
#Sta/Elev= 30
    4818  310.94  4839.9  310.54  4846.9  311.13  4866.3  311.19  4875.2  311.07
  4882.4  312.28  4889.3  312.28  4896.6  310.86  4917.6  310.67  4930.7  310.12
  4953.2  309.76  4967.3  308.58  4988.4  306.34  4999.5  303.43  5002.3  302.93
  5005.5  303.43  5009.5  304.67  5016.7  306.16  5023.6  306.86    5045  306.35
  5051.9  307.38  5087.5  309.38    5123  309.27  5165.1  308.76  5264.2  308.69
  5299.4  309.44  5320.8  310.64  5377.4  310.46  5412.7  309.93  5474.2  310.44
#Mann= 6 ,-1 , 0
    4818     .08       0  4866.3     .05       0  4930.7     .16       0
  4999.5     .07       0  5005.5     .16       0    5123     .05       0
Bank Sta=4999.5,5005.5
XS Rating Curve= 0 ,0
Exp/Cntr=0.3,0.1

Type RM Length L Ch R = 1 ,812     ,330,330,330
BEGIN DESCRIPTION:
Mapping XS 58bf7398
END DESCRIPTION:
XS GIS Cut Line= 2
       3567258.5     10239129.71      3567771.53     10238733.86
#Sta/Elev= 30
    4642  310.12  4722.3  309.09  4749.6  308.28  4764.1  308.48  4813.9  306.45
  4822.1   305.7  4828.4  305.75  4842.9  304.31  4849.2  304.41  4857.4  303.79
  4886.4  303.58  4892.7  303.95  4907.2  303.49  4942.5  303.93  4963.3  303.43
    4986  301.86  4997.2  299.54    5000  299.04  5003.2  299.54  5021.3  304.17
  5027.7  305.28  5035.8  306.29  5060.3  307.19  5085.7  307.47    5092  308.04
  5220.6  306.13  5241.4   307.9  5249.6  307.83  5270.4  306.17    5290  306.45
#Mann= 4 ,-1 , 0
    4642     .16       0  4997.2     .07       0  5003.2     .16       0
  5060.3     .05       0
Bank Sta=4997.2,5003.2
XS Rating Curve= 0 ,0
Exp/Cntr=0.3,0.1

Type RM Length L Ch R = 1 ,482     ,95,95,95
BEGIN DESCRIPTION:
UNT0504 IN WICK 4.0
END DESCRIPTION:
XS GIS Cut Line= 2
      3567479.88      10239262.5      3568037.12     10238952.64
#Sta/Elev= 30
  4782.2  307.27  4852.6  304.54  4922.7  300.36    4933  301.02  4938.8  299.52
  4954.8  299.95  4970.4  298.74  4982.2  299.55  4995.2  298.31    4998  297.81
  5001.2  298.31    5036  301.36  5041.7   303.7  5057.7  303.45  5063.4  305.62
  5079.4  304.36  5083.6  305.66  5101.2  304.36  5106.9  305.91  5122.9  303.91
  5128.6  305.25  5138.9  304.11  5144.6  305.43  5160.6  303.23  5166.3  304.72
  5182.4  303.03  5231.5  304.54  5328.7  304.04  5350.5  305.37  5419.8  303.56
#Mann= 6 ,-1 , 0
  4782.2      .1       0  4852.6     .05       0  4970.4     .16       0
  4995.2     .07       0  5001.2     .16       0  5083.6     .05       0
Bank Sta=4995.2,5001.2
XS Rating Curve= 0 ,0
Exp/Cntr=0.3,0.1

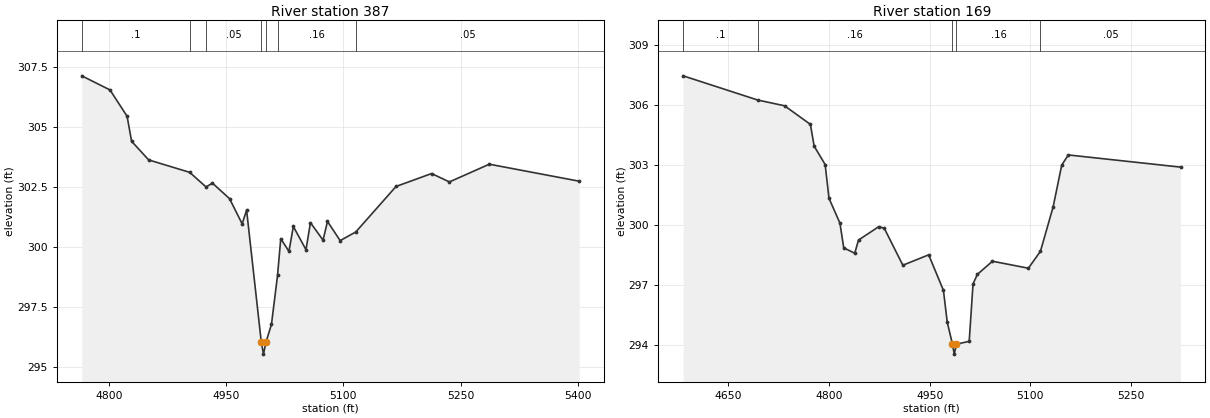
Type RM Length L Ch R = 1 ,387     ,218,218,218
BEGIN DESCRIPTION:
UNT0504 IN WICK 3.0
END DESCRIPTION:
XS GIS Cut Line= 2
      3567518.91     10239345.85      3568077.99     10239041.61
#Sta/Elev= 30
  4765.2  307.15  4801.3  306.56  4823.2  305.46  4828.9  304.42  4850.7  303.64
  4903.3  303.12  4924.2  302.51  4932.4  302.67  4954.3  302.02  4970.4  300.97
  4976.1  301.54  4994.9  296.03  4997.7  295.53  5000.9  296.03  5007.9  296.77
  5015.7  298.82  5019.8  300.35  5030.3  299.82  5035.9  300.86  5052.1  299.89
  5057.8  301.02  5073.9  300.29  5079.6  301.07  5095.8  300.27  5115.8  300.63
  5167.3  302.53  5212.8  303.07  5235.6  302.72  5286.7  303.46  5401.7  302.75
#Mann= 7 ,-1 , 0
  4765.2      .1       0  4903.3     .16       0  4924.2     .05       0
  4994.9     .04       0  5000.9     .05       0  5015.7     .16       0
  5115.8     .05       0
Bank Sta=4994.9,5000.9
XS Rating Curve= 0 ,0
Exp/Cntr=0.3,0.1

Type RM Length L Ch R = 1 ,169     ,0,0,0
BEGIN DESCRIPTION:
UNT0504 IN WICK 2.0
END DESCRIPTION:
XS GIS Cut Line= 4
      3567553.46     10239414.21      3567648.91     10239422.89
       3568143.7     10239162.47      3568148.02     10239076.16
#Sta/Elev= 30
  4582.4  307.48  4693.4  306.27  4733.6  305.98  4772.1  305.05  4777.7  303.96
  4794.1  303.04  4799.8  301.35  4816.1  300.11  4821.8  298.87  4838.2   298.6
  4843.8  299.26    4874  299.93  4882.2  299.85  4909.9     298  4948.4  298.52
  4970.4  296.74    4976  295.16  4983.8  294.05  4986.5  293.55  4989.8  294.05
  5008.8  294.19  5014.5  297.06  5020.9  297.54  5043.5   298.2    5097  297.85
    5115   298.7  5133.9  300.92  5146.7  303.01  5156.5  303.52  5323.8  302.91
#Mann= 5 ,-1 , 0
  4582.4      .1       0  4693.4     .16       0  4983.8     .07       0
  4989.8     .16       0    5115     .05       0
Bank Sta=4983.8,4989.8
XS Rating Curve= 0 ,0
Exp/Cntr=0.3,0.1

Chan Stop Cuts=-1
Use User Specified Reach Order=0
Composite Channel Slope=5