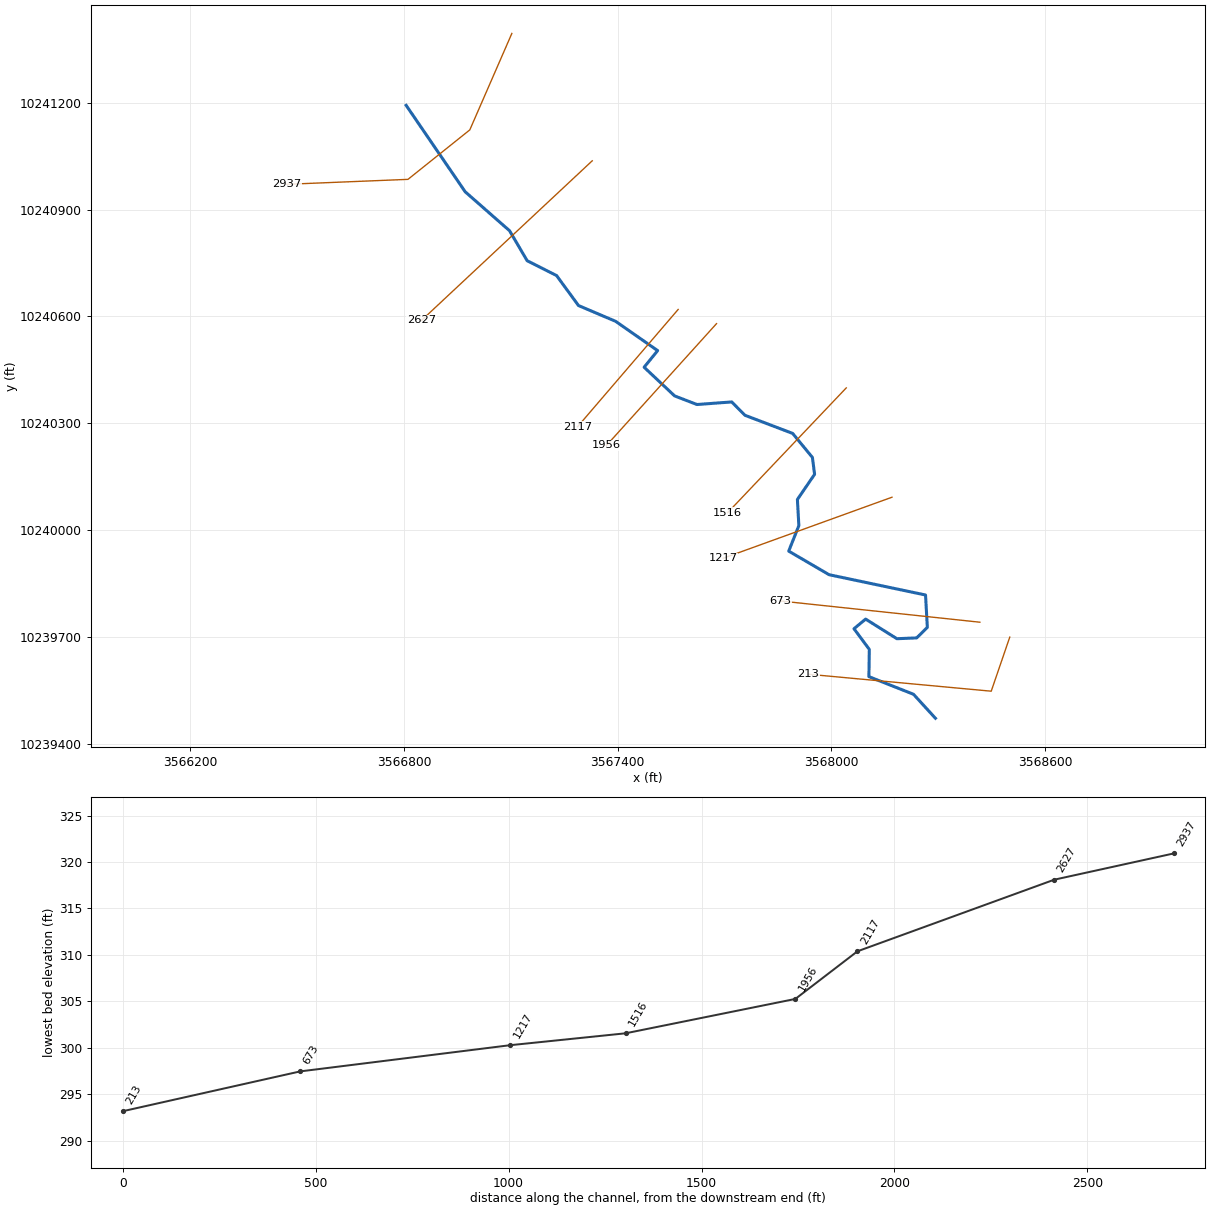
--- STEEPHOLLOWBRANCH.prj (project) ---

Proj Title=STEEP HOLLOW BRANCH TRIB 12
Current Plan=p01
Default Exp/Contr=0.3,0.1
English Units
Geom File=g01
Flow File=f01
Plan File=p01
Y Axis Title=Elevation
X Axis Title(PF)=Main Channel Distance
X Axis Title(XS)=Station
BEGIN DESCRIPTION:
UNT05241 IN WICK
END DESCRIPTION:
DSS Export Rating Curves= 0
DSS Export Rating Curve Sorted= 0
DSS Export Volume Flow Curves= 0
DXF OffsetX= 0
DXF OffsetY= 0
DXF ScaleX= 1
DXF ScaleY= 10

--- STEEPHOLLOWBRANCH.p01 (plan) ---

Plan Title=Multiple Run
Short Identifier=Multiple
Geom File=g01
Flow File=f01
Subcritical Flow
K Sum by GR= 0
Std Step Tol= 0.01
Critical Tol= 0.01
Num of Std Step Trials= 20
Max Error Tol= 0.3
Flow Tol Ratio= 0.001
Split Flow NTrial= 30
Split Flow Tol= 0.02
Split Flow Ratio= 0.02
Log Output Level= 0
Friction Slope Method= 1
Unsteady Friction Slope Method= 2
Unsteady Bridges Friction Slope Method= 1
Parabolic Critical Depth
Global Vel Dist=  1 , 1 , 1
Global Log Level= 0
CheckData=True
Encroach Param= -1, 0, 0, 0
BEGIN DESCRIPTION:
Multiple Run
END DESCRIPTION:

--- STEEPHOLLOWBRANCH.f01 (steady flow) ---

Flow Title=Multiple
Program Version=4.10
Number of Profiles= 7
Profile Names=10-year,25-year,50-year,1pct_min,100-year,1pct_plu,500-year
River Rch & RM=UNT05241 IN WICK,Reach-1         ,2937
     143     176     200     167     226     306     290
River Rch & RM=TEEPHOLLOWBRTR12,Reach-1         ,2937
     143     176     200     167     226     306     290
Boundary for River Rch & Prof#=TEEPHOLLOWBRTR12,Reach-1         , 1
Up Type= 0
Dn Type= 3
Dn Slope=0.005
Boundary for River Rch & Prof#=TEEPHOLLOWBRTR12,Reach-1         , 2
Up Type= 0
Dn Type= 3
Dn Slope=0.005
Boundary for River Rch & Prof#=TEEPHOLLOWBRTR12,Reach-1         , 3
Up Type= 0
Dn Type= 3
Dn Slope=0.005
Boundary for River Rch & Prof#=TEEPHOLLOWBRTR12,Reach-1         , 4
Up Type= 0
Dn Type= 3
Dn Slope=0.005
Boundary for River Rch & Prof#=TEEPHOLLOWBRTR12,Reach-1         , 5
Up Type= 0
Dn Type= 3
Dn Slope=0.005
Boundary for River Rch & Prof#=TEEPHOLLOWBRTR12,Reach-1         , 6
Up Type= 0
Dn Type= 3
Dn Slope=0.005
Boundary for River Rch & Prof#=TEEPHOLLOWBRTR12,Reach-1         , 7
Up Type= 0
Dn Type= 3
Dn Slope=0.005
DSS Import GetInterval= 0
DSS Import GetPeak= 0
DSS Import FillOption= 0

--- STEEPHOLLOWBRANCH.g01 (geometry) ---

Geom Title=Existing Conditions
Program Version=4.10

River Reach=TEEPHOLLOWBRTR12,Reach-1
Reach XY= 30
      3566805.91      10241192.7      3566971.71     10240949.93
       3567096.3      10240840.6       3567145.6     10240756.49
      3567228.25     10240714.73      3567289.88     10240630.53
      3567394.04     10240586.26      3567512.08     10240503.97
       3567474.1     10240457.31      3567559.75     10240376.77
      3567622.41     10240352.65      3567720.04     10240359.86
      3567757.36     10240322.38      3567891.23     10240271.46
      3567946.69     10240203.99       3567952.8     10240156.62
      3567904.54     10240086.03      3567908.61     10240012.53
      3567880.12     10239940.96      3567993.39     10239874.78
      3568264.31     10239817.75       3568269.4     10239726.86
      3568239.44     10239697.29      3568183.87     10239695.04
      3568096.16      10239750.1      3568063.41     10239723.11
      3568106.47     10239664.98      3568105.31     10239588.47
      3568230.49     10239539.03      3568292.11     10239471.64

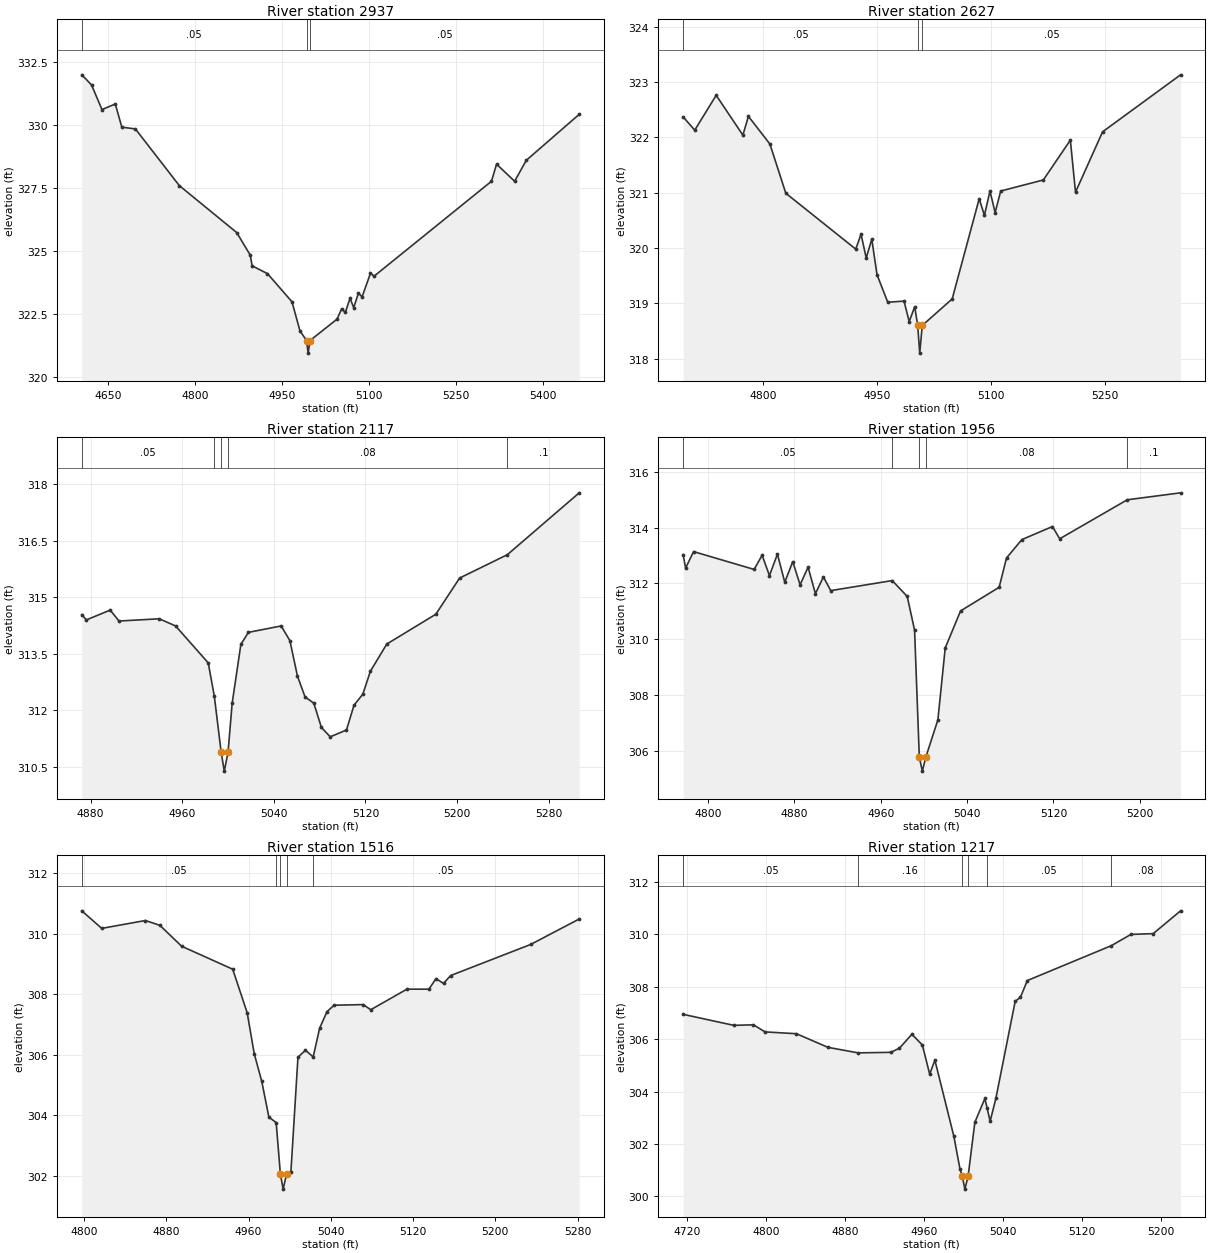
Type RM Length L Ch R = 1 ,2937    ,310,310,310
BEGIN DESCRIPTION:
UNT05241 IN WICK 4.0
END DESCRIPTION:
XS GIS Cut Line= 4
       3567102.7     10241394.59      3566984.64     10241123.76
      3566811.03     10240984.87      3566470.79     10240970.99
#Sta/Elev= 30
  4604.3  331.99  4621.1  331.59  4639.1  330.61  4662.1  330.83  4673.4  329.91
  4696.8  329.84  4772.5  327.59  4871.7  325.72  4895.1  324.82  4898.2   324.4
  4924.7  324.09    4967  322.97  4980.7  321.82  4992.1  321.43  4994.9  320.93
  4998.1  321.43  5044.7  322.28  5052.7  322.69  5059.1  322.55  5067.1  323.11
  5073.5  322.74  5081.6  323.31    5088  323.17  5102.4   324.1  5108.8  323.99
  5311.2  327.76    5320  328.44  5351.2  327.76  5371.2  328.59  5462.6  330.42
#Mann= 3 ,-1 , 0
  4604.3     .05       0  4992.1     .03       0  4998.1     .05       0
Bank Sta=4992.1,4998.1
XS Rating Curve= 0 ,0
Exp/Cntr=0.3,0.1

Type RM Length L Ch R = 1 ,2627    ,510,510,510
BEGIN DESCRIPTION:
UNT05241 IN WICK 3.0
END DESCRIPTION:
XS GIS Cut Line= 2
      3567328.38     10241036.95      3566849.23     10240589.04
#Sta/Elev= 30
  4694.1  322.37  4709.4  322.13  4737.7  322.76  4772.9  322.04  4780.2  322.38
  4808.5  321.88  4829.5  320.99  4921.7  319.98  4928.7  320.25  4935.5  319.82
  4942.9  320.16  4949.7  319.52  4963.9  319.02  4985.4  319.04  4992.2  318.67
  4999.5  318.94  5003.4   318.6  5006.1   318.1  5009.4   318.6  5048.9  319.08
  5084.5  320.89  5091.4  320.59  5098.7  321.03  5105.5  320.64  5112.9  321.03
  5169.1  321.23  5204.7  321.95  5211.5  321.01  5247.2   322.1    5350  323.13
#Mann= 3 ,-1 , 0
  4694.1     .05       0  5003.4     .03       0  5009.4     .05       0
Bank Sta=5003.4,5009.4
XS Rating Curve= 0 ,0
Exp/Cntr=0.3,0.1

Type RM Length L Ch R = 1 ,2117    ,161,161,161
BEGIN DESCRIPTION:
Mapping XS 44c8414e
END DESCRIPTION:
XS GIS Cut Line= 2
      3567569.71      10240619.6      3567286.93     10240289.97
#Sta/Elev= 30
  4872.3  314.54  4876.3   314.4  4897.1  314.66  4904.8  314.37  4939.9  314.43
  4954.2  314.24  4982.7  313.26    4988  312.38    4994  310.89  4996.7  310.39
    5000  310.89  5003.6  312.19  5011.2  313.75  5017.8  314.07  5046.4  314.24
    5054  313.85  5060.6  312.91  5067.2  312.36  5074.9  312.19  5081.5  311.55
  5089.2   311.3  5103.4  311.48    5110  312.14  5117.7  312.43  5124.3  313.04
  5138.6  313.76  5181.4  314.55  5202.2  315.51  5243.9  316.13  5306.6  317.77
#Mann= 5 ,-1 , 0
  4872.3     .05       0    4988     .08       0    4994     .07       0
    5000     .08       0  5243.9      .1       0
Bank Sta=4994,5000
XS Rating Curve= 0 ,0
Exp/Cntr=0.3,0.1

Type RM Length L Ch R = 1 ,1956    ,440,440,440
BEGIN DESCRIPTION:
Mapping XS cff3f08c
END DESCRIPTION:
XS GIS Cut Line= 2
      3567677.37     10240579.69      3567368.31     10240237.63
#Sta/Elev= 30
  4776.8  313.03  4779.1  312.55  4786.5  313.14  4842.6   312.5    4850  313.01
  4856.8  312.28  4864.2  313.05    4871  312.04  4878.4  312.78  4885.2  311.95
  4892.6  312.58  4899.4  311.63  4906.8  312.23  4913.6  311.74  4970.6   312.1
  4984.5  311.53  4991.3  310.32  4995.7  305.76  4998.5  305.26  5001.7  305.76
  5012.9   307.1  5019.7  309.68  5033.9  311.01  5069.7  311.86  5076.5  312.91
  5090.7  313.57  5119.1  314.04  5125.8   313.6  5188.4     315  5237.8  315.25
#Mann= 5 ,-1 , 0
  4776.8     .05       0  4970.6     .08       0  4995.7     .07       0
  5001.7     .08       0  5188.4      .1       0
Bank Sta=4995.7,5001.7
XS Rating Curve= 0 ,0
Exp/Cntr=0.3,0.1

Type RM Length L Ch R = 1 ,1516    ,299,299,299
BEGIN DESCRIPTION:
UNT05241 IN WICK 2.0
END DESCRIPTION:
XS GIS Cut Line= 2
      3568041.72     10240399.36      3567708.35     10240048.62
#Sta/Elev= 30
  4797.7  310.76  4817.1  310.18  4859.6  310.44  4873.7  310.28  4894.8  309.59
  4944.5  308.83  4958.6  307.39  4965.5  306.03  4972.8  305.12  4979.7  303.94
  4986.8  303.76  4990.9  302.06  4993.6  301.56  4996.9  302.06  5001.1  302.11
    5008  305.92  5015.3  306.15  5022.8  305.93  5029.1  306.88  5036.3  307.43
  5043.2  307.64  5071.5  307.66  5078.8  307.49    5114  308.17  5135.4  308.17
  5142.3  308.52  5149.6  308.36  5156.5  308.62  5234.5  309.65  5281.6  310.49
#Mann= 5 ,-1 , 0
  4797.7     .05       0  4986.8     .16       0  4990.9     .07       0
  4996.9     .16       0  5022.8     .05       0
Bank Sta=4990.9,4996.9
XS Rating Curve= 0 ,0
Exp/Cntr=0.3,0.1

Type RM Length L Ch R = 1 ,1217    ,544,544,544
BEGIN DESCRIPTION:
Mapping XS 91aacab5
END DESCRIPTION:
XS GIS Cut Line= 2
      3568170.17     10240092.35      3567696.03     10239920.88
#Sta/Elev= 30
  4715.8  306.95  4767.1  306.53  4787.1  306.55  4798.8  306.28  4830.7  306.21
  4862.6  305.69  4893.2  305.48  4926.4   305.5  4935.1  305.66  4947.7  306.19
  4958.3  305.78  4965.7  304.67    4971   305.2  4990.2   302.3  4996.4  301.05
  4998.7  300.78  5001.4  300.28  5004.7  300.78  5011.5  302.83  5021.7  303.74
    5024  303.36    5027  302.87  5032.8  303.74  5052.4  307.45  5057.7   307.6
  5064.7  308.24  5149.8  309.57  5169.7     310  5192.3  310.03    5220   310.9
#Mann= 6 ,-1 , 0
  4715.8     .05       0  4893.2     .16       0  4998.7     .07       0
  5004.7     .16       0    5024     .05       0  5149.8     .08       0
Bank Sta=4998.7,5004.7
XS Rating Curve= 0 ,0
Exp/Cntr=0.3,0.1

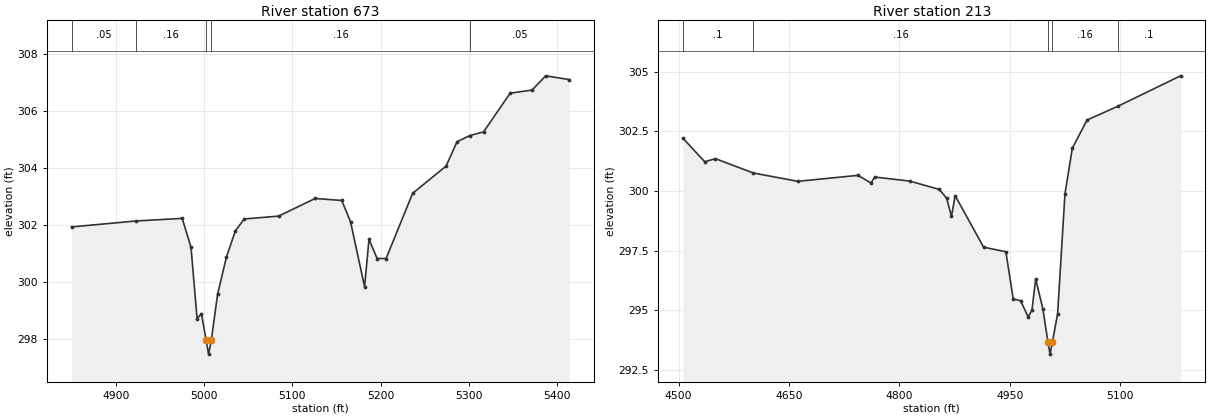
Type RM Length L Ch R = 1 ,673     ,460,460,460
BEGIN DESCRIPTION:
Mapping XS 9a448dd0
END DESCRIPTION:
XS GIS Cut Line= 2
      3568416.85     10239741.36      3567855.73     10239801.11
#Sta/Elev= 30
  4849.5  301.93  4922.8  302.14    4975  302.23    4985  301.22  4991.9  298.71
  4996.9  298.88  5002.1  297.96  5004.9  297.46  5008.1  297.96  5015.2  299.57
  5025.2  300.87  5035.3  301.79  5045.4  302.21  5084.4  302.31  5125.8  302.93
    5156  302.86    5166  302.11  5181.9  299.83  5186.9  301.49  5196.2  300.82
  5206.3  300.82  5236.4  303.11  5274.4  304.07  5286.7  304.92  5301.1  305.14
  5316.9  305.27    5347  306.63  5371.9  306.74  5387.3  307.24  5413.8  307.11
#Mann= 5 ,-1 , 0
  4849.5     .05       0  4922.8     .16       0  5002.1     .07       0
  5008.1     .16       0  5301.1     .05       0
Bank Sta=5002.1,5008.1
XS Rating Curve= 0 ,0
Exp/Cntr=0.3,0.1

Type RM Length L Ch R = 1 ,213     ,0,0,0
BEGIN DESCRIPTION:
UNT05241 IN WICK 1.0
END DESCRIPTION:
XS GIS Cut Line= 3
      3568500.86     10239699.56      3568448.78     10239547.65
      3567935.78     10239595.27
#Sta/Elev= 30
    4506  302.21  4535.5  301.23  4549.9  301.36  4601.3  300.76  4661.8  300.41
  4743.6  300.66  4761.3  300.34  4766.3  300.59  4813.9  300.42  4854.1  300.07
  4864.1   299.7  4870.6  298.94  4875.6  299.81  4914.3  297.65  4944.5  297.46
  4954.5  295.48  4964.5  295.41  4974.6  294.74  4979.9     295    4985  296.32
  4994.7  295.08  5001.7  293.67  5004.5  293.17  5007.7  293.67  5014.8  294.86
  5024.8  299.89  5034.8   301.8  5054.9  302.98  5096.3  303.55  5181.8  304.83
#Mann= 5 ,-1 , 0
    4506      .1       0  4601.3     .16       0  5001.7     .07       0
  5007.7     .16       0  5096.3      .1       0
Bank Sta=5001.7,5007.7
XS Rating Curve= 0 ,0
Exp/Cntr=0.3,0.1

Chan Stop Cuts=-1
Use User Specified Reach Order=0
Composite Channel Slope=5