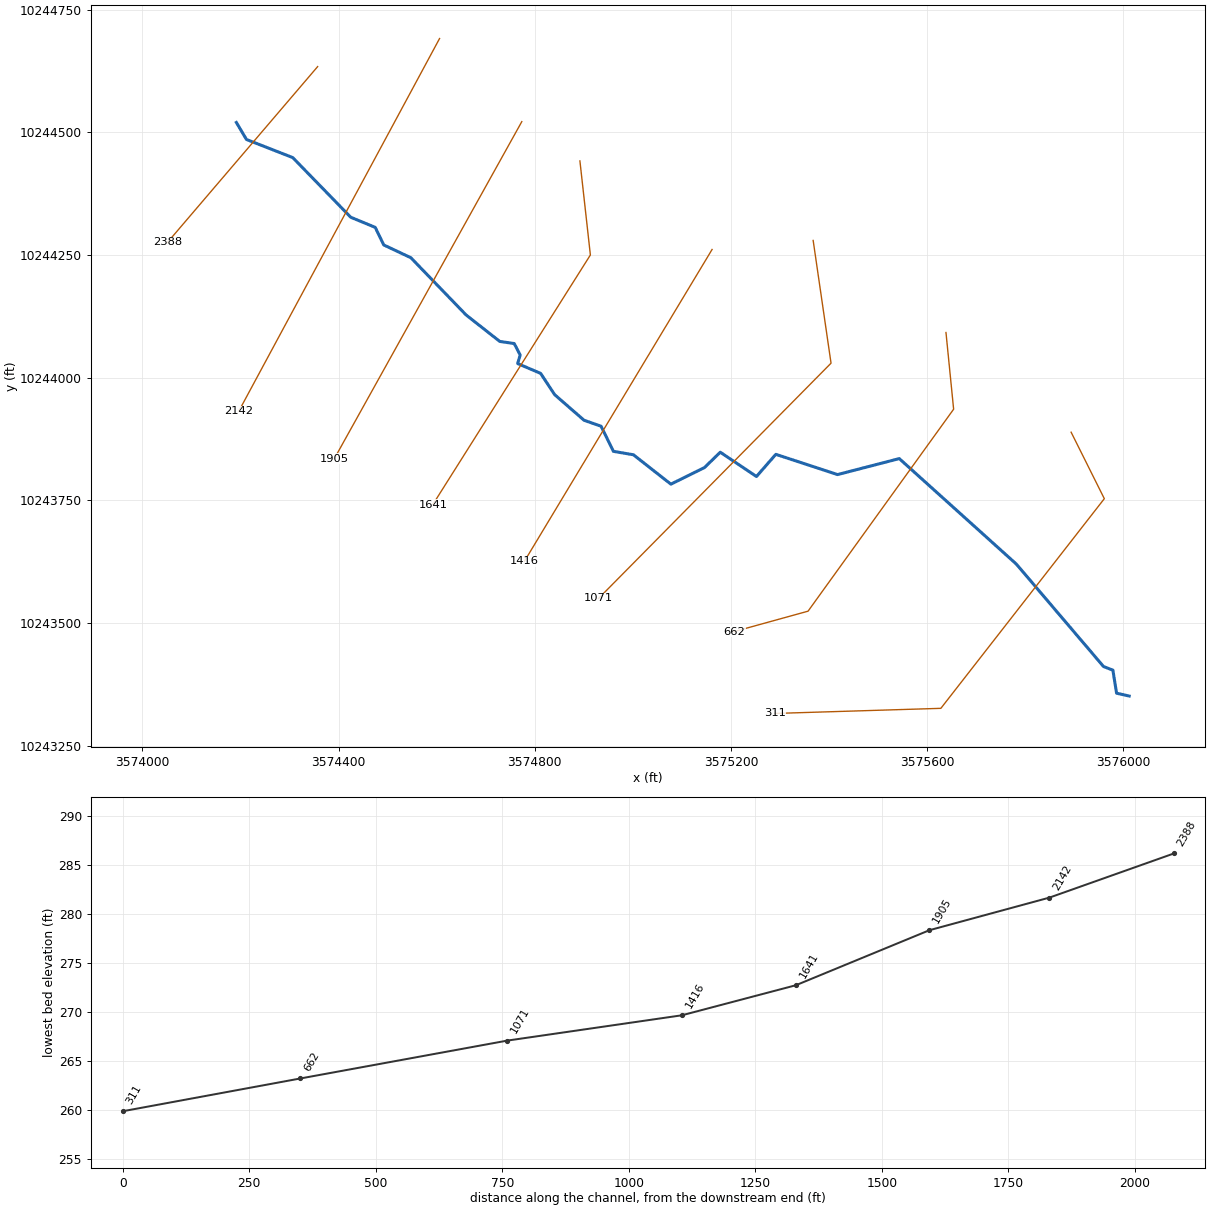
--- STEEPHOLLOWBRANCH.prj (project) ---

Proj Title=STEEP HOLLOW BRANCH TRIB 2
Current Plan=p01
Default Exp/Contr=0.3,0.1
English Units
Geom File=g01
Flow File=f01
Plan File=p01
Y Axis Title=Elevation
X Axis Title(PF)=Main Channel Distance
X Axis Title(XS)=Station
BEGIN DESCRIPTION:
UNT05249 IN WICK
END DESCRIPTION:
DSS Export Rating Curves= 0
DSS Export Rating Curve Sorted= 0
DSS Export Volume Flow Curves= 0
DXF OffsetX= 0
DXF OffsetY= 0
DXF ScaleX= 1
DXF ScaleY= 10

--- STEEPHOLLOWBRANCH.p01 (plan) ---

Plan Title=Multiple Run
Short Identifier=Multiple
Geom File=g01
Flow File=f01
Subcritical Flow
K Sum by GR= 0
Std Step Tol= 0.01
Critical Tol= 0.01
Num of Std Step Trials= 20
Max Error Tol= 0.3
Flow Tol Ratio= 0.001
Split Flow NTrial= 30
Split Flow Tol= 0.02
Split Flow Ratio= 0.02
Log Output Level= 0
Friction Slope Method= 1
Unsteady Friction Slope Method= 2
Unsteady Bridges Friction Slope Method= 1
Parabolic Critical Depth
Global Vel Dist=  1 , 1 , 1
Global Log Level= 0
CheckData=True
Encroach Param= -1, 0, 0, 0
BEGIN DESCRIPTION:
Multiple Run
END DESCRIPTION:

--- STEEPHOLLOWBRANCH.f01 (steady flow) ---

Flow Title=Multiple
Program Version=4.10
Number of Profiles= 7
Profile Names=10-year,25-year,50-year,1pct_min,100-year,1pct_plu,500-year
River Rch & RM=UNT05249 IN WICK,Reach-1         ,2388
     121     147     166     139     188     254     239
River Rch & RM=STEEPHOLLOWBRTR2,Reach-1         ,2388
     121     147     166     139     188     254     239
Boundary for River Rch & Prof#=STEEPHOLLOWBRTR2,Reach-1         , 1
Up Type= 0
Dn Type= 3
Dn Slope=0.005
Boundary for River Rch & Prof#=STEEPHOLLOWBRTR2,Reach-1         , 2
Up Type= 0
Dn Type= 3
Dn Slope=0.005
Boundary for River Rch & Prof#=STEEPHOLLOWBRTR2,Reach-1         , 3
Up Type= 0
Dn Type= 3
Dn Slope=0.005
Boundary for River Rch & Prof#=STEEPHOLLOWBRTR2,Reach-1         , 4
Up Type= 0
Dn Type= 3
Dn Slope=0.005
Boundary for River Rch & Prof#=STEEPHOLLOWBRTR2,Reach-1         , 5
Up Type= 0
Dn Type= 3
Dn Slope=0.005
Boundary for River Rch & Prof#=STEEPHOLLOWBRTR2,Reach-1         , 6
Up Type= 0
Dn Type= 3
Dn Slope=0.005
Boundary for River Rch & Prof#=STEEPHOLLOWBRTR2,Reach-1         , 7
Up Type= 0
Dn Type= 3
Dn Slope=0.005
DSS Import GetInterval= 0
DSS Import GetPeak= 0
DSS Import FillOption= 0

--- STEEPHOLLOWBRANCH.g01 (geometry) ---

Geom Title=Existing Conditions
Program Version=4.10

River Reach=STEEPHOLLOWBRTR2,Reach-1
Reach XY= 30
       3574191.5     10244520.11      3574212.12     10244485.39
      3574306.52     10244448.49      3574424.79     10244326.97
       3574474.7     10244306.35      3574492.07     10244270.54
       3574547.4      10244244.5      3574660.07     10244127.85
      3574728.65     10244074.03      3574758.16     10244069.69
      3574770.32     10244046.26      3574765.11      10244028.9
      3574811.98     10244008.93      3574840.63     10243965.53
      3574900.52     10243913.44      3574935.25     10243901.29
      3574960.42     10243850.08      3575001.22     10243843.13
      3575077.61     10243783.24      3575146.18     10243817.09
       3575178.3     10243848.34      3575252.09     10243798.86
      3575291.58       10243844.      3575417.45     10243802.77
      3575543.32     10243835.32      3575782.03     10243620.47
      3575959.83     10243411.75      3575978.94     10243404.37
      3575986.45     10243357.41      3576012.11     10243351.64

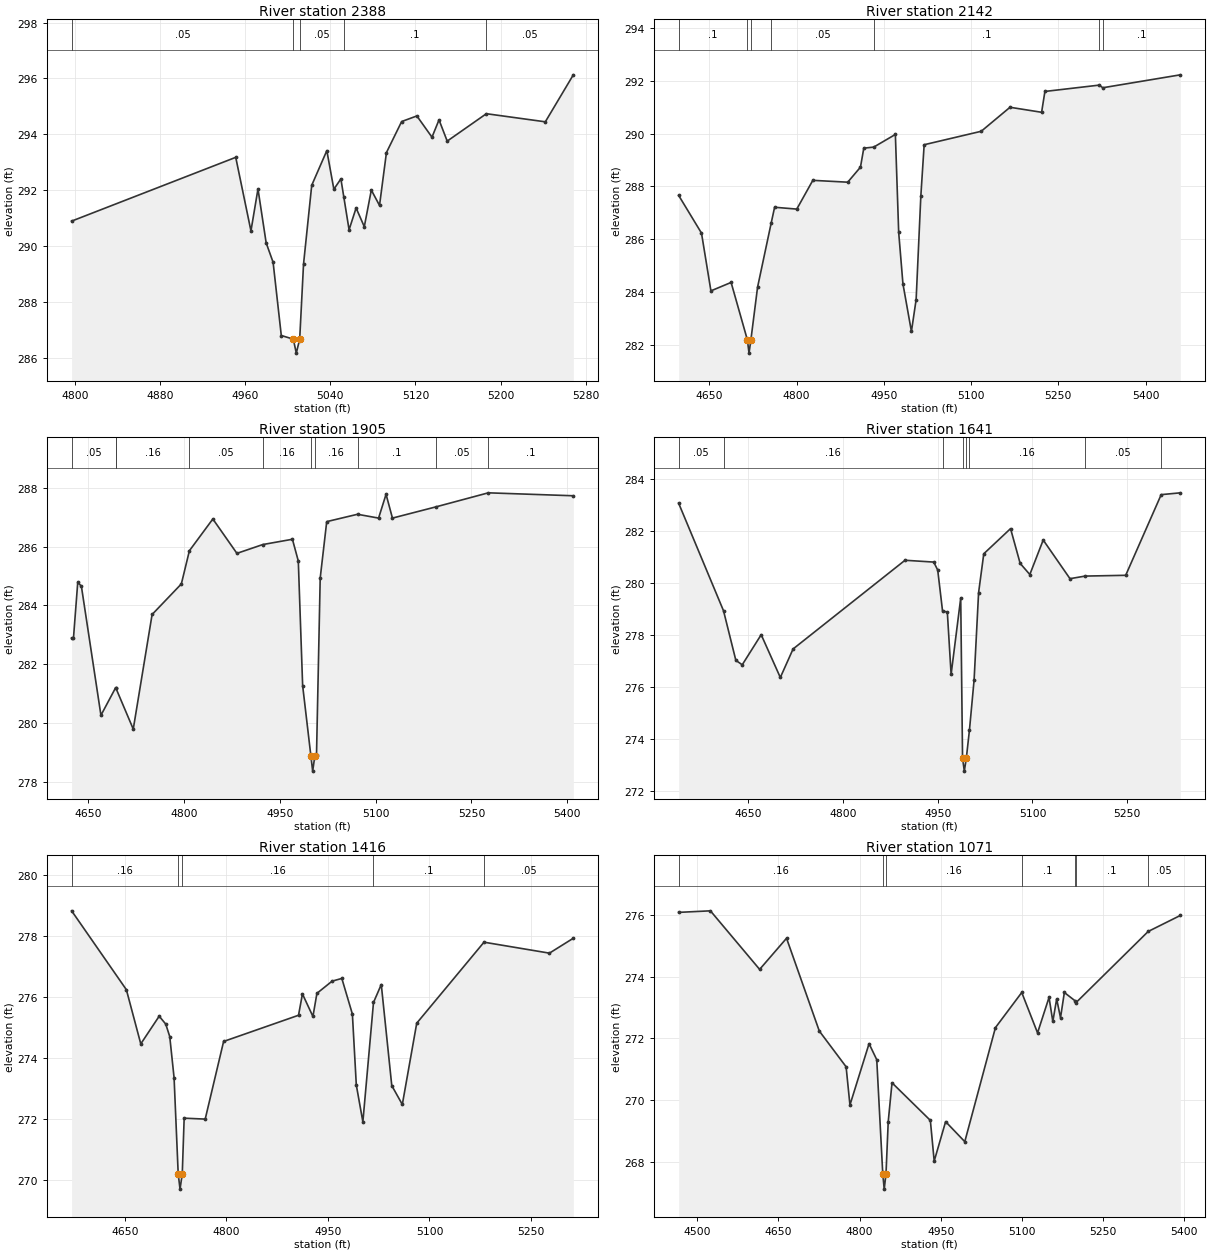
Type RM Length L Ch R = 1 ,2388    ,246,246,246
BEGIN DESCRIPTION:
UNT05249 IN WICK 5.0
END DESCRIPTION:
XS GIS Cut Line= 2
      3574357.31     10244633.88      3574050.95      10244275.6
#Sta/Elev= 30
  4796.9   290.9  4951.1  293.18  4965.4  290.55    4972  292.05  4979.7  290.12
  4986.2  289.43  4993.9  286.81  5005.2  286.68    5008  286.18  5011.2  286.68
  5014.8  289.36  5022.5  292.18  5036.7  293.42  5043.3  292.04  5049.9  292.41
  5052.7  291.75  5057.6  290.59  5064.2  291.37  5071.9   290.7  5078.5  292.01
  5086.2  291.46  5092.7  293.35    5107  294.46  5121.3  294.66  5135.5   293.9
  5142.1  294.52  5149.8  293.76  5186.6  294.74    5242  294.45  5268.3  296.13
#Mann= 5 ,-1 , 0
  4796.9     .05       0  5005.2     .03       0  5011.2     .05       0
  5052.7      .1       0  5186.6     .05       0
Bank Sta=5005.2,5011.2
XS Rating Curve= 0 ,0
Exp/Cntr=0.3,0.1

Type RM Length L Ch R = 1 ,2142    ,237,237,237
BEGIN DESCRIPTION:
UNT05249 IN WICK 4.0
END DESCRIPTION:
XS GIS Cut Line= 2
      3574605.89     10244691.04      3574196.47     10243931.91
#Sta/Elev= 30
  4597.2  287.66  4636.5  286.23  4652.7  284.04  4687.4  284.36  4715.4  282.18
  4718.2  281.68  4721.4  282.18  4732.9  284.18  4756.2   286.6  4762.2  287.21
  4800.3  287.14  4827.9  288.23  4887.9  288.16  4909.8  288.73  4915.5  289.45
  4932.6  289.49  4969.8  289.97  4975.5  286.26  4982.8  284.31  4997.4   282.5
  5005.5  283.71  5013.6  287.64  5019.3  289.58  5117.4  290.09  5166.9     291
  5221.2  290.81  5226.9   291.6  5320.3  291.84  5326.4  291.74  5459.7  292.23
#Mann= 7 ,-1 , 0
  4597.2      .1       0  4715.4     .07       0  4721.4      .1       0
  4756.2     .05       0  4932.6      .1       0  5320.3     .05       0
  5326.4      .1       0
Bank Sta=4715.4,4721.4
XS Rating Curve= 0 ,0
Exp/Cntr=0.3,0.1

Type RM Length L Ch R = 1 ,1905    ,264,264,264
BEGIN DESCRIPTION:
Mapping XS 67a27ff7
END DESCRIPTION:
XS GIS Cut Line= 2
      3574773.58     10244521.72      3574391.45     10243835.44
#Sta/Elev= 30
  4624.1  282.89    4627  282.89  4633.7  284.79  4639.4  284.65    4670  280.26
  4692.8  281.19  4693.5  281.18  4720.6  279.79  4750.1  283.69  4795.9  284.73
  4808.5  285.86  4845.2  286.94  4882.9  285.77  4923.4  286.07  4969.8  286.25
    4979  285.51  4985.8  281.27  4998.8  278.86  5001.5  278.36  5004.8  278.86
  5007.5   278.9  5013.3  284.93  5023.5  286.85  5071.7   287.1  5104.7  286.97
  5116.4  287.78  5126.4  286.97  5194.1  287.35  5276.5  287.83  5409.6  287.73
#Mann= 10 ,-1 , 0
  4624.1     .05       0  4692.8      .1       0  4693.5     .16       0
  4808.5     .05       0  4923.4     .16       0  4998.8     .07       0
  5004.8     .16       0  5071.7      .1       0  5194.1     .05       0
  5276.5      .1       0
Bank Sta=4998.8,5004.8
XS Rating Curve= 0 ,0
Exp/Cntr=0.3,0.1

Type RM Length L Ch R = 1 ,1641    ,225,225,225
BEGIN DESCRIPTION:
UNT05249 IN WICK 3.0
END DESCRIPTION:
XS GIS Cut Line= 3
       3574892.1     10244441.69      3574913.43     10244250.08
      3574592.08     10243741.61
#Sta/Elev= 30
  4539.8  283.08  4610.9  278.93  4630.4  277.02  4640.5  276.85  4670.5  278.01
  4700.8  276.36    4721  277.46  4898.2  280.88  4943.7  280.81    4950   280.5
  4957.6  278.93  4965.2  278.88  4971.2  276.48  4986.4  279.42  4989.3  273.25
  4992.1  272.75  4995.3  273.25  5000.3  274.35  5007.6  276.27  5014.7  279.63
  5022.9  281.13  5065.3   282.1  5080.5  280.76  5095.8  280.33    5117  281.66
  5159.4  280.17  5183.4  280.27  5247.6   280.3  5303.8  283.41  5334.1  283.48
#Mann= 8 ,-1 , 0
  4539.8     .05       0  4610.9     .16       0  4957.6     .05       0
  4989.3     .03       0  4995.3     .05       0  5000.3     .16       0
  5183.4     .05       0  5303.8      .1       0
Bank Sta=4989.3,4995.3
XS Rating Curve= 0 ,0
Exp/Cntr=0.3,0.1

Type RM Length L Ch R = 1 ,1416    ,345,345,345
BEGIN DESCRIPTION:
Mapping XS abeb6b77
END DESCRIPTION:
XS GIS Cut Line= 2
      3575161.61     10244261.32      3574779.02     10243626.26
#Sta/Elev= 30
  4571.2  278.83  4652.1  276.24  4673.4  274.46  4700.6  275.37  4710.3  275.11
  4716.2   274.7  4722.6  273.35  4728.7  270.19  4731.4  269.69  4734.7  270.19
  4737.5  272.02  4768.6  271.99  4795.8  274.54  4906.5   275.4  4912.3   276.1
  4927.8  275.36  4933.7  276.12  4956.1  276.52  4970.5  276.61  4986.1  275.44
  4991.9  273.11  5001.6   271.9  5017.3  275.82  5028.8  276.41  5044.3  273.09
  5059.9  272.47  5081.2  275.14  5180.6   277.8  5277.3  277.44  5312.6  277.93
#Mann= 5 ,-1 , 0
  4571.2     .16       0  4728.7     .07       0  4734.7     .16       0
  5017.3      .1       0  5180.6     .05       0
Bank Sta=4728.7,4734.7
XS Rating Curve= 0 ,0
Exp/Cntr=0.3,0.1

Type RM Length L Ch R = 1 ,1071    ,409,409,409
BEGIN DESCRIPTION:
UNT05249 IN WICK 2.0
END DESCRIPTION:
XS GIS Cut Line= 3
      3575367.73      10244279.7      3575404.18     10244029.72
      3574930.22     10243550.55
#Sta/Elev= 30
  4465.9  276.09  4524.6  276.14  4615.5  274.24  4665.2  275.25  4725.7  272.24
  4775.2  271.08  4782.3  269.84  4817.6  271.83  4831.8  271.31  4842.9  267.61
  4845.6  267.11  4848.9  267.61    4853   269.3    4860  270.56  4930.8  269.34
  4937.9  268.02    4959   269.3  4994.4  268.65    5051  272.35  5099.6  273.49
  5128.8  272.18    5150  273.33    5157  272.55  5164.1  273.28  5171.2  272.67
  5178.3  273.49  5197.4  273.23  5199.2  273.15  5333.1  275.47  5392.5  275.99
#Mann= 7 ,-1 , 0
  4465.9     .16       0  4842.9     .07       0  4848.9     .16       0
  5099.6      .1       0  5197.4     .16       0  5199.2      .1       0
  5333.1     .05       0
Bank Sta=4842.9,4848.9
XS Rating Curve= 0 ,0
Exp/Cntr=0.3,0.1

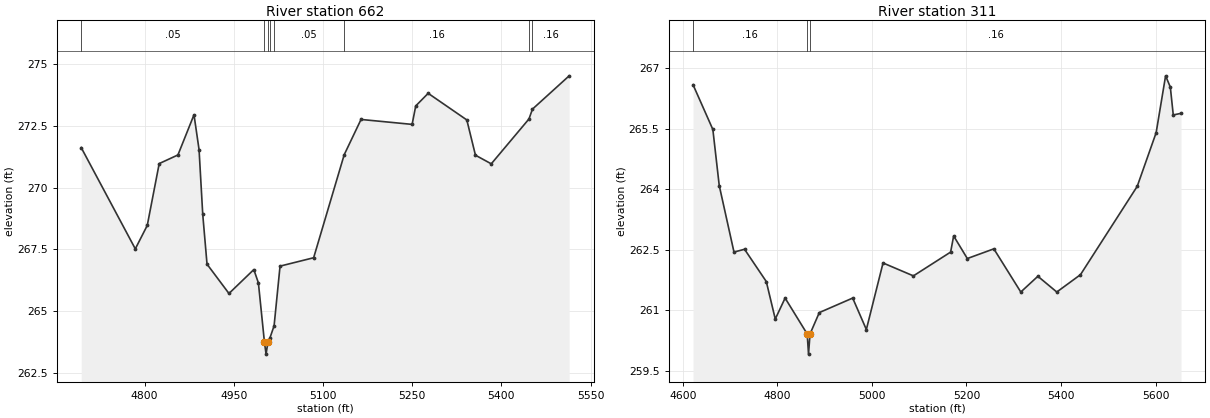
Type RM Length L Ch R = 1 ,662     ,351,351,351
BEGIN DESCRIPTION:
Mapping XS 3bda9e6e
END DESCRIPTION:
XS GIS Cut Line= 4
      3575638.56     10244092.17      3575654.18     10243935.97
      3575357.31     10243524.51       3575206.7     10243482.96
#Sta/Elev= 30
  4693.4  271.63  4784.4  267.52  4804.5  268.47  4824.6  270.98  4856.1  271.33
  4883.1  272.96  4891.6  271.55  4897.8  268.92    4905   266.9  4941.9  265.71
  4983.7  266.68  4991.4  266.14  5001.5  263.75  5004.3  263.25  5007.5  263.75
    5011  263.92  5017.8   264.4  5027.8  266.82  5084.3  267.16  5135.7  271.34
    5164  272.77  5249.9  272.57    5256  273.32  5276.9  273.83  5341.9  272.75
  5356.4  271.32    5383  270.97  5446.4  272.79  5452.3  273.19    5514  274.54
#Mann= 8 ,-1 , 0
  4693.4     .05       0  5001.5     .04       0  5007.5     .05       0
    5011     .16       0  5017.8     .05       0  5135.7     .16       0
  5446.4      .1       0  5452.3     .16       0
Bank Sta=5001.5,5007.5
XS Rating Curve= 0 ,0
Exp/Cntr=0.3,0.1

Type RM Length L Ch R = 1 ,311     ,0,0,0
BEGIN DESCRIPTION:
UNT05249 IN WICK 1.0
END DESCRIPTION:
XS GIS Cut Line= 4
      3575893.77     10243889.09      3575961.47     10243753.67
      3575628.14     10243326.59      3575289.56     10243316.17
#Sta/Elev= 30
  4621.8  266.59  4663.7  265.48  4677.2  264.09  4708.4  262.44  4730.7  262.51
  4776.7  261.71  4795.7  260.78  4816.5   261.3  4863.2  260.41    4866  259.91
  4869.2  260.41  4888.8  260.94  4959.4   261.3  4988.3  260.52  5023.6  262.17
  5087.8  261.85  5166.5  262.44  5172.9  262.84  5201.8  262.28  5257.9  262.52
  5314.9  261.45    5351  261.84    5391  261.45  5441.1  261.88  5561.1  264.07
  5601.1   265.4  5621.1  266.81  5631.1  266.53  5637.3  265.84  5653.7  265.88
#Mann= 3 ,-1 , 0
  4621.8     .16       0  4863.2     .07       0  4869.2     .16       0
Bank Sta=4863.2,4869.2
XS Rating Curve= 0 ,0
Exp/Cntr=0.3,0.1

Chan Stop Cuts=-1
Use User Specified Reach Order=0
Composite Channel Slope=5