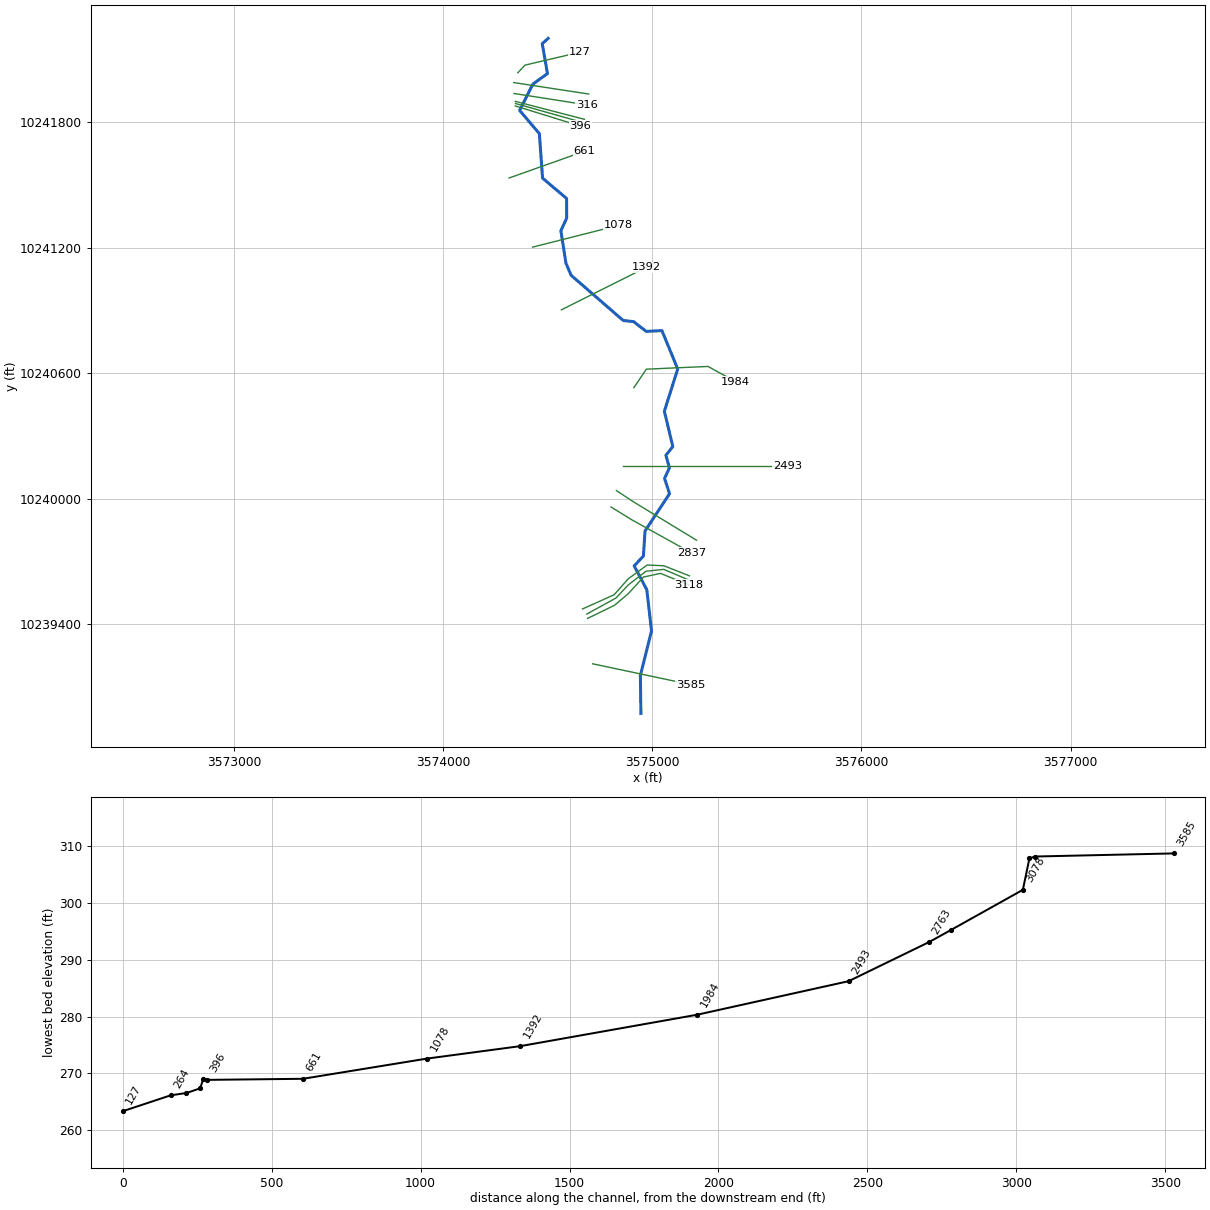
--- STEEPHOLLOWBRANCH.prj (project) ---

Proj Title=STEEP HOLLOW BRANCH TRIB 3
Current Plan=p01
Default Exp/Contr=0.3,0.1
English Units
Geom File=g01
Flow File=f01
Plan File=p01
Y Axis Title=Elevation
X Axis Title(PF)=Main Channel Distance
X Axis Title(XS)=Station
BEGIN DESCRIPTION:
UNT05248 IN WICK
END DESCRIPTION:
DSS Export Rating Curves= 0
DSS Export Rating Curve Sorted= 0
DSS Export Volume Flow Curves= 0
DXF Filename=UNT05248 IN WICK.
DXF OffsetX= 0
DXF OffsetY= 0
DXF ScaleX= 1
DXF ScaleY= 10

--- STEEPHOLLOWBRANCH.p01 (plan) ---

Plan Title=Multiple Run
Short Identifier=Multiple
Geom File=g01
Flow File=f01
Subcritical Flow
K Sum by GR= 0
Std Step Tol= 0.01
Critical Tol= 0.01
Num of Std Step Trials= 20
Max Error Tol= 0.3
Flow Tol Ratio= 0.001
Split Flow NTrial= 30
Split Flow Tol= 0.02
Split Flow Ratio= 0.02
Log Output Level= 0
Friction Slope Method= 1
Unsteady Friction Slope Method= 2
Unsteady Bridges Friction Slope Method= 1
Parabolic Critical Depth
Global Vel Dist=  1 , 1 , 1
Global Log Level= 0
CheckData=True
Encroach Param= -1, 0, 0, 0
BEGIN DESCRIPTION:
Multiple Run
END DESCRIPTION:

--- STEEPHOLLOWBRANCH.f01 (steady flow) ---

Flow Title=Multiple
Program Version=4.10
Number of Profiles= 7
Profile Names=10-year,25-year,50-year,1pct_min,100-year,1pct_plu,500-year
River Rch & RM=UNT05248 IN WICK,Reach-1         ,3585
     182     229     264     226     305     413     406
River Rch & RM=STEEPHOLLOWBRTR3,Reach-1         ,3585
     182     229     264     226     305     413     406
Boundary for River Rch & Prof#=STEEPHOLLOWBRTR3,Reach-1         , 1
Up Type= 0
Dn Type= 3
Dn Slope=0.005
Boundary for River Rch & Prof#=STEEPHOLLOWBRTR3,Reach-1         , 2
Up Type= 0
Dn Type= 3
Dn Slope=0.005
Boundary for River Rch & Prof#=STEEPHOLLOWBRTR3,Reach-1         , 3
Up Type= 0
Dn Type= 3
Dn Slope=0.005
Boundary for River Rch & Prof#=STEEPHOLLOWBRTR3,Reach-1         , 4
Up Type= 0
Dn Type= 3
Dn Slope=0.005
Boundary for River Rch & Prof#=STEEPHOLLOWBRTR3,Reach-1         , 5
Up Type= 0
Dn Type= 3
Dn Slope=0.005
Boundary for River Rch & Prof#=STEEPHOLLOWBRTR3,Reach-1         , 6
Up Type= 0
Dn Type= 3
Dn Slope=0.005
Boundary for River Rch & Prof#=STEEPHOLLOWBRTR3,Reach-1         , 7
Up Type= 0
Dn Type= 3
Dn Slope=0.005
DSS Import GetInterval= 0
DSS Import GetPeak= 0
DSS Import FillOption= 0

--- STEEPHOLLOWBRANCH.g01 (geometry) ---

Geom Title=Existing Conditions
Program Version=4.10

River Reach=STEEPHOLLOWBRTR3,Reach-1
Reach XY= 30
      3574945.49     10238974.15      3574942.88     10239155.13
      3574996.27     10239368.68      3574973.58     10239565.72
      3574913.14     10239679.33      3574957.41      10239726.2
      3574965.22     10239845.99      3575082.41     10240024.38
      3575058.47     10240097.28      3575081.91     10240148.06
       3575064.9     10240208.07      3575098.04     10240249.64
      3575057.67     10240418.91      3575121.47     10240620.73
      3575045.95     10240804.33      3574970.43     10240800.42
      3574910.54     10240847.29      3574861.06      10240852.5
      3574611.85     10241068.63      3574587.11     10241126.16
      3574562.79      10241281.7      3574590.59     10241341.86
      3574590.12     10241436.15      3574475.18     10241533.31
        3574460.      10241745.9      3574365.91     10241856.78
      3574428.67     10241982.43      3574498.61     10242033.22
      3574473.86     10242176.05      3574502.11     10242201.64

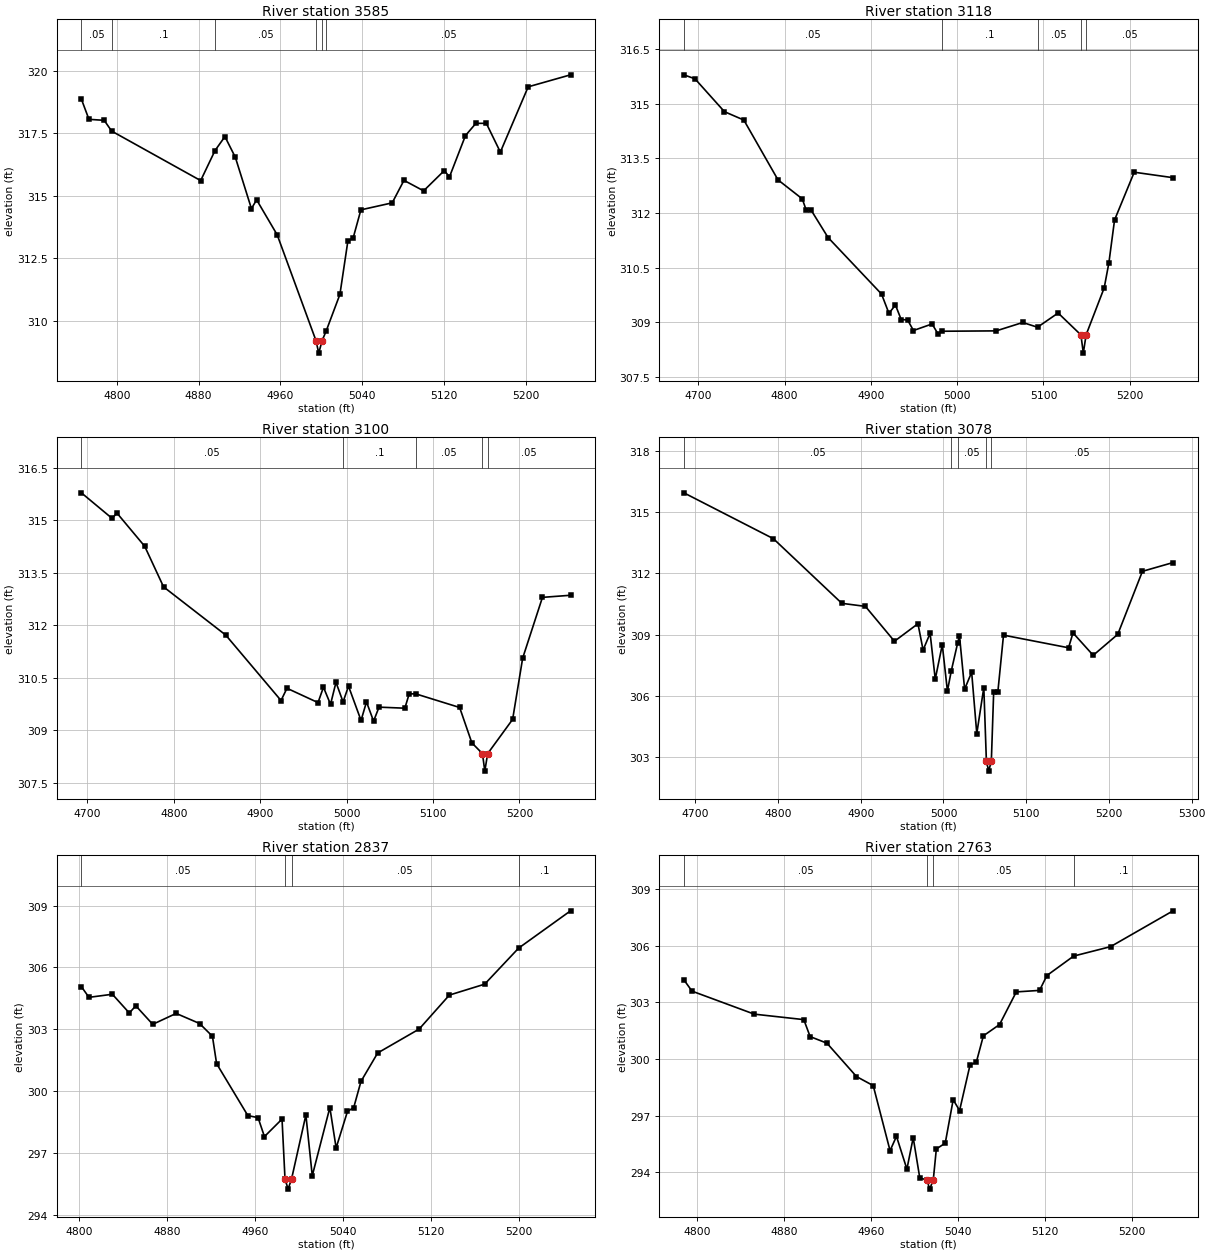
Type RM Length L Ch R = 1 ,3585    ,467,467,467
BEGIN DESCRIPTION:
UNT05248 IN WICK 7.0
END DESCRIPTION:
XS GIS Cut Line= 2
      3574714.86     10239211.18      3575182.58     10239112.08
#Sta/Elev= 30
  4765.4  318.87  4772.8  318.06  4787.7  318.02    4795  317.59    4882  315.61
    4896  316.81  4905.7  317.37  4915.9  316.54  4931.6  314.49  4936.7  314.84
  4956.8  313.44  4994.7  309.21  4997.4  308.71  5000.7  309.21  5004.8  309.61
  5018.1  311.06  5025.9   313.2    5031  313.31  5038.6  314.44  5069.2  314.72
  5080.7  315.62  5099.9   315.2  5120.1  316.01  5125.2  315.76  5140.8  317.41
    5151   317.9  5161.2   317.9  5174.9  316.75  5202.1  319.36  5243.5  319.84
#Mann= 6 ,-1 , 0
  4765.4     .05       0    4795      .1       0    4896     .05       0
  4994.7     .07       0  5000.7     .05       0  5004.8     .05       0
Bank Sta=4994.7,5000.7
XS Rating Curve= 0 ,0
Exp/Cntr=0.3,0.1

Type RM Length L Ch R = 1 ,3118    ,18,18,18
BEGIN DESCRIPTION:
Mapping XS f2ade8ea
END DESCRIPTION:
XS GIS Cut Line= 6
       3574690.5     10239428.21      3574818.96     10239490.71
      3574884.93     10239546.27      3574957.85     10239626.13
      3575039.45     10239643.49      3575174.83     10239587.95
#Sta/Elev= 30
  4683.2  315.79  4696.1  315.68  4730.2  314.78  4752.7  314.55  4792.3  312.91
  4820.4  312.39    4825  312.08  4830.7  312.08  4850.3  311.33  4912.3  309.78
  4920.9  309.25  4928.4  309.48  4935.1  309.08  4942.5  309.07  4949.3  308.78
  4970.9  308.96  4977.7  308.69    4982  308.76  5045.2  308.77    5076     309
  5093.1  308.87    5117  309.26  5143.4  308.66  5146.2  308.16  5149.4  308.66
  5170.4  309.95  5175.8  310.63  5182.4  311.81  5205.2  313.12  5250.2  312.97
#Mann= 5 ,-1 , 0
  4683.2     .05       0    4982      .1       0  5093.1     .05       0
  5143.4     .07       0  5149.4     .05       0
Bank Sta=5143.4,5149.4
XS Rating Curve= 0 ,0
Exp/Cntr=0.3,0.1

Type RM Length L Ch R = 1 ,3100    ,22,22,22
BEGIN DESCRIPTION:
Mapping XS 2ccd08ce
END DESCRIPTION:
XS GIS Cut Line= 6
      3574686.99     10239449.03      3574825.91     10239525.43
      3574886.67     10239589.67        3574970.      10239653.9
      3575055.07     10239662.58      3575173.09     10239612.25
#Sta/Elev= 30
  4693.1  315.79  4728.6  315.06  4734.3  315.21  4766.4  314.26  4788.2   313.1
  4860.2  311.72  4924.1  309.85    4931   310.2  4966.9  309.79  4973.2  310.23
  4981.4  309.74  4987.7  310.37  4995.9  309.81  5002.2  310.26  5016.7  309.28
    5023  309.81  5031.2  309.26  5037.5  309.66  5067.4  309.63  5072.4  310.04
    5080  310.04  5130.8  309.65  5144.9  308.64  5157.2  308.33  5159.9  307.83
  5163.2  308.33  5192.1  309.31  5203.7  311.06  5226.6   312.8  5259.1  312.86
#Mann= 5 ,-1 , 0
  4693.1     .05       0  4995.9      .1       0    5080     .05       0
  5157.2     .07       0  5163.2     .05       0
Bank Sta=5157.2,5163.2
XS Rating Curve= 0 ,0
Exp/Cntr=0.3,0.1

Type RM Length L Ch R = 1 ,3078    ,241,241,241
BEGIN DESCRIPTION:
UNT05248 IN WICK 6.0
END DESCRIPTION:
XS GIS Cut Line= 6
      3574666.19     10239473.35      3574817.23     10239541.06
      3574884.93     10239617.45      3574975.21     10239683.42
      3575055.07     10239679.95      3575177.73     10239631.57
#Sta/Elev= 30
  4686.3  315.95  4794.5   313.7  4877.2  310.53  4905.7  310.38  4940.8  308.67
  4969.2  309.53  4975.4  308.24  4983.9  309.06  4990.1  306.81  4998.6   308.5
  5004.8  306.23  5009.5  307.22  5017.1  308.57  5019.4  308.94  5025.6  306.32
  5034.1  307.15  5040.3  304.14  5048.8   306.4  5051.9   302.8  5054.7   302.3
  5057.9   302.8  5060.7  306.16  5065.7  306.16  5072.6  308.97  5151.2  308.35
  5156.6  309.08    5181  307.98  5210.7  309.01  5240.5   312.1  5277.5  312.53
#Mann= 5 ,-1 , 0
  4686.3     .05       0  5009.5      .1       0  5017.1     .05       0
  5051.9     .03       0  5057.9     .05       0
Bank Sta=5051.9,5057.9
XS Rating Curve= 0 ,0
Exp/Cntr=0.3,0.1

Type RM Length L Ch R = 1 ,2837    ,74,74,74
BEGIN DESCRIPTION:
Mapping XS c8ea850b
END DESCRIPTION:
XS GIS Cut Line= 3
      3574802.42     10239961.02      3574903.96     10239898.53
      3575188.77     10239740.59
#Sta/Elev= 30
    4802  305.07  4808.9  304.55  4830.2   304.7  4845.6  303.79  4851.5  304.14
  4866.9  303.24  4888.2  303.77  4909.5  303.28  4921.2  302.66    4925  301.33
  4953.4  298.81  4962.7  298.71  4968.5  297.79  4984.5  298.64  4987.2  295.74
    4990  295.24  4993.2  295.74  5006.2  298.84    5012  295.89    5028   299.2
  5033.7  297.24    5044  299.01  5049.7   299.2  5056.3  300.47  5071.5  301.85
  5109.2  303.01  5136.7  304.66  5168.8  305.19  5199.7  306.94  5246.9  308.75
#Mann= 4 ,-1 , 0
    4802     .05       0  4987.2     .04       0  4993.2     .05       0
  5199.7      .1       0
Bank Sta=4987.2,4993.2
XS Rating Curve= 0 ,0
Exp/Cntr=0.3,0.1

Type RM Length L Ch R = 1 ,2763    ,270,270,270
BEGIN DESCRIPTION:
Mapping XS d4dc9368
END DESCRIPTION:
XS GIS Cut Line= 3
      3574828.41     10240039.17      3574911.77     10239984.47
      3575211.24     10239802.18
#Sta/Elev= 30
  4787.9   304.2  4795.4   303.6  4852.7  302.38  4898.3  302.09  4904.1  301.19
  4919.6  300.84  4946.8  299.07  4962.2  298.59  4977.7  295.14  4983.6   295.9
  4993.2  294.16    4999  295.83  5005.1  293.68  5011.5   293.6  5014.2   293.1
  5017.5   293.6  5020.3  295.23  5028.5  295.54  5035.8  297.84  5041.7  297.27
  5051.3  299.68  5057.1  299.83  5063.6  301.23  5078.5  301.83  5093.9  303.56
  5115.3  303.64  5122.1  304.43  5146.7  305.46  5180.7  305.96  5238.2  307.86
#Mann= 4 ,-1 , 0
  4787.9     .05       0  5011.5     .03       0  5017.5     .05       0
  5146.7      .1       0
Bank Sta=5011.5,5017.5
XS Rating Curve= 0 ,0
Exp/Cntr=0.3,0.1

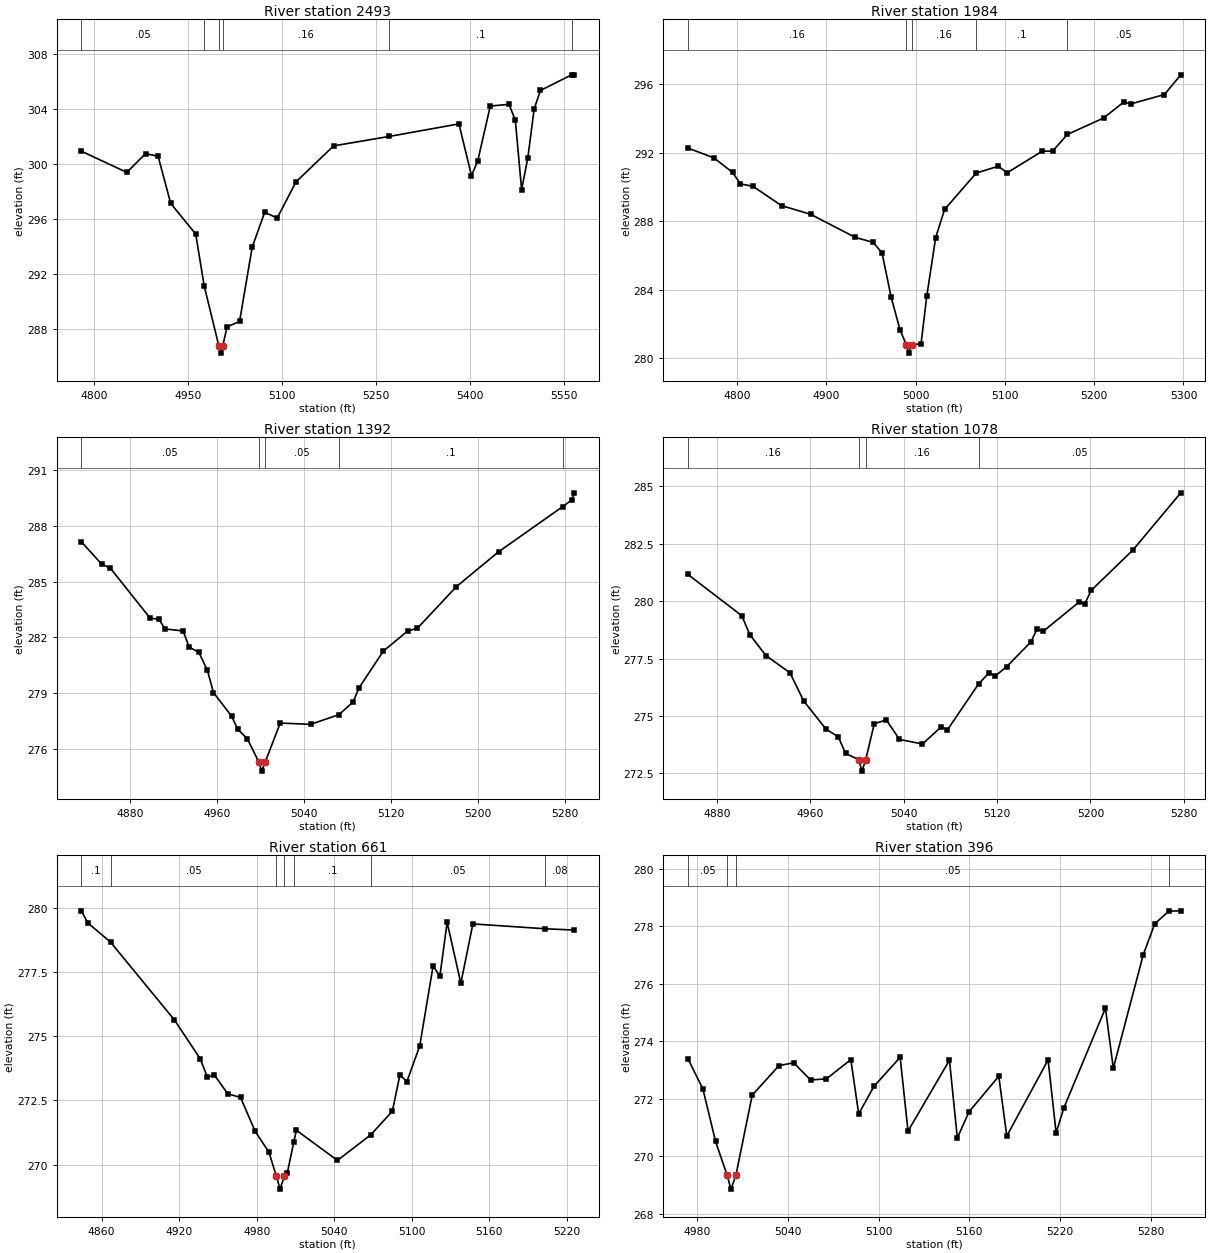
Type RM Length L Ch R = 1 ,2493    ,509,509,509
BEGIN DESCRIPTION:
UNT05248 IN WICK 5.0
END DESCRIPTION:
XS GIS Cut Line= 2
      3574859.67     10240156.34      3575646.17     10240156.34
#Sta/Elev= 30
  4779.6  300.91    4852  299.37    4882  300.74    4902  300.54    4922  297.12
    4962  294.88  4975.4  291.13    4999  286.72  5001.8  286.22    5005  286.72
    5012  288.13    5032  288.53    5052  293.91    5072  296.47    5092  296.05
    5122  298.68    5182   301.3  5271.1  301.99    5382   302.9    5402  299.14
    5412   300.2    5432   304.2    5462  304.32    5472  303.16    5482  298.12
    5492  300.45    5502  303.98    5512  305.33  5561.8  306.47  5566.1  306.47
#Mann= 6 ,-1 , 0
  4779.6     .05       0  4975.4     .16       0    4999     .07       0
    5005     .16       0  5271.1      .1       0  5561.8     .05       0
Bank Sta=4999,5005
XS Rating Curve= 0 ,0
Exp/Cntr=0.3,0.1

Type RM Length L Ch R = 1 ,1984    ,593,593,593
BEGIN DESCRIPTION:
UNT05248 IN WICK 4.0
END DESCRIPTION:
XS GIS Cut Line= 4
      3574911.77     10240531.34      3574971.67     10240619.89
      3575265.94     10240632.91       3575397.9     10240560.46
#Sta/Elev= 30
    4745  292.27    4774   291.7    4795  290.85  4803.9  290.18  4817.8  290.04
  4849.9  288.91  4882.4  288.41  4932.4  287.06  4952.4  286.77  4962.4  286.16
  4972.5   283.6  4982.5  281.68  4989.5  280.81  4992.2  280.31  4995.5  280.81
  5006.1  280.85  5012.5  283.62  5022.5  287.05  5032.5  288.69  5067.9  290.81
  5092.6  291.21  5102.6  290.83    5142  292.09  5153.5  292.09  5169.9  293.06
  5210.5  294.02  5233.4  294.96  5240.8  294.84  5278.7  295.39    5297  296.54
#Mann= 5 ,-1 , 0
    4745     .16       0  4989.5     .07       0  4995.5     .16       0
  5067.9      .1       0  5169.9     .05       0
Bank Sta=4989.5,4995.5
XS Rating Curve= 0 ,0
Exp/Cntr=0.3,0.1

Type RM Length L Ch R = 1 ,1392    ,313,313,313
BEGIN DESCRIPTION:
Mapping XS 0d389ea2
END DESCRIPTION:
XS GIS Cut Line= 2
      3574565.43     10240903.74      3574971.41     10241106.73
#Sta/Elev= 30
  4835.1  287.14  4853.7  285.94  4861.6  285.73  4898.5  283.02  4906.4  282.98
    4912  282.45  4928.7  282.34  4934.3  281.47  4943.2  281.19  4951.1  280.22
  4956.7  279.02  4973.4  277.75    4979  277.05  4987.9  276.53  4998.4  275.29
  5001.1  274.79  5004.4  275.29  5018.2  277.38  5046.1  277.31  5072.2  277.83
  5085.2  278.51  5090.8  279.28  5113.2  281.26  5135.6  282.34  5144.4  282.48
  5180.3  284.72  5219.4  286.61  5278.4  289.04  5286.5  289.39    5289  289.78
#Mann= 5 ,-1 , 0
  4835.1     .05       0  4998.4     .03       0  5004.4     .05       0
  5072.2      .1       0  5278.4     .05       0
Bank Sta=4998.4,5004.4
XS Rating Curve= 0 ,0
Exp/Cntr=0.3,0.1

Type RM Length L Ch R = 1 ,1078    ,417,417,417
BEGIN DESCRIPTION:
UNT05248 IN WICK 3.0
END DESCRIPTION:
XS GIS Cut Line= 2
      3574427.36     10241203.21      3574836.55      10241306.8
#Sta/Elev= 30
  4855.3  281.16  4901.5  279.36  4908.3  278.54  4922.1  277.63  4942.7  276.88
  4954.5  275.65  4973.7  274.42    4984   274.1  4990.3  273.37  5001.6   273.1
  5004.4   272.6  5007.6   273.1  5014.9  274.66  5025.2  274.83  5036.5  273.98
  5056.2  273.78  5072.3  274.53  5077.5  274.39  5104.3   276.4  5113.3  276.88
  5118.5  276.74  5128.4  277.15    5149  278.22  5154.3  278.78  5159.5  278.68
  5190.2  279.95  5195.3  279.89  5200.6  280.46  5236.4  282.22  5277.4  284.71
#Mann= 4 ,-1 , 0
  4855.3     .16       0  5001.6     .07       0  5007.6     .16       0
  5104.3     .05       0
Bank Sta=5001.6,5007.6
XS Rating Curve= 0 ,0
Exp/Cntr=0.3,0.1

Type RM Length L Ch R = 1 ,661     ,322,322,322
BEGIN DESCRIPTION:
UNT05248 IN WICK 2.0
END DESCRIPTION:
XS GIS Cut Line= 2
      3574315.39     10241533.94      3574674.81     10241661.56
#Sta/Elev= 30
  4844.4   279.9  4849.3  279.43  4866.9  278.68  4916.4  275.64  4936.4  274.12
  4941.9   273.4  4947.2   273.5  4957.6  272.76  4967.5  272.62  4978.9  271.29
  4989.5  270.48  4995.3  269.54  4998.1  269.04  5001.3  269.54  5003.6  269.65
  5008.8  270.89  5010.7  271.34  5042.5  270.16  5068.3  271.16    5085  272.08
  5090.9  273.51  5096.2  273.23  5106.2  274.63  5116.5  277.74  5121.8  277.36
  5127.4  279.45    5138  277.07  5147.3  279.39  5203.1   279.2  5225.8  279.15
#Mann= 7 ,-1 , 0
  4844.4      .1       0  4866.9     .05       0  4995.3     .03       0
  5001.3     .05       0  5008.8      .1       0  5068.3     .05       0
  5203.1     .08       0
Bank Sta=4995.3,5001.3
XS Rating Curve= 0 ,0
Exp/Cntr=0.3,0.1

Type RM Length L Ch R = 1 ,396     ,12,12,12
BEGIN DESCRIPTION:
Mapping XS a96cc794
END DESCRIPTION:
XS GIS Cut Line= 2
      3574344.59     10241878.61      3574655.82     10241782.25
#Sta/Elev= 30
    4974  273.39  4983.9  272.34  4992.3  270.51  4999.8  269.35  5002.5  268.85
  5005.8  269.35  5016.5  272.12  5034.2  273.15  5043.9  273.25  5055.1  272.65
  5065.6  272.69  5081.7  273.36  5086.9  271.47    5097  272.43  5114.3  273.44
  5119.5  270.87  5146.9  273.34  5152.1  270.63  5159.8  271.54  5179.5  272.78
  5184.8   270.7  5212.1  273.35  5217.4  270.81  5222.6  271.69    5250  275.15
  5255.2  273.06    5275  277.01  5282.6  278.09  5291.9  278.53  5299.8  278.54
#Mann= 4 ,-1 , 0
    4974     .05       0  4999.8     .03       0  5005.8     .05       0
  5291.9     .08       0
Bank Sta=4999.8,5005.8
XS Rating Curve= 0 ,0
Exp/Cntr=0.3,0.1

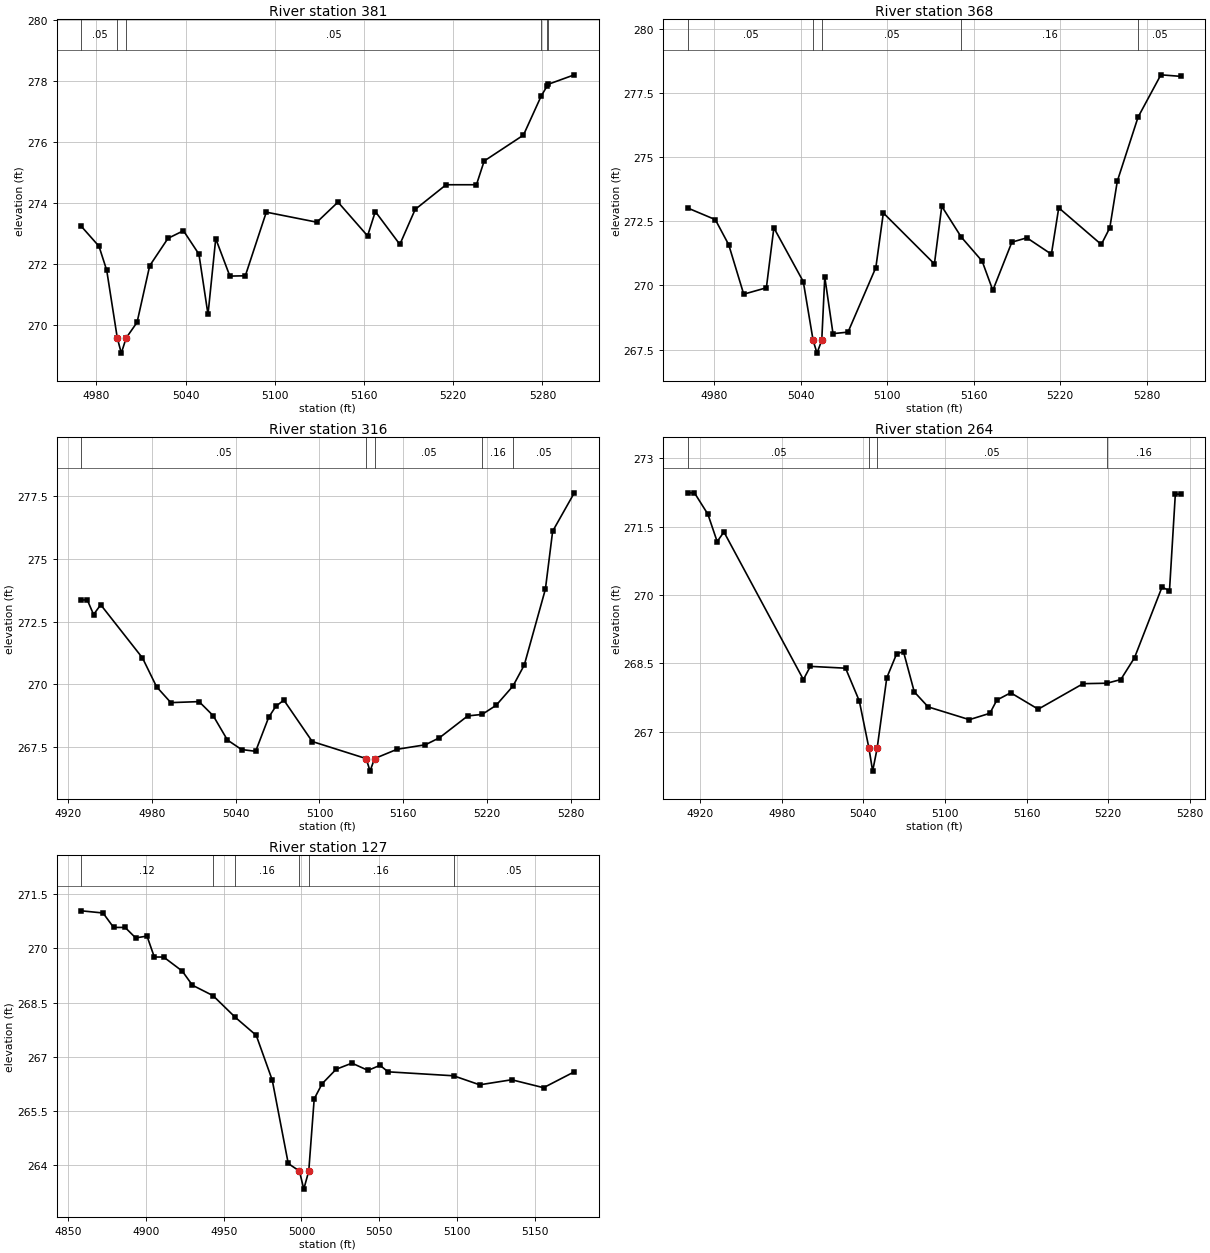
Type RM Length L Ch R = 1 ,381     ,11,11,11
BEGIN DESCRIPTION:
Mapping XS ee0d2a53
END DESCRIPTION:
XS GIS Cut Line= 2
      3574346.06     10241889.95      3574665.05     10241800.11
#Sta/Elev= 30
    4970  273.22  4981.8  272.57    4987  271.78  4994.1  269.56  4996.8  269.06
  5000.1  269.56  5007.4  270.07  5015.9  271.93  5028.2  272.83  5038.6  273.08
    5049  272.31  5055.1  270.33  5060.3  272.82  5069.8  271.59  5080.2   271.6
  5094.3  273.69  5128.3  273.36  5142.5  274.02  5162.4  272.91  5167.6  273.71
  5184.1  272.63  5194.4  273.78  5215.2  274.59  5235.6  274.59  5240.8  275.37
  5267.2  276.22  5279.2  277.51  5283.1  277.83  5283.9  277.89  5301.4   278.2
#Mann= 6 ,-1 , 0
    4970     .05       0  4994.1     .03       0  5000.1     .05       0
  5279.2     .16       0  5283.1     .05       0  5283.9     .08       0
Bank Sta=4994.1,5000.1
XS Rating Curve= 0 ,0
Exp/Cntr=0.3,0.1

Type RM Length L Ch R = 1 ,368     ,46,46,46
BEGIN DESCRIPTION:
Mapping XS 8c75d5e8
END DESCRIPTION:
XS GIS Cut Line= 2
      3574344.69     10241900.38      3574675.41     10241814.45
#Sta/Elev= 30
  4961.9  273.02  4980.9  272.57  4990.2  271.59  5000.6  269.66  5016.3  269.91
  5021.5  272.25  5041.9  270.15  5048.7  267.86  5051.4  267.36  5054.7  267.86
  5056.8  270.33  5062.5  268.12  5072.9  268.18  5092.2   270.7  5097.4  272.83
  5132.8  270.84  5137.9  273.09  5151.4  271.89  5165.9  270.95  5173.3  269.81
  5186.5  271.69  5196.9  271.86  5213.9  271.22    5219  273.03  5248.5   271.6
  5254.4  272.25  5259.6  274.07    5274  276.57  5289.8  278.22  5303.6  278.16
#Mann= 5 ,-1 , 0
  4961.9     .05       0  5048.7     .03       0  5054.7     .05       0
  5151.4     .16       0    5274     .05       0
Bank Sta=5048.7,5054.7
XS Rating Curve= 0 ,0
Exp/Cntr=0.3,0.1

Type RM Length L Ch R = 1 ,316     ,53,53,53
BEGIN DESCRIPTION:
Mapping XS 188e2160
END DESCRIPTION:
XS GIS Cut Line= 2
      3574338.91     10241938.05      3574687.45     10241883.43
#Sta/Elev= 30
  4929.6  273.36  4933.8  273.36  4938.3  272.78  4943.4  273.17  4973.3  271.05
  4983.4   269.9  4993.6  269.27  5013.8  269.31  5023.9  268.75  5034.1  267.78
  5044.2   267.4  5054.3  267.33  5063.6  268.68  5068.7  269.12  5074.5  269.37
  5094.8  267.72  5133.4  267.04  5136.2  266.54  5139.4  267.04  5155.5  267.41
  5175.8  267.59  5185.9  267.87  5206.1  268.74  5216.4   268.8  5226.4  269.16
  5238.5  269.93  5246.6  270.77  5261.7  273.79  5266.9   276.1  5282.4  277.63
#Mann= 5 ,-1 , 0
  4929.6     .05       0  5133.4     .03       0  5139.4     .05       0
  5216.4     .16       0  5238.5     .05       0
Bank Sta=5133.4,5139.4
XS Rating Curve= 0 ,0
Exp/Cntr=0.3,0.1

Type RM Length L Ch R = 1 ,264     ,161,161,161
BEGIN DESCRIPTION:
Mapping XS 561864d5
END DESCRIPTION:
XS GIS Cut Line= 2
      3574337.57     10241990.14      3574695.72     10241935.44
#Sta/Elev= 30
  4911.1  272.24  4915.9  272.24  4925.8  271.77  4932.6  271.17  4937.6  271.38
    4996  268.14  5001.1  268.43    5027  268.39  5037.1  267.67  5044.2  266.63
  5046.9  266.13  5050.2  266.63  5057.3  268.18  5064.6  268.71  5069.6  268.75
  5077.5  267.87  5087.7  267.54    5118  267.26  5133.1   267.4  5138.2  267.69
  5148.4  267.85  5168.6  267.49  5201.6  268.05  5219.1  268.06  5229.3  268.14
  5239.4  268.62  5259.6  270.17  5265.1  270.09  5269.4  272.21  5273.4  272.21
#Mann= 4 ,-1 , 0
  4911.1     .05       0  5044.2     .03       0  5050.2     .05       0
  5219.1     .16       0
Bank Sta=5044.2,5050.2
XS Rating Curve= 0 ,0
Exp/Cntr=0.3,0.1

Type RM Length L Ch R = 1 ,127     ,0,0,0
BEGIN DESCRIPTION:
UNT05248 IN WICK 1.0
END DESCRIPTION:
XS GIS Cut Line= 3
      3574357.15     10242037.02      3574390.99     10242073.47
      3574651.36     10242134.66
#Sta/Elev= 30
  4858.4  271.04  4872.3  270.98  4879.1  270.58  4886.5  270.58  4893.3  270.29
  4900.6  270.34  4905.3  269.76  4911.3  269.76  4923.3  269.37  4929.8  268.98
  4943.1  268.69  4957.4  268.09  4970.9  267.59  4981.2  266.35  4991.5  264.04
  4998.7  263.83  5001.5  263.33  5004.7  263.83  5008.2  265.83  5013.3  266.25
  5022.3  266.65  5032.5  266.82  5042.8  266.62  5050.6  266.76  5055.7  266.58
  5097.9  266.47  5114.7  266.22  5135.3  266.36  5155.8  266.14  5175.6  266.58
#Mann= 6 ,-1 , 0
  4858.4     .12       0  4943.1     .05       0  4957.4     .16       0
  4998.7     .07       0  5004.7     .16       0  5097.9     .05       0
Bank Sta=4998.7,5004.7
XS Rating Curve= 0 ,0
Exp/Cntr=0.3,0.1
Stream Node=UNT05248 IN WICK,Reach-1         , 0 , 0 ,Upstream end
Stream Node=UNT05248 IN WICK,Reach-1         , 0 , 1 ,Downstream end

Chan Stop Cuts=-1
Use User Specified Reach Order=0
Composite Channel Slope=5