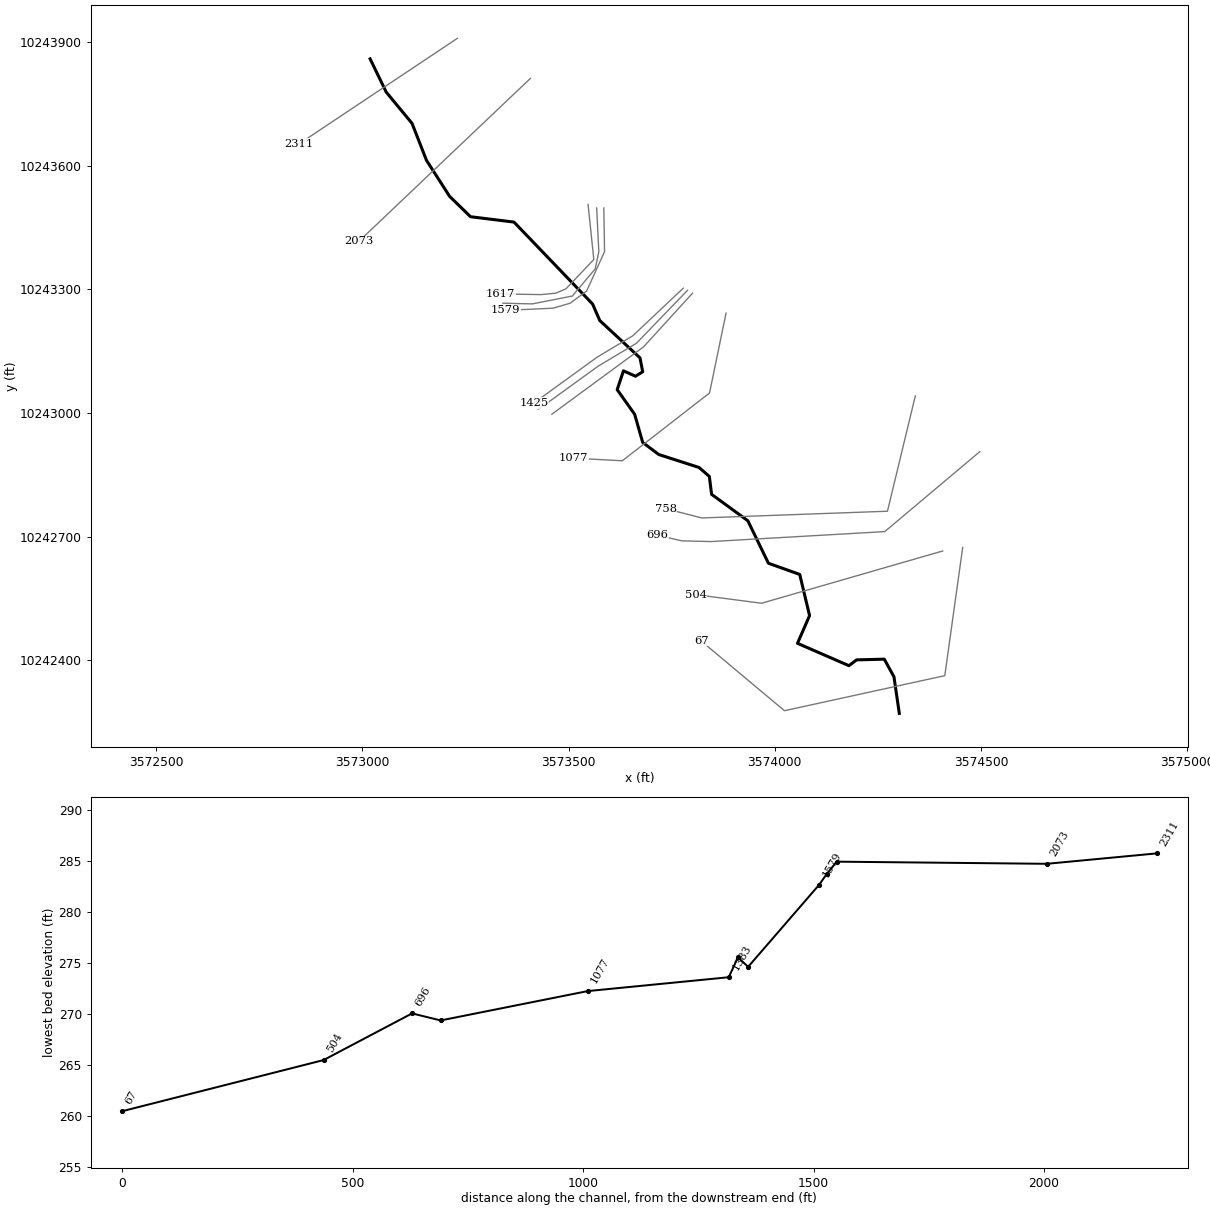
--- STEEPHOLLOWBRANCH.prj (project) ---

Proj Title=STEEP HOLLOW BRANCH TRIB 4
Current Plan=p01
Default Exp/Contr=0.3,0.1
English Units
Geom File=g01
Flow File=f01
Plan File=p01
Y Axis Title=Elevation
X Axis Title(PF)=Main Channel Distance
X Axis Title(XS)=Station
BEGIN DESCRIPTION:
UNT05247 IN WICK
END DESCRIPTION:
DSS Export Rating Curves= 0
DSS Export Rating Curve Sorted= 0
DSS Export Volume Flow Curves= 0
DXF Filename=UNT05247 IN WICK.
DXF OffsetX= 0
DXF OffsetY= 0
DXF ScaleX= 1
DXF ScaleY= 10

--- STEEPHOLLOWBRANCH.p01 (plan) ---

Plan Title=Multiple Run
Short Identifier=Multiple
Geom File=g01
Flow File=f01
Subcritical Flow
K Sum by GR= 0
Std Step Tol= 0.01
Critical Tol= 0.01
Num of Std Step Trials= 20
Max Error Tol= 0.3
Flow Tol Ratio= 0.001
Split Flow NTrial= 30
Split Flow Tol= 0.02
Split Flow Ratio= 0.02
Log Output Level= 0
Friction Slope Method= 1
Unsteady Friction Slope Method= 2
Unsteady Bridges Friction Slope Method= 1
Parabolic Critical Depth
Global Vel Dist=  1 , 1 , 1
Global Log Level= 0
CheckData=True
Encroach Param= -1, 0, 0, 0
BEGIN DESCRIPTION:
Multiple Run
END DESCRIPTION:

--- STEEPHOLLOWBRANCH.f01 (steady flow) ---

Flow Title=Multiple
Program Version=4.10
Number of Profiles= 7
Profile Names=10-year,25-year,50-year,1pct_min,100-year,1pct_plu,500-year
River Rch & RM=UNT05247 IN WICK,Reach-1         ,2311
     134     165     187     157     212     287     273
River Rch & RM=STEEPHOLLOWBRTR4,Reach-1         ,2311
     134     165     187     157     212     287     273
Boundary for River Rch & Prof#=STEEPHOLLOWBRTR4,Reach-1         , 1
Up Type= 0
Dn Type= 3
Dn Slope=0.005
Boundary for River Rch & Prof#=STEEPHOLLOWBRTR4,Reach-1         , 2
Up Type= 0
Dn Type= 3
Dn Slope=0.005
Boundary for River Rch & Prof#=STEEPHOLLOWBRTR4,Reach-1         , 3
Up Type= 0
Dn Type= 3
Dn Slope=0.005
Boundary for River Rch & Prof#=STEEPHOLLOWBRTR4,Reach-1         , 4
Up Type= 0
Dn Type= 3
Dn Slope=0.005
Boundary for River Rch & Prof#=STEEPHOLLOWBRTR4,Reach-1         , 5
Up Type= 0
Dn Type= 3
Dn Slope=0.005
Boundary for River Rch & Prof#=STEEPHOLLOWBRTR4,Reach-1         , 6
Up Type= 0
Dn Type= 3
Dn Slope=0.005
Boundary for River Rch & Prof#=STEEPHOLLOWBRTR4,Reach-1         , 7
Up Type= 0
Dn Type= 3
Dn Slope=0.005
DSS Import GetInterval= 0
DSS Import GetPeak= 0
DSS Import FillOption= 0

--- STEEPHOLLOWBRANCH.g01 (geometry) ---

Geom Title=Existing Conditions
Program Version=4.10

River Reach=STEEPHOLLOWBRTR4,Reach-1
Reach XY= 30
      3573018.72     10243858.98      3573057.78     10243778.25
      3573120.28     10243702.73      3573155.44     10243612.88
      3573211.43     10243525.64      3573262.21     10243476.16
      3573367.68     10243463.14       3573558.3     10243264.35
      3573575.66     10243224.41      3573673.25     10243133.81
      3573679.76     10243100.17       3573662.4     10243089.32
       3573633.1     10243102.34      3573617.91     10243056.77
      3573660.23     10242997.09      3573679.76     10242928.73
      3573718.82     10242899.43      3573816.48     10242867.96
      3573841.43     10242846.26      3573846.86     10242802.86
      3573934.75     10242738.84      3573984.66     10242635.76
      3574060.62     10242608.63      3574084.49     10242508.81
      3574055.19     10242441.53      3574179.98     10242387.28
      3574198.42     10242401.38      3574265.68     10242403.13
      3574289.14     10242360.41      3574302.11     10242271.64

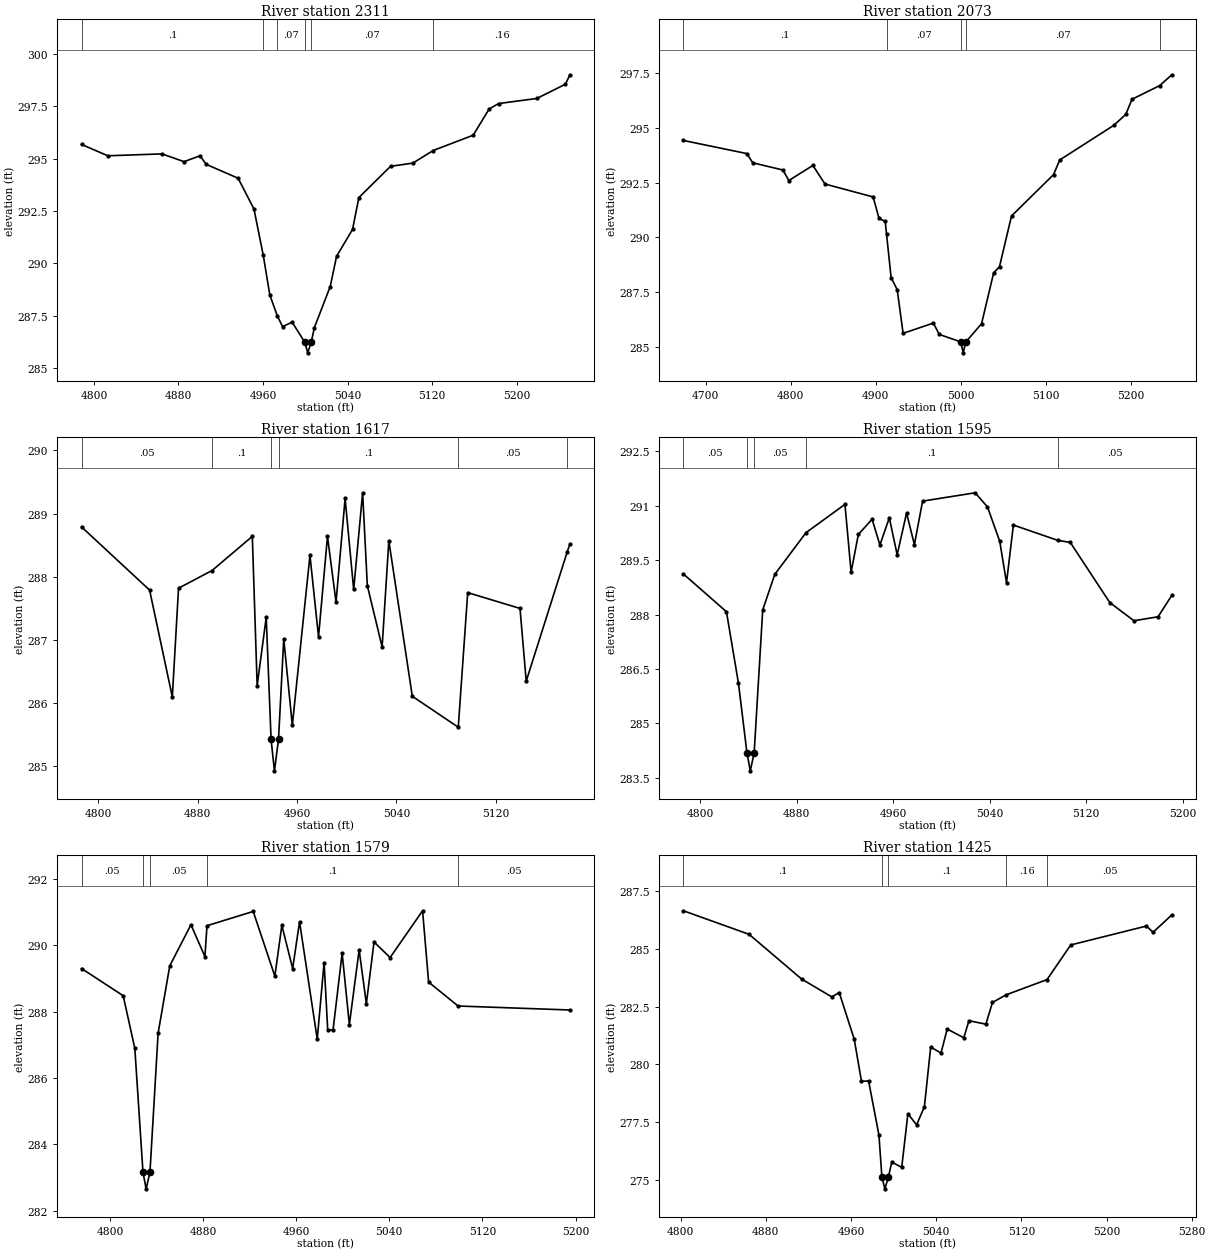
Type RM Length L Ch R = 1 ,2311    ,238,238,238
BEGIN DESCRIPTION:
UNT05247 IN WICK 5.0
END DESCRIPTION:
XS GIS Cut Line= 2
      3573230.31     10243908.79      3572845.99     10243652.57
#Sta/Elev= 30
  4788.3  295.67  4813.2  295.13  4864.3  295.22  4885.3  294.85  4900.3  295.13
  4906.3  294.72  4936.4  294.06  4951.4  292.59  4960.2  290.38  4966.4  288.49
  4973.4  287.51  4978.4  286.99  4987.5   287.2  4999.5  286.24  5002.2  285.74
  5005.5  286.24  5008.5  286.94  5023.5   288.9  5029.5  290.34  5044.6  291.62
  5050.6  293.14  5080.6  294.63  5101.6  294.78  5120.8  295.38  5158.7  296.11
  5173.8  297.36  5182.8  297.62  5218.8  297.86  5245.9  298.54  5250.2  298.99
#Mann= 6 ,-1 , 0
  4788.3      .1       0  4960.2     .16       0  4973.4     .07       0
  4999.5     .07       0  5005.5     .07       0  5120.8     .16       0
Bank Sta=4999.5,5005.5
XS Rating Curve= 0 ,0
Exp/Cntr=0.3,0.1

Type RM Length L Ch R = 1 ,2073    ,456,456,456
BEGIN DESCRIPTION:
UNT05247 IN WICK 4.0
END DESCRIPTION:
XS GIS Cut Line= 2
       3573407.4     10243811.57      3572991.25     10243416.23
#Sta/Elev= 30
  4673.8  294.42  4748.4  293.82  4755.3   293.4  4790.8  293.07  4797.7  292.59
    4826  293.28  4840.2  292.43  4896.8  291.84  4903.7  290.86    4911  290.72
  4912.5  290.16  4917.9  288.16  4925.1   287.6    4932  285.61  4967.6  286.08
  4974.5  285.56  4999.8  285.22  5002.6  284.72  5005.8  285.22  5024.2  286.05
  5038.4  288.37  5045.3  288.66  5059.4  290.97  5108.8  292.86  5116.1  293.53
  5179.6  295.11  5193.7  295.61    5201   296.3  5233.7  296.93  5247.8  297.42
#Mann= 5 ,-1 , 0
  4673.8      .1       0  4912.5     .07       0  4999.8     .07       0
  5005.8     .07       0  5233.7      .1       0
Bank Sta=4999.8,5005.8
XS Rating Curve= 0 ,0
Exp/Cntr=0.3,0.1

Type RM Length L Ch R = 1 ,1617    ,22,22,22
BEGIN DESCRIPTION:
Mapping XS e7b83835
END DESCRIPTION:
XS GIS Cut Line= 6
      3573547.32     10243506.03      3573561.21     10243372.34
       3573493.5     10243301.16      3573469.19     10243290.75
      3573432.73     10243287.28      3573335.48     10243288.91
#Sta/Elev= 30
  4786.5  288.79  4841.3  287.79  4859.6   286.1  4864.6  287.82  4891.6   288.1
    4924  288.64  4927.9  286.28  4935.2  287.36  4939.1  285.43  4941.8  284.93
  4945.1  285.43  4949.3  287.02  4956.2  285.65  4970.4  288.34  4977.3  287.05
  4984.5  288.64  4991.4   287.6  4998.7  289.24  5005.6   287.8  5012.8  289.33
  5016.6  287.86  5028.5  286.89  5033.9  288.57  5052.8  286.11  5089.8  285.62
  5097.4  287.75  5139.5   287.5  5144.5  286.35  5177.6   288.4  5179.7  288.52
#Mann= 6 ,-1 , 0
  4786.5     .05       0  4891.6      .1       0  4939.1     .07       0
  4945.1      .1       0  5089.8     .05       0  5177.6      .1       0
Bank Sta=4939.1,4945.1
XS Rating Curve= 0 ,0
Exp/Cntr=0.3,0.1

Type RM Length L Ch R = 1 ,1595    ,16,16,16
BEGIN DESCRIPTION:
Mapping XS a78cdbcc
END DESCRIPTION:
XS GIS Cut Line= 6
      3573568.15     10243497.31      3573573.36     10243391.44
      3573564.68     10243349.78      3573509.12      10243283.8
       3573411.9     10243264.71      3573340.72     10243266.44
#Sta/Elev= 30
  4785.9  289.12  4821.6  288.08  4831.6   286.1  4838.6  284.19  4841.4  283.69
  4844.6  284.19  4851.7  288.13  4861.7  289.11  4887.6  290.26  4919.9  291.04
    4925  289.17    4931  290.21  4942.4  290.63  4948.9  289.92  4956.7  290.67
  4963.2  289.65    4971   290.8  4977.5  289.93  4984.3  291.13  5027.9  291.36
  5038.1  290.97  5048.3  290.02  5053.9  288.88  5059.6  290.47  5096.2  290.05
  5106.8  289.99  5139.6  288.33  5159.6  287.83  5179.6  287.94    5191  288.53
#Mann= 5 ,-1 , 0
  4785.9     .05       0  4838.6     .07       0  4844.6     .05       0
  4887.6      .1       0  5096.2     .05       0
Bank Sta=4838.6,4844.6
XS Rating Curve= 0 ,0
Exp/Cntr=0.3,0.1

Type RM Length L Ch R = 1 ,1579    ,154,154,154
BEGIN DESCRIPTION:
Mapping XS d32f3717
END DESCRIPTION:
XS GIS Cut Line= 6
      3573585.51     10243497.39      3573587.25     10243391.44
      3573543.84     10243295.96      3573503.91     10243266.44
      3573462.25     10243254.29      3573347.69     10243249.08
#Sta/Elev= 30
  4775.6   289.3  4811.4  288.48  4821.4  286.89  4828.4  283.16  4831.1  282.66
  4834.4  283.16  4841.4  287.35  4851.4  289.38  4869.6  290.62  4881.6  289.66
  4883.4  290.59  4923.1  291.02  4941.7  289.07  4947.7   290.6    4957   289.3
  4962.9  290.71  4978.1  287.17    4984  289.48  4987.1  287.45  4991.7  287.45
  4999.5  289.76  5005.7  287.61  5014.1  289.86  5020.3  288.24  5026.9   290.1
  5040.7  289.63  5068.6  291.04  5073.8  288.89  5099.1  288.17  5195.2  288.05
#Mann= 5 ,-1 , 0
  4775.6     .05       0  4828.4     .07       0  4834.4     .05       0
  4883.4      .1       0  5099.1     .05       0
Bank Sta=4828.4,4834.4
XS Rating Curve= 0 ,0
Exp/Cntr=0.3,0.1

Type RM Length L Ch R = 1 ,1425    ,22,22,22
BEGIN DESCRIPTION:
Mapping XS b4ebff83
END DESCRIPTION:
XS GIS Cut Line= 4
      3573778.04     10243302.74      3573655.66     10243187.31
      3573568.86     10243135.23      3573415.71     10243024.24
#Sta/Elev= 30
  4802.7  286.65  4864.4  285.63  4913.8  283.69  4942.1  282.92    4949  283.11
  4963.1  281.09  4969.9  279.27  4976.6  279.28  4986.3  276.94  4989.1  275.11
  4991.9  274.61  4995.1  275.11  4998.4  275.77  5007.7  275.54  5013.5  277.86
  5021.7  277.38    5029  278.17  5034.9  280.75  5044.6  280.49  5050.4  281.53
    5066  281.15  5070.8  281.89  5086.7  281.74  5092.9  282.68  5105.7  283.01
  5144.1  283.67  5166.4  285.17  5237.5  285.99  5243.7  285.72  5261.3  286.47
#Mann= 5 ,-1 , 0
  4802.7      .1       0  4989.1     .07       0  4995.1      .1       0
  5105.7     .16       0  5144.1     .05       0
Bank Sta=4989.1,4995.1
XS Rating Curve= 0 ,0
Exp/Cntr=0.3,0.1

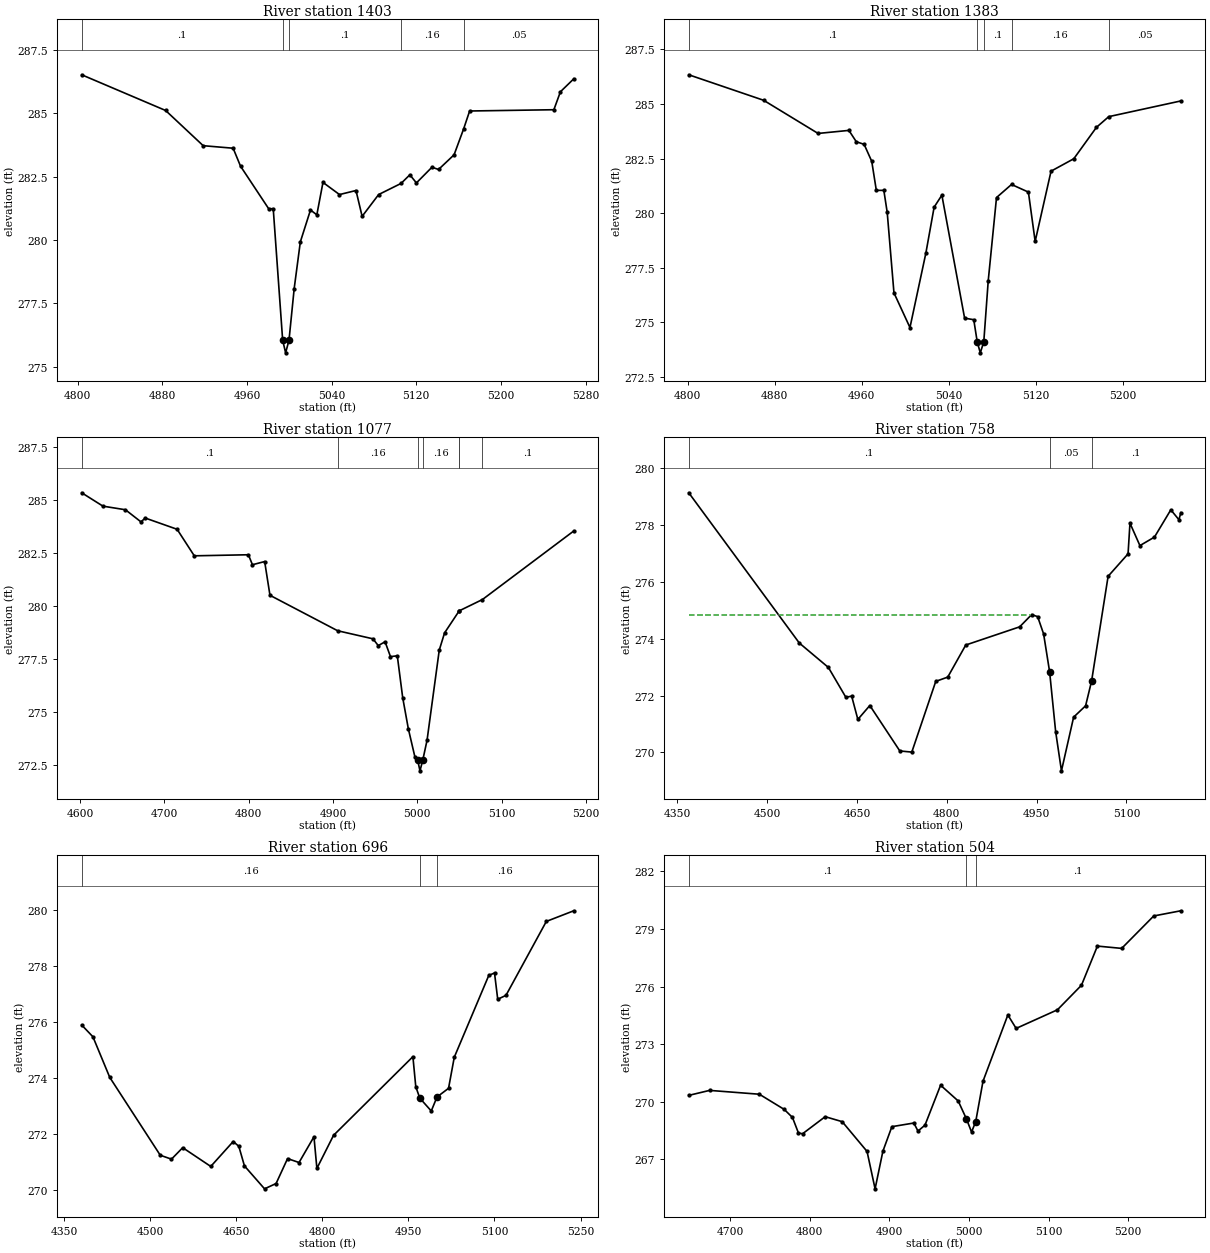
Type RM Length L Ch R = 1 ,1403    ,20,20,20
BEGIN DESCRIPTION:
Mapping XS 3b149624
END DESCRIPTION:
XS GIS Cut Line= 5
      3573788.48     10243297.56      3573664.35     10243169.08
      3573571.46     10243113.53      3573436.05     10243015.44
      3573426.84     10243009.58
#Sta/Elev= 30
  4803.9  286.52  4883.2  285.11  4918.7  283.72    4947  283.62    4954  282.91
  4980.6  281.23  4984.9  281.23  4993.8  276.04  4996.6  275.54  4999.8  276.04
  5004.7  278.08  5010.5  279.92  5020.1  281.18  5026.1  280.99  5031.9  282.27
  5047.5  281.79  5063.1  281.95  5068.9  280.93  5084.5  281.79  5105.7  282.23
    5114  282.57  5120.2  282.25  5134.9  282.87  5141.1  282.78  5155.8  283.36
  5164.8  284.38  5170.5  285.09  5250.1  285.14  5256.3  285.85  5268.9  286.36
#Mann= 5 ,-1 , 0
  4803.9      .1       0  4993.8     .07       0  4999.8      .1       0
  5105.7     .16       0  5164.8     .05       0
Bank Sta=4993.8,4999.8
XS Rating Curve= 0 ,0
Exp/Cntr=0.3,0.1

Type RM Length L Ch R = 1 ,1383    ,306,306,306
BEGIN DESCRIPTION:
UNT05247 IN WICK 3.0
END DESCRIPTION:
XS GIS Cut Line= 3
      3573800.61     10243290.59      3573681.71      10243160.4
       3573459.5     10242997.22
#Sta/Elev= 30
  4801.1  286.34  4869.9  285.17  4919.9  283.65  4948.2  283.79    4955  283.27
  4962.2  283.15  4969.2  282.37  4973.4  281.04  4980.3  281.04  4983.4  280.03
  4989.6  276.34  5004.3  274.75  5018.9  278.16  5026.5  280.27  5033.6  280.82
  5054.5  275.18  5062.9  275.11  5066.1  274.09  5068.9  273.59  5072.1  274.09
  5076.2   276.9  5083.8  280.71  5097.6  281.31  5113.1  280.96  5119.3   278.7
  5133.9  281.92  5154.8  282.49  5175.6  283.93  5186.9  284.42  5253.1  285.14
#Mann= 5 ,-1 , 0
  4801.1      .1       0  5066.1     .07       0  5072.1      .1       0
  5097.6     .16       0  5186.9     .05       0
Bank Sta=5066.1,5072.1
XS Rating Curve= 0 ,0
Exp/Cntr=0.3,0.1

Type RM Length L Ch R = 1 ,1077    ,319,319,319
BEGIN DESCRIPTION:
UNT05247 IN WICK 2.0
END DESCRIPTION:
XS GIS Cut Line= 4
      3573881.95     10243242.48      3573841.91     10243048.76
      3573630.36     10242884.27      3573512.42     10242890.56
#Sta/Elev= 30
  4601.8  285.33    4627   284.7  4653.7  284.53  4672.1  283.96  4677.2  284.14
    4715  283.61  4735.4  282.36  4799.6  282.41  4804.4  281.94  4818.9  282.09
  4825.2   280.5  4905.5  278.83  4947.4  278.45  4953.7  278.13  4961.8  278.31
  4968.2  277.61  4976.3  277.65  4982.7  275.68  4989.4  274.21  4997.1   272.9
  5000.5  272.73  5003.2  272.23  5006.5  272.73  5011.6  273.67  5026.1  277.92
  5032.4  278.73  5049.8  279.77  5049.9  279.77  5077.3   280.3  5185.7  283.53
#Mann= 7 ,-1 , 0
  4601.8      .1       0  4905.5     .16       0  5000.5     .07       0
  5006.5     .16       0  5049.8      .1       0  5049.9     .16       0
  5077.3      .1       0
Bank Sta=5000.5,5006.5
XS Rating Curve= 0 ,0
Exp/Cntr=0.3,0.1

Type RM Length L Ch R = 1 ,758     ,62,62,62
BEGIN DESCRIPTION:
Mapping XS 7636fe23
END DESCRIPTION:
XS GIS Cut Line= 4
        3574341.    10243041.745     3574273.383    10242761.901
      3573823.36     10242745.61      3573735.93     10242767.89
#Sta/Elev= 30
 4369.04  279.14 4553.64  273.85 4602.22  272.99 4631.37  271.94 4641.08  271.98
  4651.4  271.16  4671.4  271.65  4721.5  270.05  4741.5  270.01  4781.5   272.5
  4801.5  272.65  4831.6  273.78  4921.6  274.42  4941.6  274.85  4951.6  274.78
  4961.6  274.17  4971.6  272.84  4981.7  270.73  4991.4  269.35  5011.7  271.24
  5031.7  271.64  5041.7  272.51  5069.3   276.2  5102.6  276.99  5105.8  278.07
  5122.4  277.28  5146.7  277.58    5174  278.54  5187.6  278.19  5190.7  278.44
#Mann= 3 , 0 , 0
 4369.04      .1       0  4971.6     .05       0  5041.7      .1       0
#XS Ineff= 2 , 0
         4940.68  274.85
Permanent Ineff=
       F       F
Bank Sta=4971.6,5041.7
XS Rating Curve= 0 ,0
Exp/Cntr=0.3,0.1

Type RM Length L Ch R = 1 ,696     ,192,192,192
BEGIN DESCRIPTION:
Mapping XS 1b3508e7
END DESCRIPTION:
XS GIS Cut Line= 5
      3574497.25    10242906.328     3574266.847     10242712.48
      3573845.93     10242688.32      3573774.75     10242690.05
      3573715.55     10242703.58
#Sta/Elev= 30
  4380.8  275.89 4400.35  275.47 4429.69  274.02 4517.68  271.24 4537.23   271.1
 4556.79  271.51 4605.67  270.84 4644.78  271.73 4654.56  271.56 4664.34  270.86
  4699.4  270.04  4719.5  270.23  4739.5  271.12  4759.5  270.98  4785.5   271.9
  4790.6  270.77  4819.6  271.95  4957.9  274.76  4962.9  273.69  4969.9  273.28
  4989.9  272.82  4999.9  273.32    5020  273.63    5030  274.74  5090.1  277.66
  5100.1  277.75  5105.7  276.81  5120.1  276.95  5190.4  279.59  5238.2  279.97
#Mann= 3 , 0 , 0
  4380.8     .16       0  4969.9     .07       0  4999.9     .16       0
#XS Ineff= 2 , 0
         4957.04  274.74
Permanent Ineff=
       F       F
#Block Obstruct= 2 , 0
         4990.45  272.81
Bank Sta=4969.9,4999.9
XS Rating Curve= 0 ,0
Exp/Cntr=0.3,0.1

Type RM Length L Ch R = 1 ,504     ,437,437,437
BEGIN DESCRIPTION:
Mapping XS 39f40408
END DESCRIPTION:
XS GIS Cut Line= 3
      3574407.31     10242665.47      3573968.09     10242538.74
      3573808.38     10242559.57
#Sta/Elev= 30
  4647.9  270.33  4674.1  270.59  4736.6  270.39  4767.8   269.6  4778.2  269.18
  4785.7  268.37  4790.9  268.33  4819.3  269.22  4840.7  268.96  4871.9  267.41
    4882  265.46  4891.8  267.42  4903.1   268.7  4930.7  268.89  4935.9  268.47
  4944.7  268.78  4964.3  270.86  4986.4  270.04  4996.8   269.1  5003.2  268.42
  5008.4  268.96  5017.6  271.07  5048.8  274.52  5059.2  273.82  5111.1  274.79
  5141.3  276.07  5161.3  278.11  5191.8  277.99  5232.1  279.68  5266.1  279.95
#Mann= 3 , 0 , 0
  4647.9      .1       0  4996.8     .05       0  5008.4      .1       0
#Block Obstruct= 2 , 0
         5003.69  268.39
Bank Sta=4996.8,5008.4
XS Rating Curve= 0 ,0
Exp/Cntr=0.3,0.1

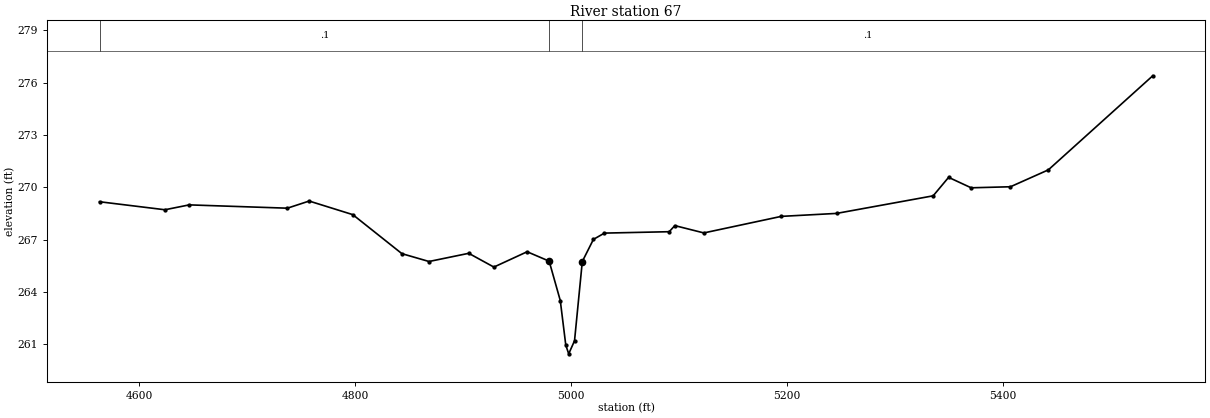
Type RM Length L Ch R = 1 ,67      ,0,0,0
BEGIN DESCRIPTION:
UNT05247 IN WICK 1.0
END DESCRIPTION:
XS GIS Cut Line= 4
      3574455.86     10242673.95      3574412.45     10242363.15
      3574023.56     10242278.08       3573821.4     10242447.41
#Sta/Elev= 30
  4563.3  269.17  4623.9  268.71  4646.4  268.99  4737.3   268.8  4757.5  269.21
  4797.9  268.43  4843.4  266.19  4868.5  265.74  4905.3  266.21  4928.6  265.42
  4959.4   266.3  4979.8  265.76  4990.1   263.5  4995.2  260.94  4997.9  260.44
  5003.3  261.19  5010.5  265.74  5020.8  267.01    5031  267.37    5091  267.45
  5096.2   267.8  5123.1  267.38  5194.8  268.33    5246   268.5  5335.5  269.51
  5349.8  270.57  5370.7  269.97  5407.1  270.03  5442.2     271  5538.9   276.4
#Mann= 3 , 0 , 0
  4563.3      .1       0  4979.8     .05       0  5010.5      .1       0
Bank Sta=4979.8,5010.5
XS Rating Curve= 0 ,0
Exp/Cntr=0.3,0.1

Chan Stop Cuts=-1
Use User Specified Reach Order=0
Composite Channel Slope=5