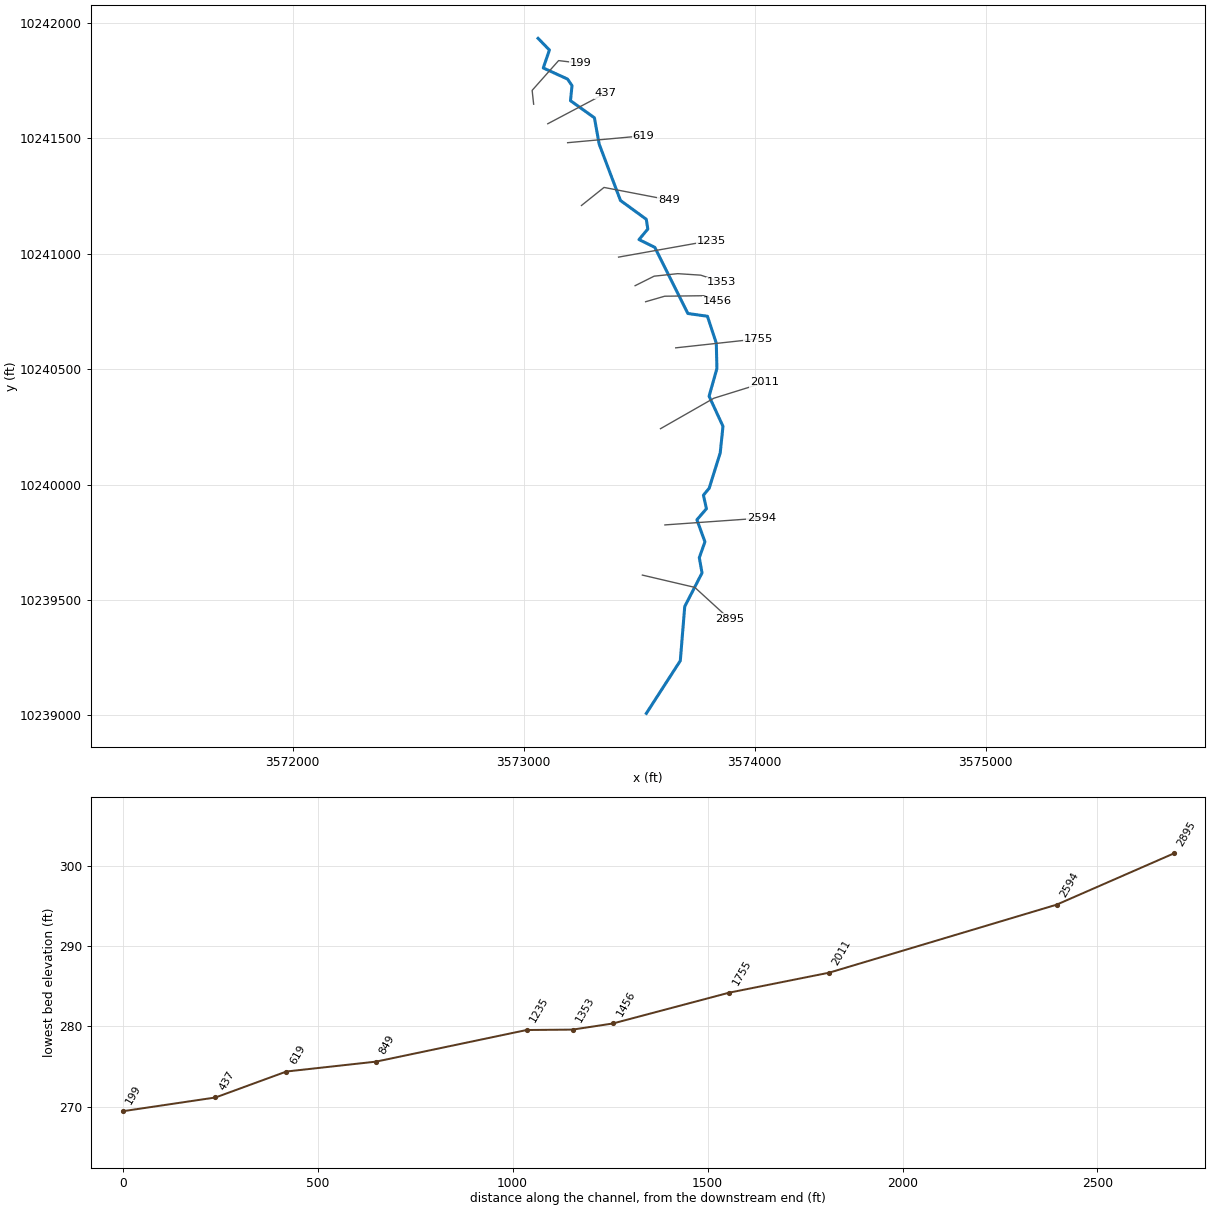
--- STEEPHOLLOWBRANCH.prj (project) ---

Proj Title=STEEP HOLLOW BRANCH TRIB 5
Current Plan=p01
Default Exp/Contr=0.3,0.1
English Units
Geom File=g01
Flow File=f01
Plan File=p01
Y Axis Title=Elevation
X Axis Title(PF)=Main Channel Distance
X Axis Title(XS)=Station
BEGIN DESCRIPTION:
UNT05246 IN WICK
END DESCRIPTION:
DSS Export Rating Curves= 0
DSS Export Rating Curve Sorted= 0
DSS Export Volume Flow Curves= 0
DXF Filename=UNT05246 IN WICK.
DXF OffsetX= 0
DXF OffsetY= 0
DXF ScaleX= 1
DXF ScaleY= 10

--- STEEPHOLLOWBRANCH.p01 (plan) ---

Plan Title=Multiple Run
Short Identifier=Multiple
Geom File=g01
Flow File=f01
Subcritical Flow
K Sum by GR= 0
Std Step Tol= 0.01
Critical Tol= 0.01
Num of Std Step Trials= 20
Max Error Tol= 0.3
Flow Tol Ratio= 0.001
Split Flow NTrial= 30
Split Flow Tol= 0.02
Split Flow Ratio= 0.02
Log Output Level= 0
Friction Slope Method= 1
Unsteady Friction Slope Method= 2
Unsteady Bridges Friction Slope Method= 1
Parabolic Critical Depth
Global Vel Dist=  1 , 1 , 1
Global Log Level= 0
CheckData=True
Encroach Param= -1, 0, 0, 0
BEGIN DESCRIPTION:
Multiple Run
END DESCRIPTION:

--- STEEPHOLLOWBRANCH.f01 (steady flow) ---

Flow Title=Multiple
Program Version=4.10
Number of Profiles= 7
Profile Names=10-year,25-year,50-year,1pct_min,100-year,1pct_plu,500-year
River Rch & RM=UNT05246 IN WICK,Reach-1         ,2895
     127     155     175     147     199     269     254
River Rch & RM=STEEPHOLLOWBRTR5,Reach-1         ,2895
     127     155     175     147     199     269     254
Boundary for River Rch & Prof#=STEEPHOLLOWBRTR5,Reach-1         , 1
Up Type= 0
Dn Type= 3
Dn Slope=0.005
Boundary for River Rch & Prof#=STEEPHOLLOWBRTR5,Reach-1         , 2
Up Type= 0
Dn Type= 3
Dn Slope=0.005
Boundary for River Rch & Prof#=STEEPHOLLOWBRTR5,Reach-1         , 3
Up Type= 0
Dn Type= 3
Dn Slope=0.005
Boundary for River Rch & Prof#=STEEPHOLLOWBRTR5,Reach-1         , 4
Up Type= 0
Dn Type= 3
Dn Slope=0.005
Boundary for River Rch & Prof#=STEEPHOLLOWBRTR5,Reach-1         , 5
Up Type= 0
Dn Type= 3
Dn Slope=0.005
Boundary for River Rch & Prof#=STEEPHOLLOWBRTR5,Reach-1         , 6
Up Type= 0
Dn Type= 3
Dn Slope=0.005
Boundary for River Rch & Prof#=STEEPHOLLOWBRTR5,Reach-1         , 7
Up Type= 0
Dn Type= 3
Dn Slope=0.005
DSS Import GetInterval= 0
DSS Import GetPeak= 0
DSS Import FillOption= 0

--- STEEPHOLLOWBRANCH.g01 (geometry) ---

Geom Title=Existing Conditions
Program Version=4.10

River Reach=STEEPHOLLOWBRTR5,Reach-1
Reach XY= 30
      3573530.85     10239009.16      3573677.84     10239237.02
      3573697.03     10239471.77      3573771.93     10239617.15
      3573760.12     10239683.12      3573784.49     10239751.83
      3573749.76     10239847.32        3573791.     10239895.06
      3573777.98     10239953.65      3573802.93     10239984.03
      3573850.68     10240137.03      3573862.61     10240252.05
      3573802.49     10240382.22      3573836.34     10240502.01
      3573833.74     10240611.39      3573795.34     10240728.39
       3573710.7     10240740.33      3573567.47     10241026.79
      3573499.11     10241060.42      3573537.09       10241106.
      3573530.58     10241148.31      3573418.82     10241229.69
      3573326.59     10241473.83      3573305.97     10241587.77
      3573202.44     10241661.71      3573209.02     10241727.01
      3573189.53     10241755.42      3573084.53     10241803.34
      3573111.26     10241881.01      3573062.11     10241931.64

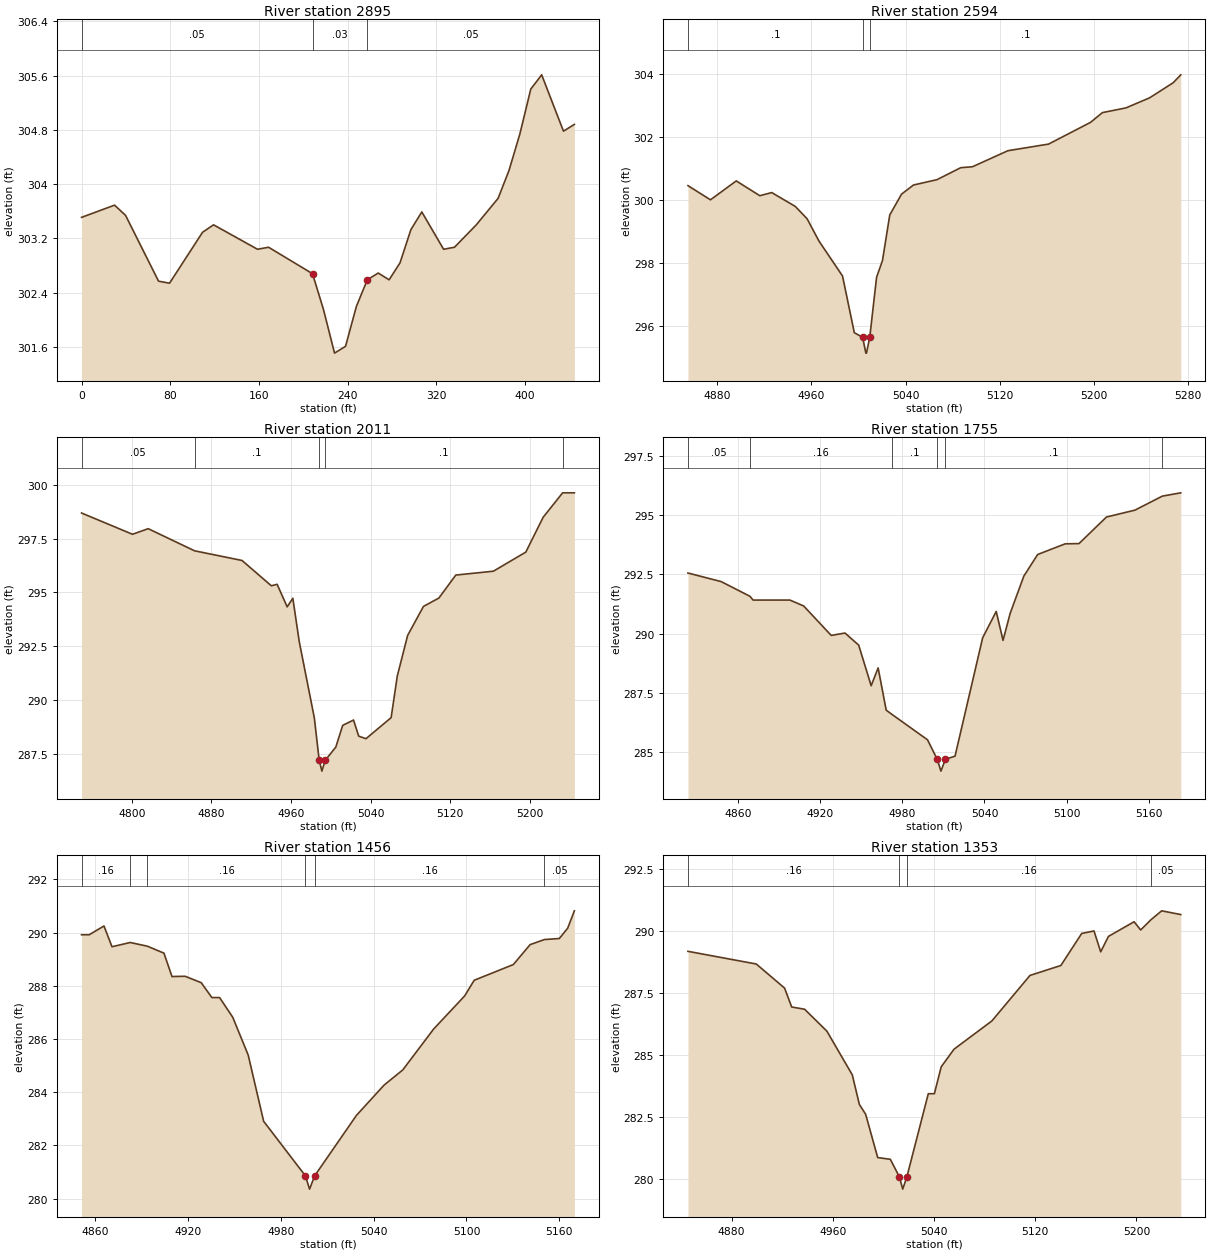
Type RM Length L Ch R = 1 ,2895    ,301,301,301
XS GIS Cut Line= 3
    3573513.7104    10239607.834     3573740.483    10239554.665
     3573890.223    10239417.947
#Sta/Elev= 30
       0  303.51   29.78  303.69    39.7  303.54   69.48  302.57    79.4  302.54
  109.18  303.29  119.11   303.4  158.81  303.04  168.74  303.07  208.44  302.68
  218.36  302.15  228.29  301.51  238.21  301.61  248.05   302.2  257.88  302.59
  267.72  302.69  277.55  302.59  287.38  302.84  297.22  303.33  307.05  303.59
  326.72  303.04  336.55  303.07  356.22   303.4  375.89  303.79  385.72   304.2
  395.55  304.74  405.39   305.4  415.22  305.61  434.89  304.78  444.72  304.88
#Mann= 3 , 0 , 0
       0     .05       0  208.44     .03       0  257.88     .05       0
Bank Sta=208.44,257.88
XS Rating Curve= 0 ,0
Exp/Cntr=0.3,0.1

Type RM Length L Ch R = 1 ,2594    ,583,583,583
BEGIN DESCRIPTION:
UNT05246 IN WICK 5.0
END DESCRIPTION:
XS GIS Cut Line= 2
      3573611.22     10239825.07      3574028.48      10239854.6
#Sta/Elev= 30
  4855.3  300.45  4874.4     300  4896.3   300.6  4916.3  300.13  4926.4  300.23
  4946.4  299.79  4956.4   299.4  4966.5  298.69  4986.5  297.58  4996.5  295.78
  5003.6  295.63  5006.3  295.13  5006.8  295.13  5009.6  295.63  5015.4  297.54
  5020.4  298.07  5026.6  299.52  5036.6  300.18  5046.7  300.47  5066.7  300.64
  5086.8  301.02  5096.8  301.05  5126.9  301.56  5161.4  301.77    5197  302.46
  5207.1  302.77  5227.1  302.92  5247.2  303.24  5267.2  303.72  5273.6  303.97
#Mann= 3 ,-1 , 0
  4855.3      .1       0  5003.6     .07       0  5009.6      .1       0
Bank Sta=5003.6,5009.6
XS Rating Curve= 0 ,0
Exp/Cntr=0.3,0.1

Type RM Length L Ch R = 1 ,2011    ,256,256,256
BEGIN DESCRIPTION:
UNT05246 IN WICK 4.0
END DESCRIPTION:
XS GIS Cut Line= 3
      3573592.08     10240241.63      3573822.95     10240373.48
      3574042.12     10240441.65
#Sta/Elev= 30
  4749.5   298.7  4800.7  297.71  4816.5  297.97  4863.1  296.94  4910.8  296.49
  4940.3  295.31  4946.1  295.38  4956.2  294.33  4961.9  294.73  4968.3  292.72
  4983.5  289.16  4988.4  287.18  4991.1  286.68  4994.4  287.18  5005.1   287.8
    5012  288.81  5022.9  289.06  5028.1  288.31  5035.4  288.19  5060.7  289.17
  5066.9  291.11  5077.3     293  5093.2  294.35  5108.7  294.74  5125.7  295.81
  5163.5  295.99  5196.1  296.88  5213.5   298.5  5233.1  299.64  5244.9  299.64
#Mann= 5 ,-1 , 0
  4749.5     .05       0  4863.1      .1       0  4988.4     .07       0
  4994.4      .1       0  5233.1     .05       0
Bank Sta=4988.4,4994.4
XS Rating Curve= 0 ,0
Exp/Cntr=0.3,0.1

Type RM Length L Ch R = 1 ,1755    ,299,299,299
BEGIN DESCRIPTION:
UNT05246 IN WICK 3.0
END DESCRIPTION:
XS GIS Cut Line= 2
      3573658.02     10240591.68       3574016.1     10240630.74
#Sta/Elev= 30
  4823.3  292.55  4847.5  292.19  4868.6  291.57  4870.9  291.41  4897.8  291.41
  4907.9  291.16    4928  289.92  4938.1  290.02  4948.1  289.51  4957.2   287.8
  4962.3  288.55  4968.2  286.77  4972.2   286.6  4998.4  285.52  5005.5   284.7
  5008.2   284.2  5011.5   284.7  5018.5  284.83  5038.7  289.82  5048.6  290.93
  5053.6  289.71  5058.8  290.85  5068.8  292.42  5078.9  293.33    5099  293.78
  5109.1  293.79  5129.2  294.91    5150   295.2    5170  295.79  5183.5  295.93
#Mann= 6 ,-1 , 0
  4823.3     .05       0  4868.6     .16       0  4972.2      .1       0
  5005.5     .07       0  5011.5      .1       0    5170     .05       0
Bank Sta=5005.5,5011.5
XS Rating Curve= 0 ,0
Exp/Cntr=0.3,0.1

Type RM Length L Ch R = 1 ,1456    ,103,103,103
BEGIN DESCRIPTION:
Mapping XS f53e23ab
END DESCRIPTION:
XS GIS Cut Line= 4
      3573527.74     10240791.32      3573610.24      10240815.2
      3573779.51     10240817.37      3573838.73      10240794.1
#Sta/Elev= 30
    4851  289.92  4855.9  289.92  4865.5  290.25  4870.7  289.47  4882.5  289.63
  4893.6  289.49  4904.3  289.23  4909.5  288.35    4918  288.36  4928.4  288.12
  4935.3  287.56  4940.3  287.56  4948.8  286.82  4958.8   285.4  4968.8  282.91
  4995.8  280.86  4998.5  280.36  5001.8  280.86  5028.8  283.13  5046.7  284.27
  5058.8  284.84  5078.8  286.38  5098.8  287.62    5105  288.21  5130.3   288.8
  5141.2  289.55  5150.4  289.74  5160.1  289.78  5165.5  290.17  5169.8  290.82
#Mann= 6 ,-1 , 0
    4851     .16       0  4882.5     .05       0  4893.6     .16       0
  4995.8     .07       0  5001.8     .16       0  5150.4     .05       0
Bank Sta=4995.8,5001.8
XS Rating Curve= 0 ,0
Exp/Cntr=0.3,0.1

Type RM Length L Ch R = 1 ,1353    ,118,118,118
BEGIN DESCRIPTION:
Mapping XS 4df1f015
END DESCRIPTION:
XS GIS Cut Line= 5
      3573482.18     10240860.76      3573564.66       10240902.
      3573666.66     10240912.85      3573766.49     10240906.34
      3573856.39     10240876.37
#Sta/Elev= 30
  4845.5  289.17  4899.5  288.66  4921.9  287.69  4927.5  286.93  4937.7  286.84
  4955.3  285.96  4975.4   284.2    4981  283.01    4986  282.61  4995.5  280.87
  5005.5   280.8  5012.6   280.1  5015.3   279.6  5018.6   280.1  5035.5  283.44
  5040.3  283.44  5045.7  284.52  5055.8  285.23  5085.8  286.37  5115.9   288.2
  5140.3   288.6  5156.8  289.89  5166.5  289.99  5171.8  289.15  5177.9  289.77
  5198.2  290.36  5203.4  290.03  5211.5  290.44    5220   290.8  5235.1  290.65
#Mann= 4 ,-1 , 0
  4845.5     .16       0  5012.6     .07       0  5018.6     .16       0
  5211.5     .05       0
Bank Sta=5012.6,5018.6
XS Rating Curve= 0 ,0
Exp/Cntr=0.3,0.1

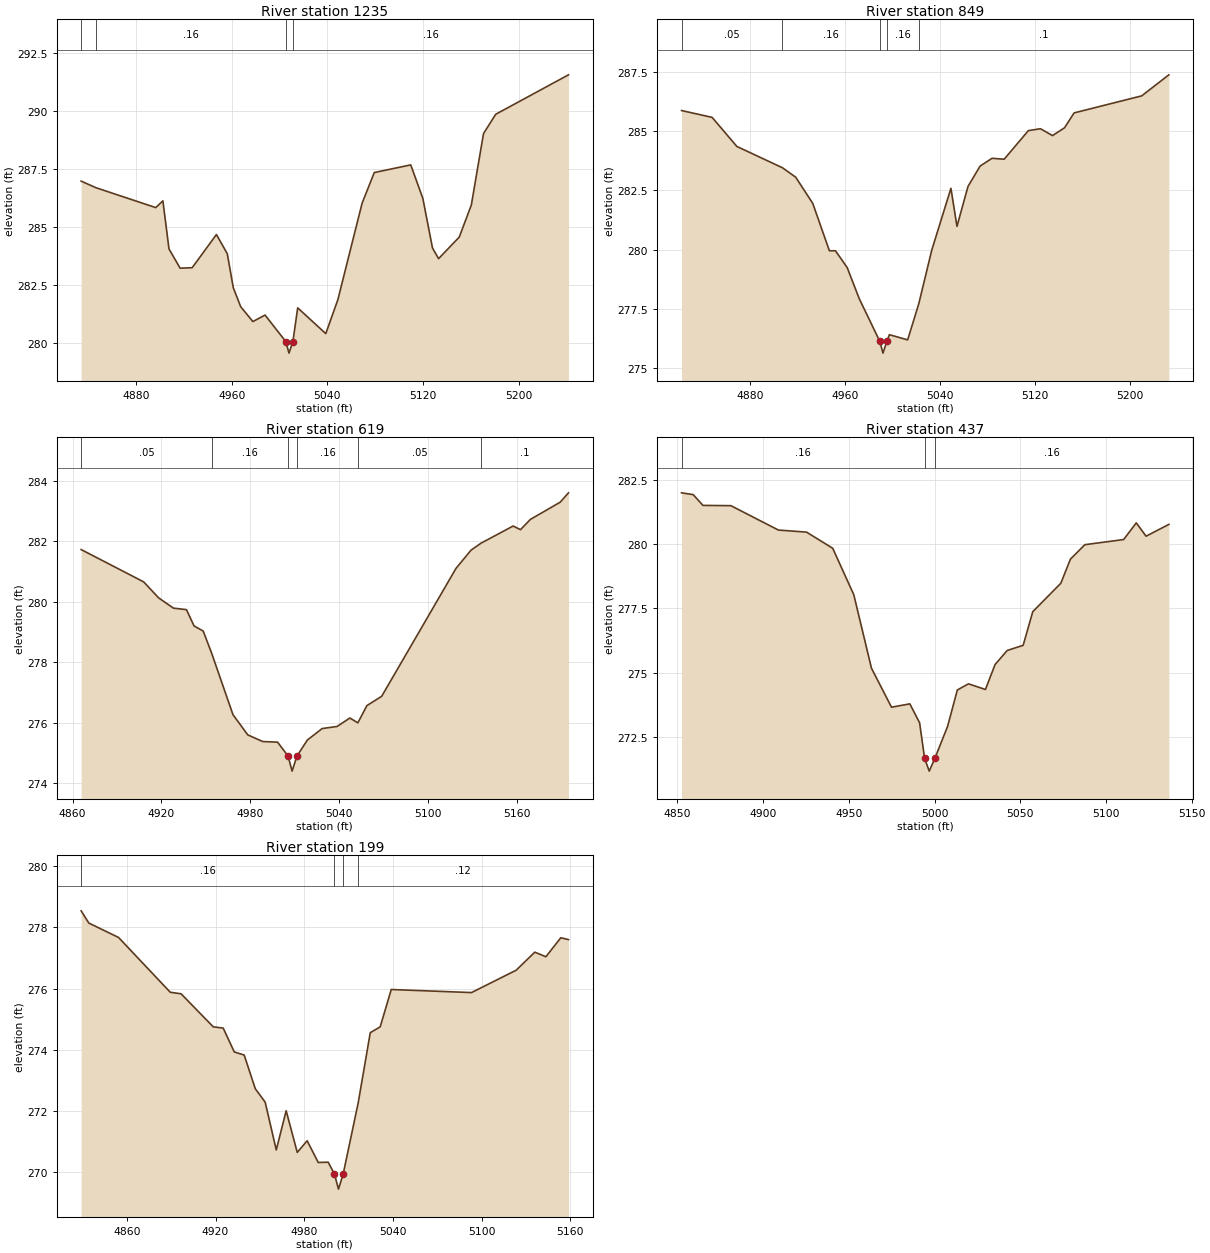
Type RM Length L Ch R = 1 ,1235    ,386,386,386
BEGIN DESCRIPTION:
Mapping XS 902e0fd6
END DESCRIPTION:
XS GIS Cut Line= 2
      3573410.63     10240984.48      3573812.09     10241056.09
#Sta/Elev= 30
    4834  286.96  4846.2  286.68  4896.4  285.82  4902.4  286.11  4907.5  284.04
  4916.8  283.21  4926.9  283.23  4947.2  284.66  4956.3  283.83  4961.3  282.37
  4967.5  281.55  4977.7  280.91  4987.9  281.19  5005.2  280.05  5007.9  279.55
  5011.2  280.05  5015.2   281.5  5038.7  280.39  5048.8  281.85  5069.1  286.01
  5079.3  287.33  5109.8  287.66  5119.9  286.22    5128  284.08  5133.1  283.62
  5150.4  284.55  5160.5  285.93  5170.7  289.01  5180.9  289.84  5241.8  291.54
#Mann= 4 ,-1 , 0
    4834     .05       0  4846.2     .16       0  5005.2     .07       0
  5011.2     .16       0
Bank Sta=5005.2,5011.2
XS Rating Curve= 0 ,0
Exp/Cntr=0.3,0.1

Type RM Length L Ch R = 1 ,849     ,230,230,230
BEGIN DESCRIPTION:
UNT05246 IN WICK 2.0
END DESCRIPTION:
XS GIS Cut Line= 3
      3573250.03     10241208.02      3573347.65     10241286.12
      3573628.49     10241232.11
#Sta/Elev= 30
  4822.1  285.88  4847.9  285.59  4868.8  284.36  4907.2  283.46  4918.4  283.06
  4932.8  281.95  4946.8  279.95  4951.9  279.95  4961.8  279.24    4972  277.92
  4989.3  276.12    4992  275.62  4995.3  276.12  4997.4   276.4  5012.8  276.18
  5022.2  277.71  5033.1  279.97  5049.3  282.59  5054.4  280.98  5063.7  282.67
  5073.9  283.53    5084  283.86  5094.2  283.82  5114.6  285.03  5124.8  285.11
    5135  284.82  5145.1  285.15  5153.2  285.78  5210.2   286.5  5233.1  287.39
#Mann= 5 ,-1 , 0
  4822.1     .05       0  4907.2     .16       0  4989.3     .07       0
  4995.3     .16       0  5022.2      .1       0
Bank Sta=4989.3,4995.3
XS Rating Curve= 0 ,0
Exp/Cntr=0.3,0.1

Type RM Length L Ch R = 1 ,619     ,182,182,182
BEGIN DESCRIPTION:
Mapping XS 08bc6af9
END DESCRIPTION:
XS GIS Cut Line= 2
      3573190.03     10241479.83      3573517.67     10241509.74
#Sta/Elev= 30
  4865.8  281.73    4908  280.66  4918.1  280.13  4928.1  279.79  4936.9  279.74
    4942   279.2  4948.2  279.03  4953.8  278.31  4968.3  276.26  4978.3  275.59
  4988.4  275.37  4998.4  275.35  5005.5  274.89  5008.2  274.39  5011.5  274.89
  5018.5  275.42  5028.5   275.8  5038.6  275.87  5047.2  276.15  5052.6  275.99
  5058.7  276.56  5068.7  276.87  5118.9  281.11    5129  281.71  5135.7  281.94
  5157.4  282.51  5162.4  282.39  5169.1  282.73  5189.2   283.3  5194.8  283.61
#Mann= 6 ,-1 , 0
  4865.8     .05       0  4953.8     .16       0  5005.5     .07       0
  5011.5     .16       0  5052.6     .05       0  5135.7      .1       0
Bank Sta=5005.5,5011.5
XS Rating Curve= 0 ,0
Exp/Cntr=0.3,0.1

Type RM Length L Ch R = 1 ,437     ,238,238,238
BEGIN DESCRIPTION:
Mapping XS d489dc56
END DESCRIPTION:
XS GIS Cut Line= 2
       3573104.1     10241561.86      3573355.46      10241694.7
#Sta/Elev= 30
  4852.4     282  4859.2  281.93  4864.9  281.51  4881.2   281.5  4908.9  280.55
  4925.3  280.47  4940.6  279.84  4952.9  278.03  4963.2  275.17  4974.9  273.65
  4985.6  273.78  4991.3  273.04  4994.2  271.66  4996.9  271.16  5000.2  271.66
  5007.6   272.9  5013.3  274.32  5019.8  274.56  5029.7  274.34  5035.3  275.31
  5042.4  275.86  5051.7  276.06  5057.3  277.37  5073.7  278.48  5079.3  279.42
  5087.7  279.98  5110.3  280.18  5117.7  280.83  5123.4  280.31  5136.7  280.77
#Mann= 3 ,-1 , 0
  4852.4     .16       0  4994.2     .07       0  5000.2     .16       0
Bank Sta=4994.2,5000.2
XS Rating Curve= 0 ,0
Exp/Cntr=0.3,0.1

Type RM Length L Ch R = 1 ,199     ,0,0,0
BEGIN DESCRIPTION:
UNT05246 IN WICK 1.0
END DESCRIPTION:
XS GIS Cut Line= 4
      3573042.92      10241646.5      3573036.41      10241706.4
        3573151.      10241835.3      3573247.26      10241823.6
#Sta/Elev= 30
  4829.1  278.54  4834.3  278.14  4854.4  277.67  4889.4  275.88  4896.7  275.83
  4918.5  274.75  4925.2  274.71  4932.7  273.93  4939.4  273.83  4946.9  272.73
  4953.6  272.29  4961.1  270.73  4967.8  272.01  4975.3  270.65    4982  271.03
  4989.5  270.32  4996.2  270.33  5000.4  269.95  5003.2  269.45  5006.4  269.95
  5016.5  272.26  5024.7  274.56  5031.4  274.75  5038.9  275.97  5093.2  275.87
  5123.4   276.6    5136  277.19  5143.5  277.04  5153.6  277.66  5158.8   277.6
#Mann= 4 ,-1 , 0
  4829.1     .16       0  5000.4     .07       0  5006.4     .16       0
  5016.5     .12       0
Bank Sta=5000.4,5006.4
XS Rating Curve= 0 ,0
Exp/Cntr=0.3,0.1

Chan Stop Cuts=-1
Use User Specified Reach Order=0
Composite Channel Slope=5