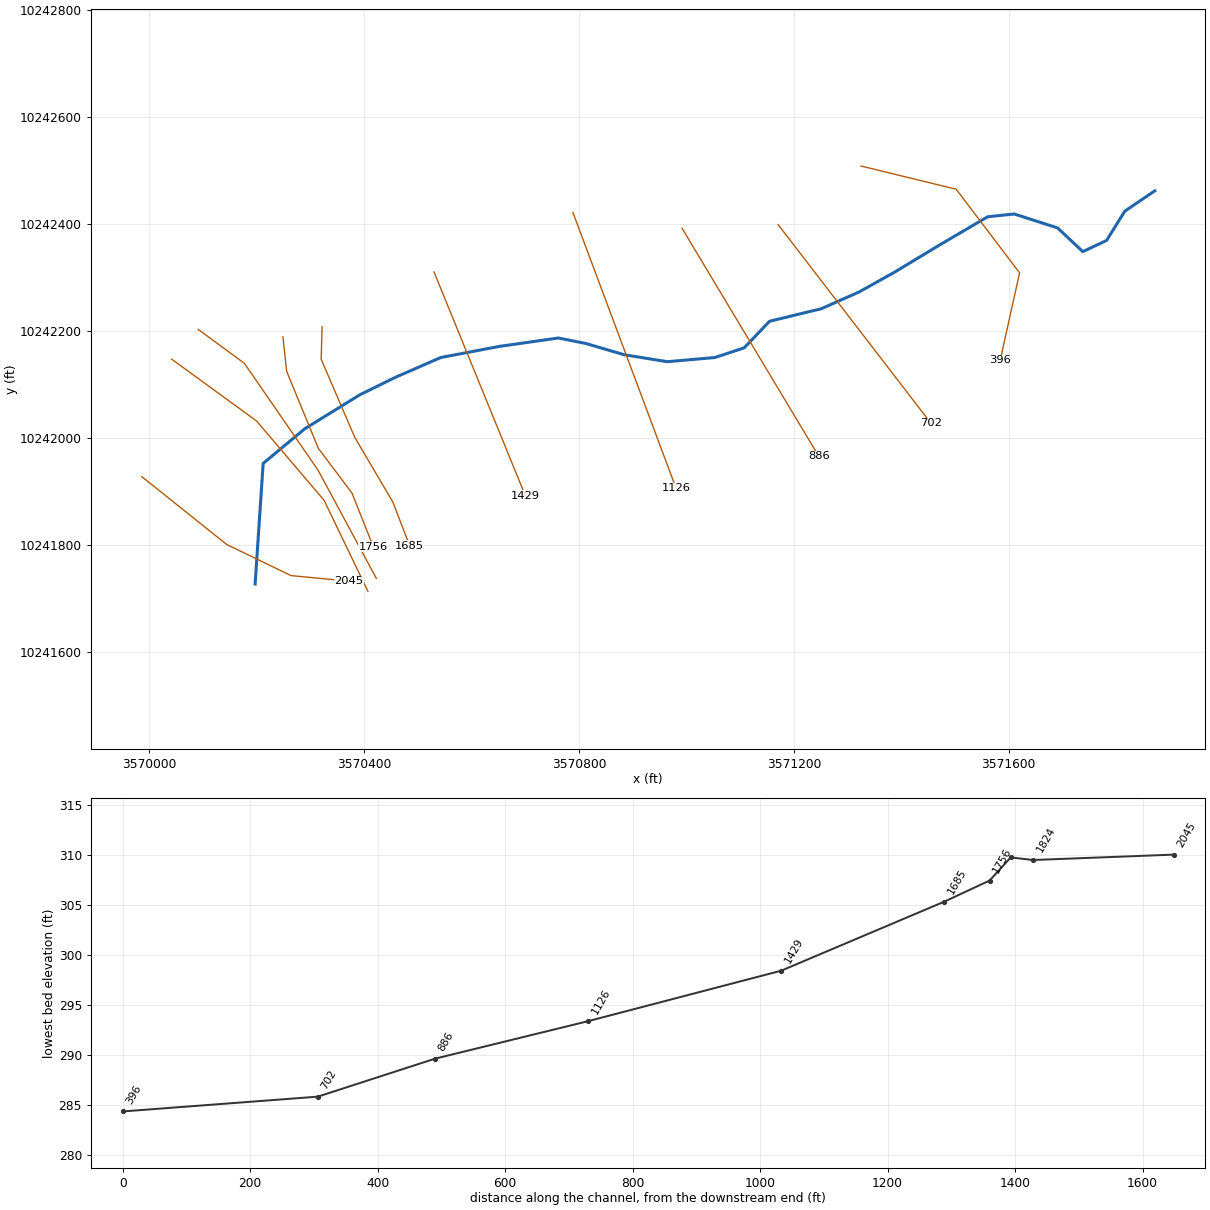
--- STEEPHOLLOWBRANCH.prj (project) ---

Proj Title=STEEP HOLLOW BRANCH TRIB 6 1
Current Plan=p01
Default Exp/Contr=0.3,0.1
English Units
Geom File=g01
Flow File=f01
Plan File=p01
Y Axis Title=Elevation
X Axis Title(PF)=Main Channel Distance
X Axis Title(XS)=Station
BEGIN DESCRIPTION:
UNT009 IN WICK
END DESCRIPTION:
DSS Export Rating Curves= 0
DSS Export Rating Curve Sorted= 0
DSS Export Volume Flow Curves= 0
DXF Filename=UNT009 IN WICK.
DXF OffsetX= 0
DXF OffsetY= 0
DXF ScaleX= 1
DXF ScaleY= 10

--- STEEPHOLLOWBRANCH.p01 (plan) ---

Plan Title=Multiple Run
Short Identifier=Multiple
Geom File=g01
Flow File=f01
Subcritical Flow
K Sum by GR= 0
Std Step Tol= 0.01
Critical Tol= 0.01
Num of Std Step Trials= 20
Max Error Tol= 0.3
Flow Tol Ratio= 0.001
Split Flow NTrial= 30
Split Flow Tol= 0.02
Split Flow Ratio= 0.02
Log Output Level= 0
Friction Slope Method= 1
Unsteady Friction Slope Method= 2
Unsteady Bridges Friction Slope Method= 1
Parabolic Critical Depth
Global Vel Dist=  1 , 1 , 1
Global Log Level= 0
CheckData=True
Encroach Param= -1, 0, 0, 0
BEGIN DESCRIPTION:
Multiple Run
END DESCRIPTION:

--- STEEPHOLLOWBRANCH.f01 (steady flow) ---

Flow Title=Multiple
Program Version=4.10
Number of Profiles= 7
Profile Names=10-year,25-year,50-year,1pct_min,100-year,1pct_plu,500-year
River Rch & RM=UNT009 IN WICK,Reach-1         ,2045
      72      83      92      75     101     136     121
River Rch & RM=TEEPHOLLOWBRTR61,Reach-1         ,2045
      72      83      92      75     101     136     121
Boundary for River Rch & Prof#=TEEPHOLLOWBRTR61,Reach-1         , 1
Up Type= 0
Dn Type= 3
Dn Slope=0.005
Boundary for River Rch & Prof#=TEEPHOLLOWBRTR61,Reach-1         , 2
Up Type= 0
Dn Type= 3
Dn Slope=0.005
Boundary for River Rch & Prof#=TEEPHOLLOWBRTR61,Reach-1         , 3
Up Type= 0
Dn Type= 3
Dn Slope=0.005
Boundary for River Rch & Prof#=TEEPHOLLOWBRTR61,Reach-1         , 4
Up Type= 0
Dn Type= 3
Dn Slope=0.005
Boundary for River Rch & Prof#=TEEPHOLLOWBRTR61,Reach-1         , 5
Up Type= 0
Dn Type= 3
Dn Slope=0.005
Boundary for River Rch & Prof#=TEEPHOLLOWBRTR61,Reach-1         , 6
Up Type= 0
Dn Type= 3
Dn Slope=0.005
Boundary for River Rch & Prof#=TEEPHOLLOWBRTR61,Reach-1         , 7
Up Type= 0
Dn Type= 3
Dn Slope=0.005
DSS Import GetInterval= 0
DSS Import GetPeak= 0
DSS Import FillOption= 0

--- STEEPHOLLOWBRANCH.g01 (geometry) ---

Geom Title=Existing Conditions
Program Version=4.10

River Reach=TEEPHOLLOWBRTR61,Reach-1
Reach XY= 25
      3570197.03     10241726.38      3570211.99      10241951.8
      3570289.58      10242016.6      3570392.07     10242080.05
      3570459.39     10242113.26      3570542.72     10242149.71
      3570652.09     10242170.55      3570761.47     10242186.17
      3570813.55     10242175.76      3570883.87     10242154.92
      3570964.59      10242141.9      3571053.14     10242149.71
      3571107.82     10242167.94       3571154.7     10242217.42
      3571251.05     10242240.86      3571321.37     10242272.11
      3571386.47     10242308.57      3571472.41     10242360.65
      3571560.95     10242412.74      3571610.43     10242417.94
      3571691.16      10242391.9      3571738.03     10242347.63
       3571782.3     10242368.46      3571816.16     10242423.15
      3571872.03     10242461.16

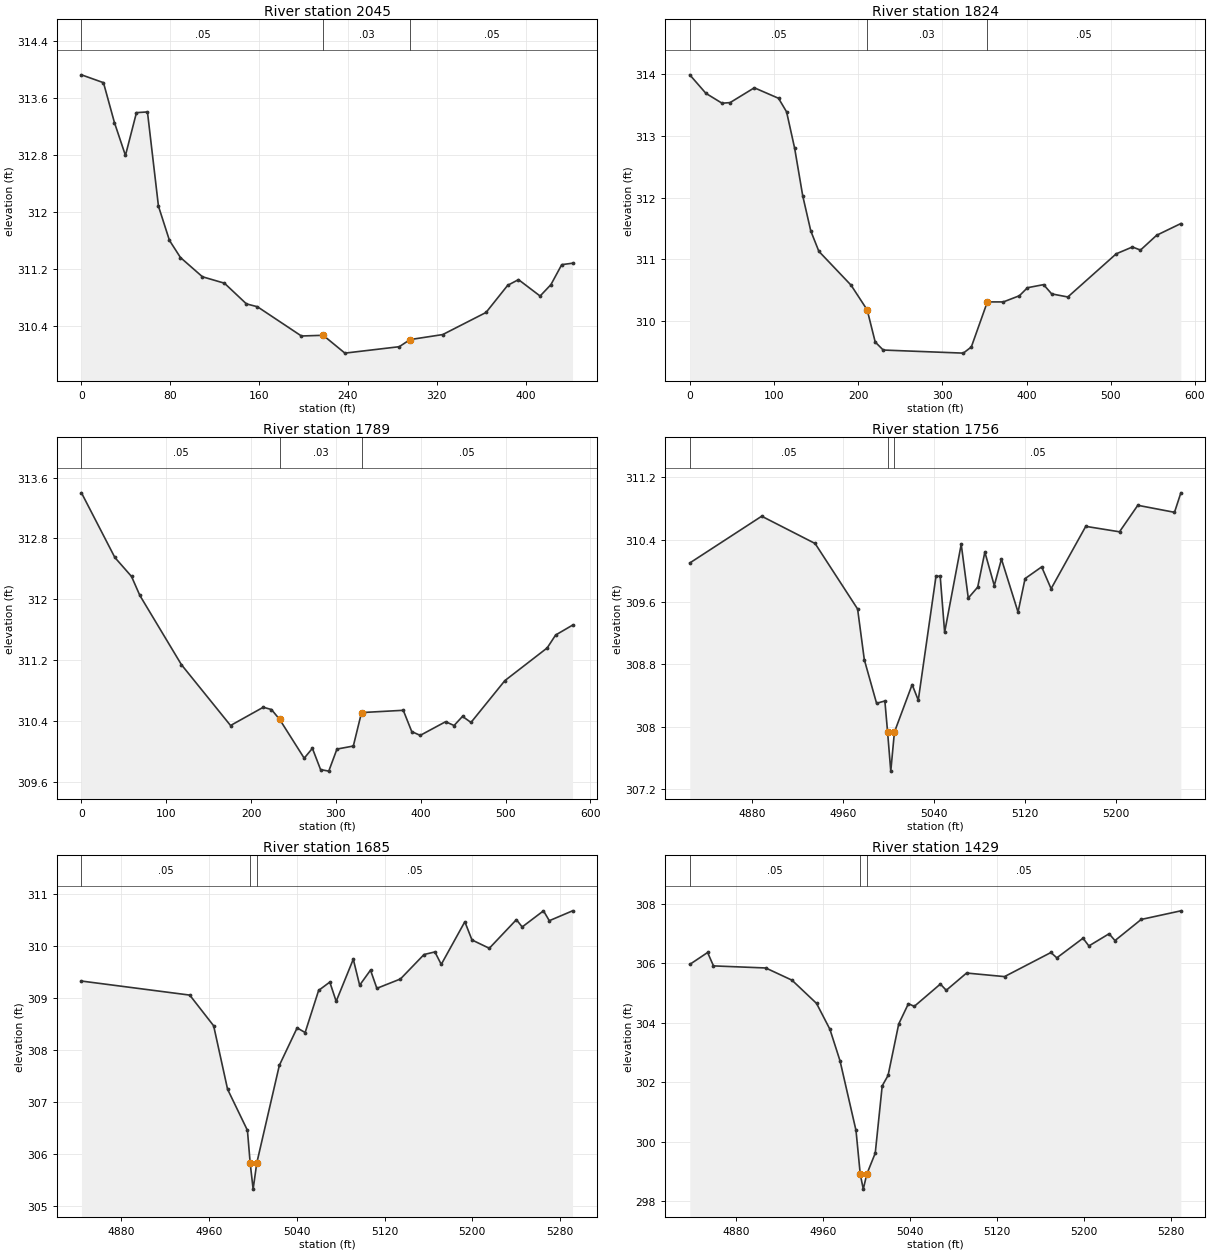
Type RM Length L Ch R = 1 ,2045    ,221,221,221
XS GIS Cut Line= 4
     3569986.073    10241927.047     3570144.059    10241800.311
      3570263.85    10241742.151     3570371.489    10241731.735
#Sta/Elev= 26
       0  313.92   19.81  313.81   29.71  313.25   39.61  312.79   49.52  313.39
   59.42   313.4   69.32  312.08   79.23   311.6   89.13  311.36  108.94  311.09
  128.75     311  148.55  310.71  158.46  310.67  198.07  310.26  217.65  310.27
  237.23  310.02  286.17  310.11  295.96  310.21  325.33  310.28  364.33  310.59
  383.81  310.97  393.55  311.05  413.02  310.82  422.76  310.98   432.5  311.26
  442.24  311.28
#Mann= 3 , 0 , 0
       0     .05       0  217.65     .03       0  295.96     .05       0
Bank Sta=217.65,295.96
XS Rating Curve= 0 ,0
Exp/Cntr=0.3,0.1

Type RM Length L Ch R = 1 ,1824    ,35,35,35
XS GIS Cut Line= 4
     3570041.628    10242146.665     3570199.614    10242031.214
     3570325.482    10241882.776      3570407.08    10241712.637
#Sta/Elev= 29
       0  313.99   19.16  313.69   38.33  313.53   47.91  313.54   76.66  313.78
  105.41  313.61  114.99  313.39  124.57   312.8  134.15  312.03  143.73  311.46
  153.32  311.13  191.65  310.58  210.74  310.18  220.26  309.66  229.77  309.53
  324.91  309.48  334.43  309.58  353.46  310.31  372.49  310.31  391.51  310.41
   401.1  310.54  420.28  310.59  429.87  310.44  449.05  310.39  506.59  311.09
  525.77   311.2  535.36  311.15  554.54  311.39  583.31  311.58
#Mann= 3 , 0 , 0
       0     .05       0  210.74     .03       0  353.46     .05       0
Bank Sta=210.74,353.46
XS Rating Curve= 0 ,0
Exp/Cntr=0.3,0.1

Type RM Length L Ch R = 1 ,1789    ,33,33,33
XS GIS Cut Line= 4
     3570091.107    10242202.221     3570177.045    10242138.853
     3570314.198      10241939.2     3570422.705    10241736.943
#Sta/Elev= 27
       0   313.4   39.34  312.55   59.01   312.3   68.84  312.05  117.83  311.14
  175.73  310.34  214.32  310.58  223.97  310.55  233.62  310.42  262.57  309.91
  272.22  310.04  281.87  309.76  291.52  309.74  301.17  310.03  320.47  310.07
  330.12  310.51  379.35  310.54  389.33  310.26  399.31  310.21  429.24  310.39
  439.22  310.34  449.19  310.46  459.17  310.38  499.08  310.93  548.97  311.36
  558.94  311.53   578.9  311.66
#Mann= 3 , 0 , 0
       0     .05       0  233.62     .03       0  330.12     .05       0
Bank Sta=233.62,330.12
XS Rating Curve= 0 ,0
Exp/Cntr=0.3,0.1

Type RM Length L Ch R = 1 ,1756    ,71,71,71
BEGIN DESCRIPTION:
Mapping XS 375c58f3
END DESCRIPTION:
XS GIS Cut Line= 5
      3570248.82     10242188.18      3570255.76     10242123.91
      3570314.79     10241979.82      3570377.29     10241896.48
      3570416.98     10241796.39
#Sta/Elev= 30
  4824.8   310.1  4888.1   310.7  4935.1  310.35  4972.5  309.51  4978.4  308.86
  4989.2   308.3  4996.5  308.33  4998.9  307.93  5001.7  307.43  5004.9  307.93
  5020.5  308.54  5025.9  308.34  5041.5  309.93  5045.2  309.93  5049.1  309.21
  5063.7  310.34  5069.9  309.65  5078.2  309.79  5084.5  310.24  5092.8  309.81
  5099.1  310.15  5113.7  309.47  5119.9   309.9  5134.5  310.05  5142.8  309.77
  5173.3  310.57    5203   310.5  5219.1  310.84  5251.4  310.75    5257     311
#Mann= 3 ,-1 , 0
  4824.8     .05       0  4998.9     .03       0  5004.9     .05       0
Bank Sta=4998.9,5004.9
XS Rating Curve= 0 ,0
Exp/Cntr=0.3,0.1

Type RM Length L Ch R = 1 ,1685    ,256,256,256
BEGIN DESCRIPTION:
Mapping XS f20eb90b
END DESCRIPTION:
XS GIS Cut Line= 5
      3570321.74     10242207.28        3570320.     10242146.48
       3570382.5     10242000.65      3570453.68     10241879.12
      3570484.93     10241797.52
#Sta/Elev= 30
  4843.7  309.32  4942.4  309.05  4964.2  308.46  4976.9  307.24    4995  306.45
  4997.5  305.82  5000.2  305.32  5003.5  305.82  5024.1   307.7  5040.3  308.42
  5047.6  308.33  5059.9  309.14  5070.1   309.3  5075.9  308.93  5091.5  309.74
  5097.3  309.24  5107.2  309.53    5113  309.18  5134.5  309.36    5156  309.83
  5165.9  309.88  5171.7  309.64  5193.2  310.46  5199.7  310.11  5215.5  309.95
  5240.2   310.5  5245.5  310.36  5264.9  310.67  5270.2  310.48  5291.4  310.67
#Mann= 3 ,-1 , 0
  4843.7     .05       0  4997.5     .03       0  5003.5     .05       0
Bank Sta=4997.5,5003.5
XS Rating Curve= 0 ,0
Exp/Cntr=0.3,0.1

Type RM Length L Ch R = 1 ,1429    ,303,303,303
BEGIN DESCRIPTION:
Mapping XS 035e11c8
END DESCRIPTION:
XS GIS Cut Line= 2
      3570530.06     10242309.69      3570700.21     10241891.26
#Sta/Elev= 30
  4837.3  305.96  4853.7  306.36  4859.1  305.91  4907.2  305.84  4931.3  305.43
  4953.9  304.65  4966.2  303.78  4975.5  302.72  4990.2  300.38  4994.1  298.91
  4996.9  298.41  5000.1  298.91  5007.9  299.62  5014.3  301.88  5019.7  302.23
  5029.5  303.96  5038.4  304.64  5043.8  304.55  5067.8   305.3  5073.2  305.09
  5091.9  305.67  5126.8  305.55  5169.5  306.36  5174.9  306.18    5199  306.84
  5204.4  306.58    5223  306.99  5228.4  306.76  5252.5  307.47    5289  307.76
#Mann= 3 ,-1 , 0
  4837.3     .05       0  4994.1     .03       0  5000.1     .05       0
Bank Sta=4994.1,5000.1
XS Rating Curve= 0 ,0
Exp/Cntr=0.3,0.1

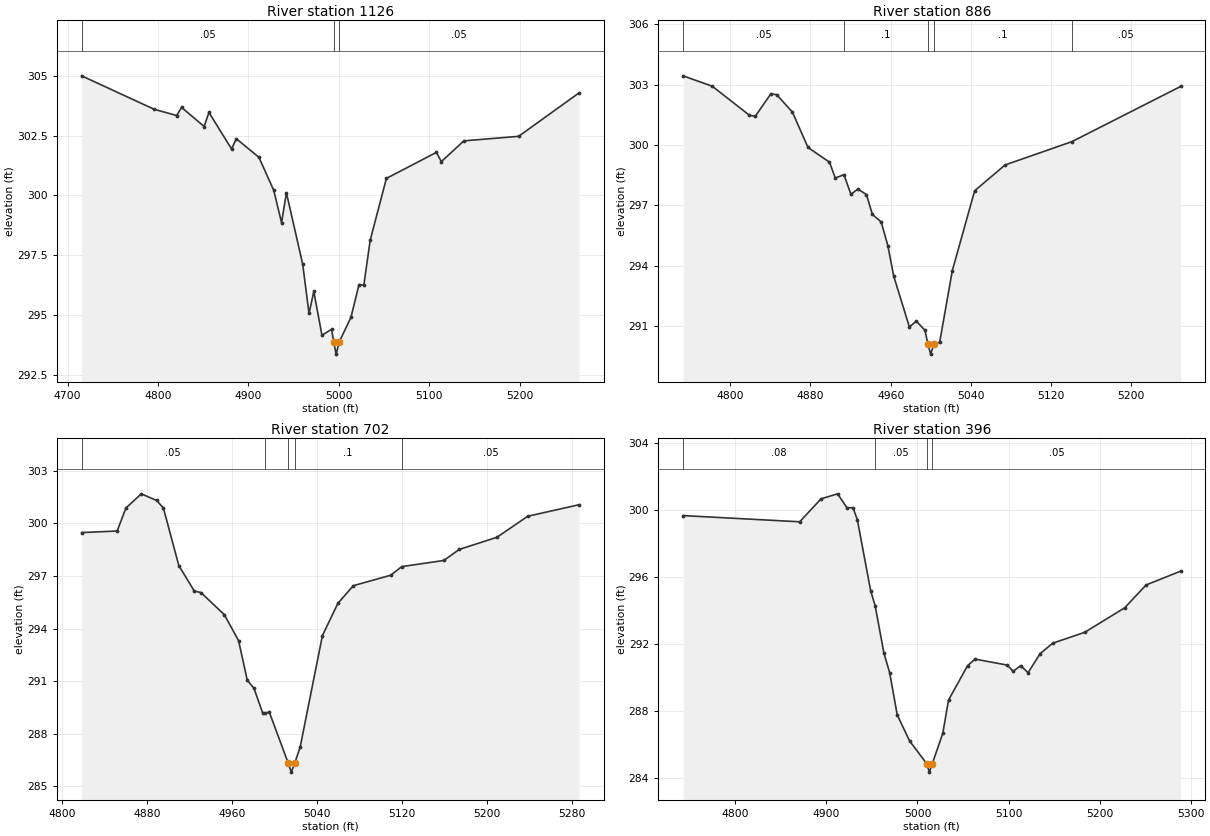
Type RM Length L Ch R = 1 ,1126    ,240,240,240
BEGIN DESCRIPTION:
UNT009 IN WICK 2.0
END DESCRIPTION:
XS GIS Cut Line= 2
      3570788.76     10242420.76      3570980.84     10241905.08
#Sta/Elev= 30
  4715.6     305  4795.8   303.6  4820.7  303.34  4826.1  303.68  4851.1  302.88
  4856.4  303.47  4881.4  301.94  4886.7  302.37  4911.7  301.59  4928.1  300.21
  4936.7  298.86  4942.1  300.11  4960.1  297.12  4967.1  295.06  4972.4  295.98
  4981.4  294.15  4992.1   294.4  4994.4  293.86  4997.1  293.36  5000.4  293.86
  5013.5   294.9  5022.4  296.27  5027.7  296.24  5034.8  298.13  5052.7  300.71
  5108.1   301.8  5113.4  301.41  5138.4  302.28    5199  302.47  5265.9  304.29
#Mann= 3 ,-1 , 0
  4715.6     .05       0  4994.4     .03       0  5000.4     .05       0
Bank Sta=4994.4,5000.4
XS Rating Curve= 0 ,0
Exp/Cntr=0.3,0.1

Type RM Length L Ch R = 1 ,886     ,184,184,184
BEGIN DESCRIPTION:
Mapping XS ae90d623
END DESCRIPTION:
XS GIS Cut Line= 2
      3570991.86      10242391.3      3571246.34     10241965.44
#Sta/Elev= 30
    4753  303.44  4782.2  302.92  4819.2  301.48    4825  301.43  4840.6  302.55
  4846.4   302.5    4862  301.64  4877.6  299.88    4899  299.15  4904.8  298.36
  4913.4  298.53  4920.4  297.55  4927.3  297.81  4935.9  297.54  4941.8  296.55
  4950.6  296.18  4957.3  294.98  4963.1  293.48  4978.7  290.96  4985.6  291.25
  4994.3  290.79  4997.1  290.11  4999.9  289.61  5003.1  290.11  5008.9   290.2
  5021.5  293.76  5043.8  297.73  5074.1  299.01  5140.8  300.17  5249.1  302.91
#Mann= 5 ,-1 , 0
    4753     .05       0  4913.4      .1       0  4997.1     .07       0
  5003.1      .1       0  5140.8     .05       0
Bank Sta=4997.1,5003.1
XS Rating Curve= 0 ,0
Exp/Cntr=0.3,0.1

Type RM Length L Ch R = 1 ,702     ,306,306,306
BEGIN DESCRIPTION:
Mapping XS 32525126
END DESCRIPTION:
XS GIS Cut Line= 2
      3571170.72     10242398.18       3571455.4     10242026.72
#Sta/Elev= 30
  4818.6  299.47    4852  299.56  4860.2  300.87  4874.7  301.68  4889.2   301.3
  4895.5  300.87    4910  297.59  4924.5  296.14  4930.8  296.05  4952.8  294.79
  4966.2  293.31  4974.4  291.05  4980.7  290.59  4988.9  289.18  4990.8  289.19
  4995.2  289.22    5013  286.31  5015.8  285.81    5019  286.31  5024.2  287.25
  5045.1   293.6  5059.6  295.43  5074.1  296.44  5109.4  297.04  5119.7  297.53
  5159.3  297.88  5173.8  298.51  5209.2   299.2  5238.2   300.4  5286.6  301.06
#Mann= 5 ,-1 , 0
  4818.6     .05       0  4990.8      .1       0    5013     .07       0
    5019      .1       0  5119.7     .05       0
Bank Sta=5013,5019
XS Rating Curve= 0 ,0
Exp/Cntr=0.3,0.1

Type RM Length L Ch R = 1 ,396     ,0,0,0
BEGIN DESCRIPTION:
UNT009 IN WICK 1.0
END DESCRIPTION:
XS GIS Cut Line= 4
      3571325.22     10242507.59      3571502.29     10242464.19
      3571620.35     10242307.94      3571584.29     10242144.83
#Sta/Elev= 30
  4743.1  299.65  4870.9  299.28  4894.3  300.65  4912.4  300.95  4922.7  300.12
  4929.4  300.12  4934.1   299.4  4948.7  295.16  4953.6  294.27  4963.3  291.42
  4969.5  290.27  4977.8  287.75  4991.3   286.2  5010.2  284.83    5013  284.33
  5016.2  284.83  5027.8  286.66    5034  288.63  5054.9  290.69  5063.2  291.08
  5098.5  290.72  5104.8  290.35  5113.1  290.69  5121.2  290.27  5134.5  291.41
  5148.2  292.03  5183.3  292.68    5227  294.14  5250.6  295.51  5288.3  296.33
#Mann= 4 ,-1 , 0
  4743.1     .08       0  4953.6     .05       0  5010.2     .04       0
  5016.2     .05       0
Bank Sta=5010.2,5016.2
XS Rating Curve= 0 ,0
Exp/Cntr=0.3,0.1

Chan Stop Cuts=-1
Use User Specified Reach Order=0
Composite Channel Slope=5