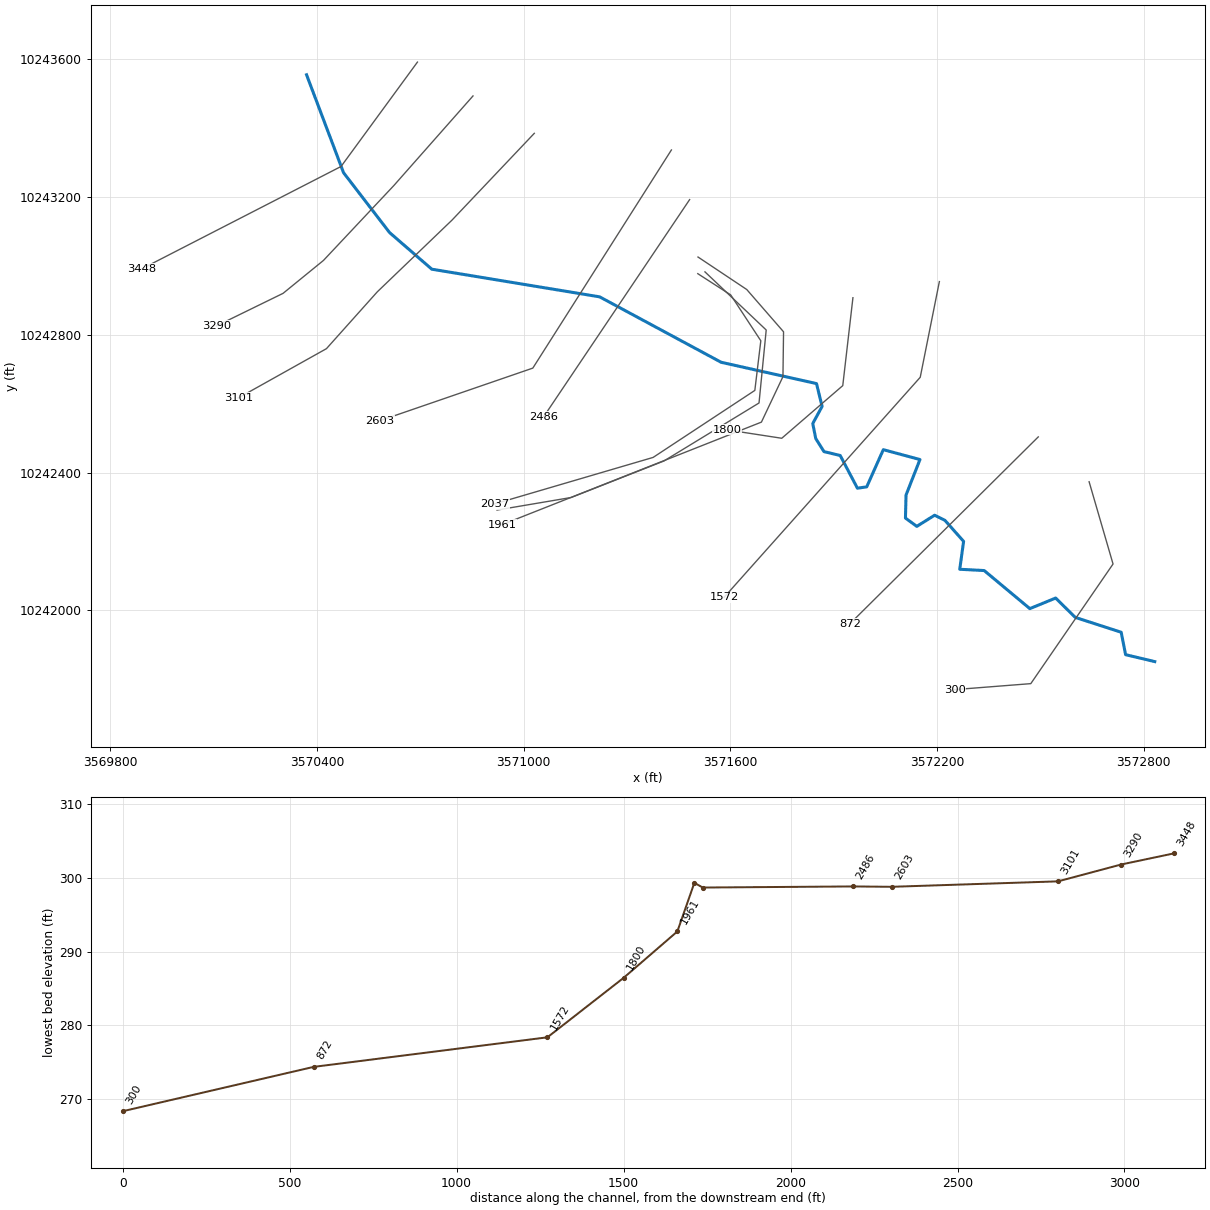
--- STEEPHOLLOWBRANCH.prj (project) ---

Proj Title=STEEP HOLLOW BRANCH TRIB 6
Current Plan=p01
Default Exp/Contr=0.3,0.1
English Units
Geom File=g01
Flow File=f01
Plan File=p01
Y Axis Title=Elevation
X Axis Title(PF)=Main Channel Distance
X Axis Title(XS)=Station
BEGIN DESCRIPTION:
UNT05245 IN WICK
END DESCRIPTION:
DSS Export Rating Curves= 0
DSS Export Rating Curve Sorted= 0
DSS Export Volume Flow Curves= 0
DXF Filename=UNT05245 IN WICK.
DXF OffsetX= 0
DXF OffsetY= 0
DXF ScaleX= 1
DXF ScaleY= 10

--- STEEPHOLLOWBRANCH.p01 (plan) ---

Plan Title=Multiple Run
Short Identifier=Multiple
Geom File=g01
Flow File=f01
Subcritical Flow
K Sum by GR= 0
Std Step Tol= 0.01
Critical Tol= 0.01
Num of Std Step Trials= 20
Max Error Tol= 0.3
Flow Tol Ratio= 0.001
Split Flow NTrial= 30
Split Flow Tol= 0.02
Split Flow Ratio= 0.02
Log Output Level= 0
Friction Slope Method= 1
Unsteady Friction Slope Method= 2
Unsteady Bridges Friction Slope Method= 1
Parabolic Critical Depth
Global Vel Dist=  1 , 1 , 1
Global Log Level= 0
CheckData=True
Encroach Param= -1, 0, 0, 0
BEGIN DESCRIPTION:
Multiple Run
END DESCRIPTION:

--- STEEPHOLLOWBRANCH.f01 (steady flow) ---

Flow Title=Multiple
Program Version=4.10
Number of Profiles= 7
Profile Names=10-year,25-year,50-year,1pct_min,100-year,1pct_plu,500-year
River Rch & RM=UNT05245 IN WICK,Reach-1         ,3448
     159     197     226     192     259     350     339
River Rch & RM=UNT05245 IN WICK,Reach-1         ,1572
     221     281     328     281     381     515     512
River Rch & RM=STEEPHOLLOWBRTR6,Reach-1         ,3448
     159     197     226     192     259     350     339
River Rch & RM=STEEPHOLLOWBRTR6,Reach-1         ,1572
     221     281     328     281     381     515     512
Boundary for River Rch & Prof#=STEEPHOLLOWBRTR6,Reach-1         , 1
Up Type= 0
Dn Type= 3
Dn Slope=0.005
Boundary for River Rch & Prof#=STEEPHOLLOWBRTR6,Reach-1         , 2
Up Type= 0
Dn Type= 3
Dn Slope=0.005
Boundary for River Rch & Prof#=STEEPHOLLOWBRTR6,Reach-1         , 3
Up Type= 0
Dn Type= 3
Dn Slope=0.005
Boundary for River Rch & Prof#=STEEPHOLLOWBRTR6,Reach-1         , 4
Up Type= 0
Dn Type= 3
Dn Slope=0.005
Boundary for River Rch & Prof#=STEEPHOLLOWBRTR6,Reach-1         , 5
Up Type= 0
Dn Type= 3
Dn Slope=0.005
Boundary for River Rch & Prof#=STEEPHOLLOWBRTR6,Reach-1         , 6
Up Type= 0
Dn Type= 3
Dn Slope=0.005
Boundary for River Rch & Prof#=STEEPHOLLOWBRTR6,Reach-1         , 7
Up Type= 0
Dn Type= 3
Dn Slope=0.005
DSS Import GetInterval= 0
DSS Import GetPeak= 0
DSS Import FillOption= 0

--- STEEPHOLLOWBRANCH.g01 (geometry) ---

Geom Title=Existing Conditions
Program Version=4.10

River Reach=STEEPHOLLOWBRTR6,Reach-1
Reach XY= 30
      3570370.27      10243554.8      3570477.69     10243270.51
      3570611.16      10243096.9      3570733.77     10242990.56
      3571220.97     10242910.27      3571573.61     10242720.38
      3571850.31     10242658.53      3571866.58     10242592.34
      3571839.45     10242542.43      3571848.14     10242499.02
      3571872.03     10242461.16      3571919.11     10242449.82
       3571969.1     10242354.93      3571996.08     10242358.86
      3572044.27     10242466.73       3572150.6     10242438.08
      3572110.18     10242335.03      3572108.51     10242268.18
      3572141.49     10242244.16       3572193.2     10242276.48
      3572223.18      10242261.6      3572277.25     10242200.61
      3572266.09     10242119.61      3572337.04      10242115.9
      3572469.52     10242005.36      3572544.45     10242036.11
      3572601.32     10241979.93      3572734.68      10241936.8
       3572747.4     10241871.76      3572832.11     10241851.64

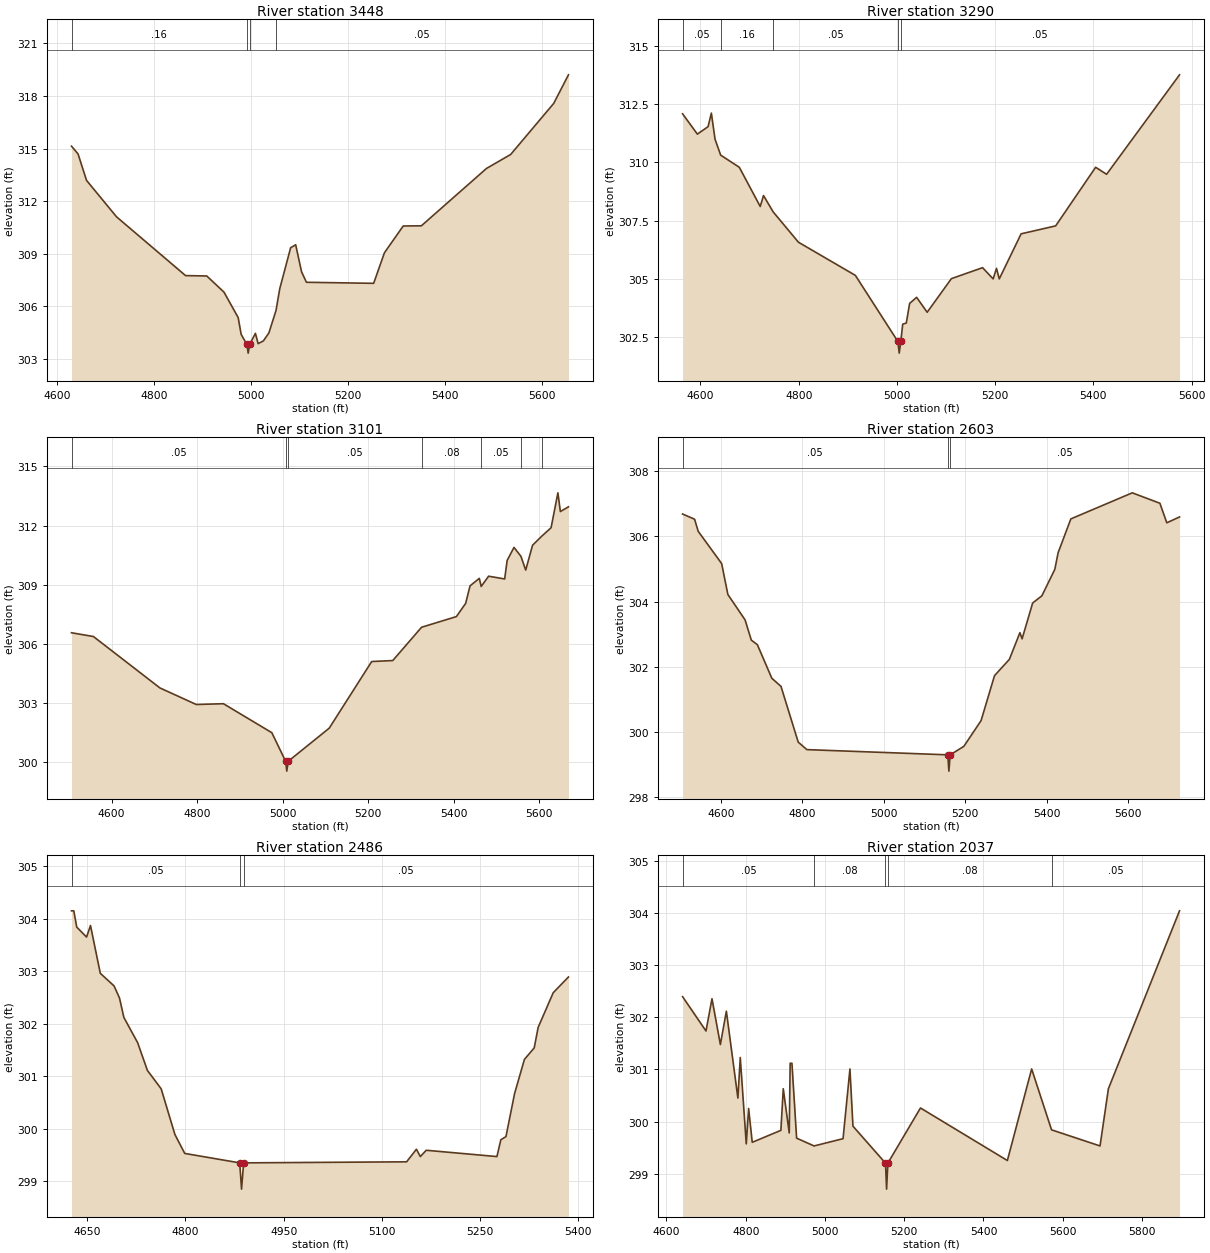
Type RM Length L Ch R = 1 ,3448    ,158,158,158
BEGIN DESCRIPTION:
UNT05245 IN WICK 6.0
END DESCRIPTION:
XS GIS Cut Line= 3
       3570692.1     10243591.64      3570470.41     10243288.69
      3569892.13     10242991.66
#Sta/Elev= 30
  4629.3  315.14  4642.8   314.7  4660.3  313.19  4722.3  311.11  4864.7  307.76
  4908.4  307.74  4943.9  306.82  4973.2  305.37  4979.4  304.41  4991.1  303.84
  4993.9  303.34  4997.1  303.84  5008.8  304.47  5014.4  303.88  5025.3  304.04
  5036.6  304.49  5051.3  305.77    5059  307.01  5081.5  309.35  5091.9  309.52
    5104  307.98  5114.1  307.38  5252.8  307.32    5275  309.06  5313.8  310.59
  5351.3   310.6  5485.6  313.87  5535.6  314.67  5624.4  317.58  5654.8  319.21
#Mann= 4 ,-1 , 0
  4629.3     .16       0  4991.1     .07       0  4997.1     .16       0
  5051.3     .05       0
Bank Sta=4991.1,4997.1
XS Rating Curve= 0 ,0
Exp/Cntr=0.3,0.1

Type RM Length L Ch R = 1 ,3290    ,189,189,189
BEGIN DESCRIPTION:
UNT05245 IN WICK 5.0
END DESCRIPTION:
XS GIS Cut Line= 5
      3570853.35     10243493.39      3570623.33     10243232.99
      3570419.34     10243015.98      3570302.15     10242920.49
      3570108.67     10242825.91
#Sta/Elev= 30
  4563.6  312.08  4593.7  311.21  4615.5  311.53  4622.2  312.11  4629.7  310.99
  4641.2  310.31  4679.1  309.79  4721.7  308.11  4728.4  308.58    4748  307.88
  4799.5  306.58  4915.4  305.16  5001.9  302.33  5004.7  301.83  5007.9  302.33
  5011.8  303.07  5019.1  303.12  5025.9  303.96  5040.1  304.22  5061.6  303.58
  5110.9  305.02  5174.4  305.49  5195.9  305.01  5202.8  305.46  5208.4  305.01
  5252.9  306.94  5323.2  307.28  5404.6  309.79  5426.9  309.49  5575.4  313.75
#Mann= 5 ,-1 , 0
  4563.6     .05       0  4641.2     .16       0    4748     .05       0
  5001.9     .04       0  5007.9     .05       0
Bank Sta=5001.9,5007.9
XS Rating Curve= 0 ,0
Exp/Cntr=0.3,0.1

Type RM Length L Ch R = 1 ,3101    ,498,498,498
BEGIN DESCRIPTION:
Mapping XS 23e48a8d
END DESCRIPTION:
XS GIS Cut Line= 5
       3571031.3     10243384.89       3570792.6     10243133.17
      3570575.59     10242924.83      3570428.02      10242759.9
       3570171.9     10242616.65
#Sta/Elev= 30
  4506.2  306.56  4557.4  306.37  4713.1  303.76  4798.1  302.92  4861.6  302.96
  4974.8  301.49  5007.1  300.04  5009.8  299.54  5013.1  300.04  5109.1  301.72
  5208.4   305.1  5257.7  305.15  5325.1  306.84  5406.5  307.38  5428.2  308.05
  5438.5  308.94  5460.2  309.32  5464.6  308.91  5481.9  309.43  5519.5  309.29
  5525.3  310.23  5541.3  310.89  5557.5  310.44  5568.7  309.74  5584.7     311
  5606.7  311.47  5628.1  311.89    5644  313.66  5649.8  312.71  5668.7  312.95
#Mann= 7 ,-1 , 0
  4506.2     .05       0  5007.1     .04       0  5013.1     .05       0
  5325.1     .08       0  5464.6     .05       0  5557.5     .08       0
  5606.7     .05       0
Bank Sta=5007.1,5013.1
XS Rating Curve= 0 ,0
Exp/Cntr=0.3,0.1

Type RM Length L Ch R = 1 ,2603    ,117,117,117
BEGIN DESCRIPTION:
UNT05245 IN WICK 4.0
END DESCRIPTION:
XS GIS Cut Line= 3
      3571429.17     10243336.58      3571026.98     10242703.48
      3570582.59      10242550.6
#Sta/Elev= 30
    4506  306.69  4535.5  306.53  4544.3  306.16  4601.9  305.17  4617.2  304.22
  4659.5  303.44  4674.7  302.82  4689.6  302.68  4725.1  301.65  4747.6   301.4
  4789.9  299.69  4811.1  299.46    5157   299.3  5159.8   298.8    5163   299.3
  5196.5  299.56  5238.8  300.35  5271.8  301.73  5308.3  302.23  5334.2  303.05
  5339.5  302.86  5365.5  303.96  5388.1  304.18  5419.8  304.99  5427.9   305.5
  5459.2  306.54    5610  307.34  5677.8  307.02  5694.8  306.42    5726   306.6
#Mann= 3 ,-1 , 0
    4506     .05       0    5157     .04       0    5163     .05       0
Bank Sta=5157,5163
XS Rating Curve= 0 ,0
Exp/Cntr=0.3,0.1

Type RM Length L Ch R = 1 ,2486    ,449,449,449
BEGIN DESCRIPTION:
Mapping XS 4296f2a1
END DESCRIPTION:
XS GIS Cut Line= 2
      3571482.09     10243192.51      3571058.51     10242562.34
#Sta/Elev= 30
  4625.9  304.15  4629.4  304.15  4633.9  303.84  4648.9  303.65  4654.9  303.87
  4669.9  302.96  4690.9  302.72  4699.2  302.49  4705.9  302.12  4726.9  301.64
  4741.9  301.11  4762.9  300.76  4783.9  299.89  4798.9  299.53  4882.9  299.35
  4885.7  298.85  4888.9  299.35  5137.9  299.37  5152.9  299.61  5158.9  299.47
  5167.9  299.59  5275.9  299.47  5281.9  299.79  5289.7  299.85  5302.9  300.67
  5317.9  301.32  5332.9  301.54  5338.9  301.93  5361.9  302.59  5385.2  302.89
#Mann= 3 ,-1 , 0
  4625.9     .05       0  4882.9     .04       0  4888.9     .05       0
Bank Sta=4882.9,4888.9
XS Rating Curve= 0 ,0
Exp/Cntr=0.3,0.1

Type RM Length L Ch R = 1 ,2037    ,25,25,25
BEGIN DESCRIPTION:
Mapping XS aad8868b
END DESCRIPTION:
XS GIS Cut Line= 6
      3571505.79     10242977.58      3571601.28     10242915.94
      3571688.71     10242782.82      3571671.35     10242638.73
      3571376.21     10242444.28      3570915.73     10242309.14
#Sta/Elev= 30
  4640.6   302.4  4699.7  301.74  4714.8  302.36    4736  301.48  4751.1  302.12
  4780.2  300.45  4786.2  301.23  4801.3  299.57  4807.3  300.25  4816.4   299.6
  4888.7  299.83  4894.7  300.63  4909.8  299.78  4912.1  301.12  4916.6  301.12
  4928.4  299.68  4972.4  299.53  5045.6  299.67    5063  301.01  5070.6  299.91
  5152.7   299.2  5155.5   298.7  5158.7   299.2    5241  300.26  5460.3  299.25
  5521.6  301.01  5571.8  299.84  5694.2  299.53  5715.3  300.63  5894.8  304.05
#Mann= 5 ,-1 , 0
  4640.6     .05       0  4972.4     .08       0  5152.7     .07       0
  5158.7     .08       0  5571.8     .05       0
Bank Sta=5152.7,5158.7
XS Rating Curve= 0 ,0
Exp/Cntr=0.3,0.1

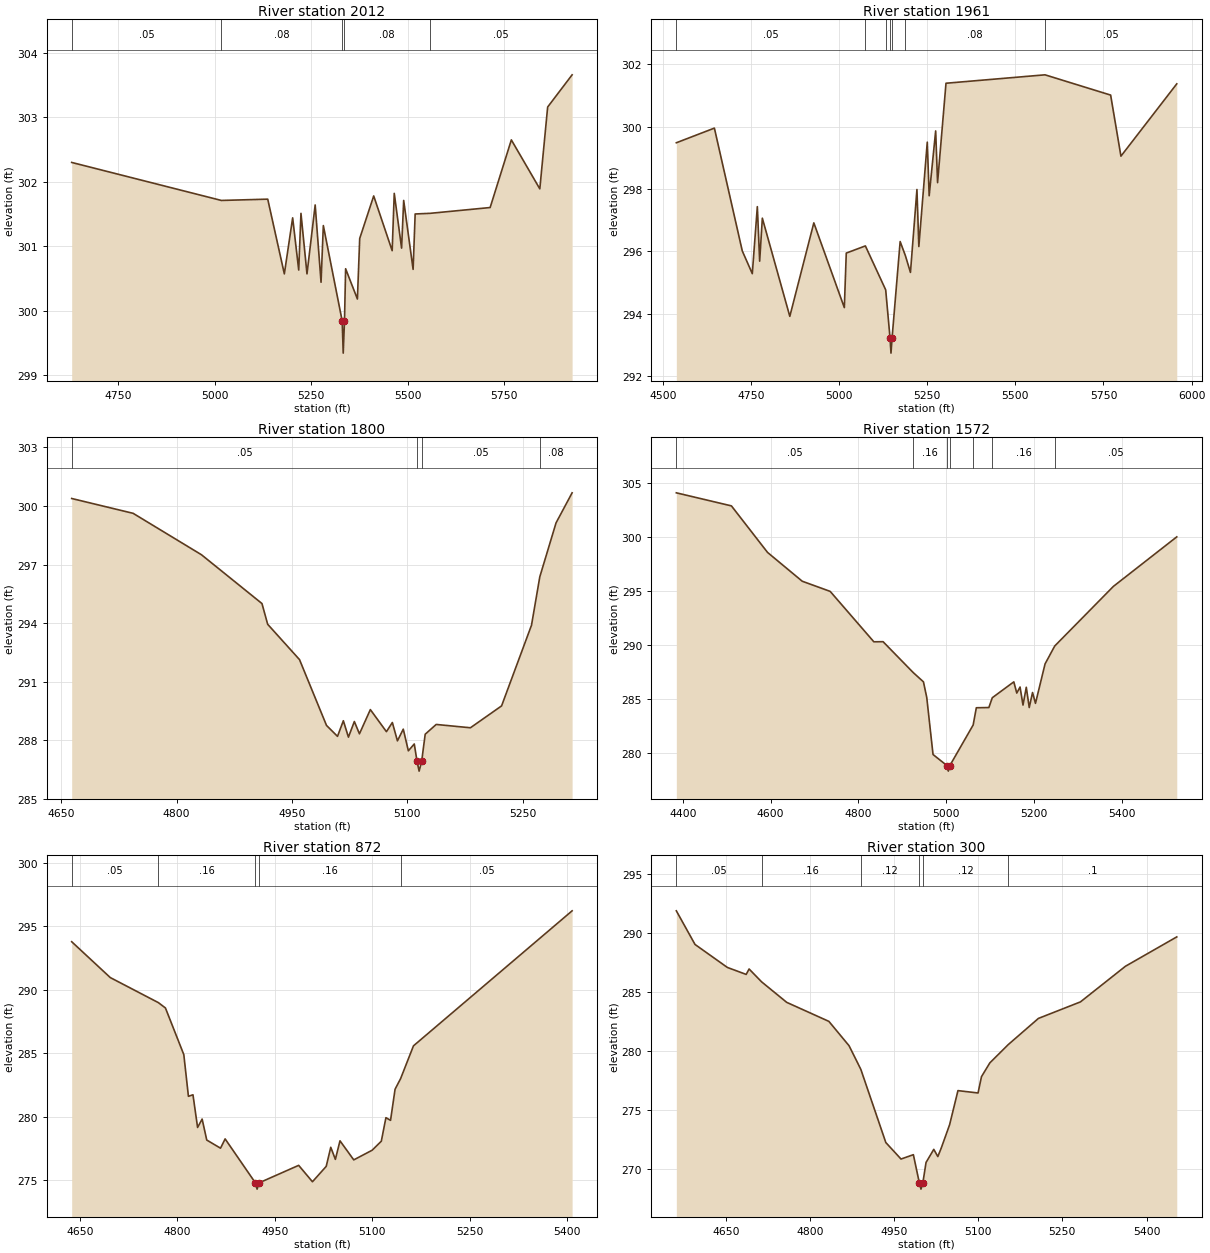
Type RM Length L Ch R = 1 ,2012    ,51,51,51
BEGIN DESCRIPTION:
Mapping XS 69f53382
END DESCRIPTION:
XS GIS Cut Line= 6
      3571526.62     10242982.79      3571704.34     10242814.07
      3571683.51     10242602.27      3571407.46     10242433.87
      3571138.37     10242327.96      3570923.07      10242291.5
#Sta/Elev= 30
  4630.3   302.3  5017.8  301.71  5137.8  301.73  5180.8  300.57  5202.3  301.44
    5218  300.63  5223.8  301.51  5239.4  300.57  5260.6  301.64  5275.8  300.44
  5281.7  301.32  5330.5  299.84  5333.2  299.34  5336.5  299.84  5339.4  300.65
  5369.9  300.18  5375.9  301.12  5412.1  301.78  5459.9  300.93  5465.3  301.82
  5484.3  300.97  5489.7  301.71  5514.1  300.64  5519.4   301.5    5558  301.51
  5713.5   301.6  5768.4  302.65  5842.1  301.89  5862.4  303.16  5925.7  303.66
#Mann= 5 ,-1 , 0
  4630.3     .05       0  5017.8     .08       0  5330.5     .04       0
  5336.5     .08       0    5558     .05       0
Bank Sta=5330.5,5336.5
XS Rating Curve= 0 ,0
Exp/Cntr=0.3,0.1

Type RM Length L Ch R = 1 ,1961    ,161,161,161
BEGIN DESCRIPTION:
Mapping XS 8a3944b2
END DESCRIPTION:
XS GIS Cut Line= 6
      3571506.41     10243025.89       3571647.9     10242931.56
      3571754.69     10242808.87      3571752.95     10242678.66
      3571690.45     10242546.71      3570938.48     10242249.36
#Sta/Elev= 30
  4538.7  299.48  4646.6  299.95  4725.7  296.01  4754.1  295.28  4768.4  297.43
    4775  295.68  4782.6  297.06  4860.5  293.91  4928.6  296.91  5015.1  294.19
  5020.6  295.94  5074.8  296.17  5132.4  294.76  5144.6  293.23  5147.4  292.73
  5150.6  293.23  5173.4  296.31  5188.2  295.86  5202.6  295.32    5221  297.98
  5226.4  296.15  5250.3   299.5  5255.7  297.78  5274.1  299.86  5279.5   298.2
  5303.4  301.39  5584.2  301.66  5770.3  301.01  5799.5  299.05  5957.8  301.37
#Mann= 7 ,-1 , 0
  4538.7     .05       0  5074.8     .08       0  5132.4     .05       0
  5144.6     .04       0  5150.6     .05       0  5188.2     .08       0
  5584.2     .05       0
Bank Sta=5144.6,5150.6
XS Rating Curve= 0 ,0
Exp/Cntr=0.3,0.1

Type RM Length L Ch R = 1 ,1800    ,228,228,228
BEGIN DESCRIPTION:
UNT05245 IN WICK 3.0
END DESCRIPTION:
XS GIS Cut Line= 4
      3571956.07     10242907.78      3571926.56     10242652.62
      3571749.48     10242499.84      3571591.48     10242524.15
#Sta/Elev= 30
  4663.5  300.38  4743.4  299.62  4832.2   297.5  4910.9     295  4918.3  293.94
  4959.7  292.13  4994.8  288.76  5009.1   288.2  5016.7     289  5023.3  288.16
    5031  288.96  5037.6  288.33  5051.8  289.57  5072.7  288.44  5080.4  288.91
    5087  287.97  5094.6  288.57  5101.2  287.46  5108.9  287.81  5112.5  286.92
  5115.2  286.42  5118.5  286.92  5123.1  288.31  5137.4  288.81  5181.9  288.64
  5222.4  289.76  5261.3  293.89  5272.1  296.37  5293.2  299.13  5314.1  300.67
#Mann= 4 ,-1 , 0
  4663.5     .05       0  5112.5     .04       0  5118.5     .05       0
  5272.1     .08       0
Bank Sta=5112.5,5118.5
XS Rating Curve= 0 ,0
Exp/Cntr=0.3,0.1

Type RM Length L Ch R = 1 ,1572    ,700,700,700
BEGIN DESCRIPTION:
Mapping XS af4252f2
END DESCRIPTION:
XS GIS Cut Line= 3
      3572206.95      10242954.6       3572151.4     10242676.86
      3571581.94     10242037.95
#Sta/Elev= 30
  4385.5  304.12  4510.9  302.91  4593.1   298.6  4672.1  295.93  4735.7  294.99
  4835.1  290.32  4856.1  290.33  4924.7  287.47    4948  286.61  4955.5  285.17
  4969.8  279.88  5001.9  278.84  5004.6  278.34  5007.9  278.84  5061.1  282.61
  5068.4  284.21  5096.9  284.23  5104.7  285.14  5153.7  286.61  5160.4  285.57
  5167.9  286.13  5174.6  284.46  5182.1  286.11  5188.8  284.23  5196.3  285.62
    5203  284.62  5224.8  288.27  5246.8  289.93  5380.3  295.45  5524.6  300.04
#Mann= 7 ,-1 , 0
  4385.5     .05       0  4924.7     .16       0  5001.9     .07       0
  5007.9     .16       0  5061.1     .05       0  5104.7     .16       0
  5246.8     .05       0
Bank Sta=5001.9,5007.9
XS Rating Curve= 0 ,0
Exp/Cntr=0.3,0.1

Type RM Length L Ch R = 1 ,872     ,572,572,572
BEGIN DESCRIPTION:
UNT05245 IN WICK 2.0
END DESCRIPTION:
XS GIS Cut Line= 2
      3572493.99     10242503.83      3571947.14     10241961.32
#Sta/Elev= 30
  4637.4  293.78  4696.8  290.96  4770.8  288.99  4781.7  288.57    4810   284.9
  4817.1  281.62  4824.1  281.74  4831.2  279.17  4838.2  279.83  4845.3  278.18
  4866.5  277.54  4873.6  278.27  4920.1  274.82  4922.8  274.32  4926.1  274.82
  4986.8  276.19    5008   274.9  5029.2  276.11  5036.2  277.61  5043.3  276.66
  5050.4  278.12  5071.6  276.62  5099.9  277.38    5114  278.09  5121.1  279.94
  5128.2  279.73  5135.2  282.18  5143.7  283.01  5163.5  285.59  5407.7  296.21
#Mann= 5 ,-1 , 0
  4637.4     .05       0  4770.8     .16       0  4920.1     .07       0
  4926.1     .16       0  5143.7     .05       0
Bank Sta=4920.1,4926.1
XS Rating Curve= 0 ,0
Exp/Cntr=0.3,0.1

Type RM Length L Ch R = 1 ,300     ,0,0,0
BEGIN DESCRIPTION:
UNT05245 IN WICK 1.0
END DESCRIPTION:
XS GIS Cut Line= 4
      3572641.56     10242373.61        3572711.      10242134.9
      3572472.29     10241787.68      3572250.93     10241770.32
#Sta/Elev= 30
  4561.9  291.88  4595.2  289.03  4652.9  287.08  4686.4  286.49  4691.6  286.95
  4713.9  285.86  4758.7  284.12  4833.8  282.51  4869.7  280.45  4890.7  278.45
  4935.3  272.24  4962.4  270.84  4984.4  271.21  4995.2  268.79    4998  268.29
  5001.2  268.79    5007  270.55  5020.8  271.66    5028  271.05  5034.1  271.77
    5049  273.75  5063.9  276.64  5099.7  276.44  5105.8  277.82  5120.7  278.99
  5153.5  280.54  5207.3  282.76  5282.2  284.16  5362.4  287.18  5453.9  289.67
#Mann= 6 ,-1 , 0
  4561.9     .05       0  4713.9     .16       0  4890.7     .12       0
  4995.2     .07       0  5001.2     .12       0  5153.5      .1       0
Bank Sta=4995.2,5001.2
XS Rating Curve= 0 ,0
Exp/Cntr=0.3,0.1

Chan Stop Cuts=-1
Use User Specified Reach Order=0
Composite Channel Slope=5