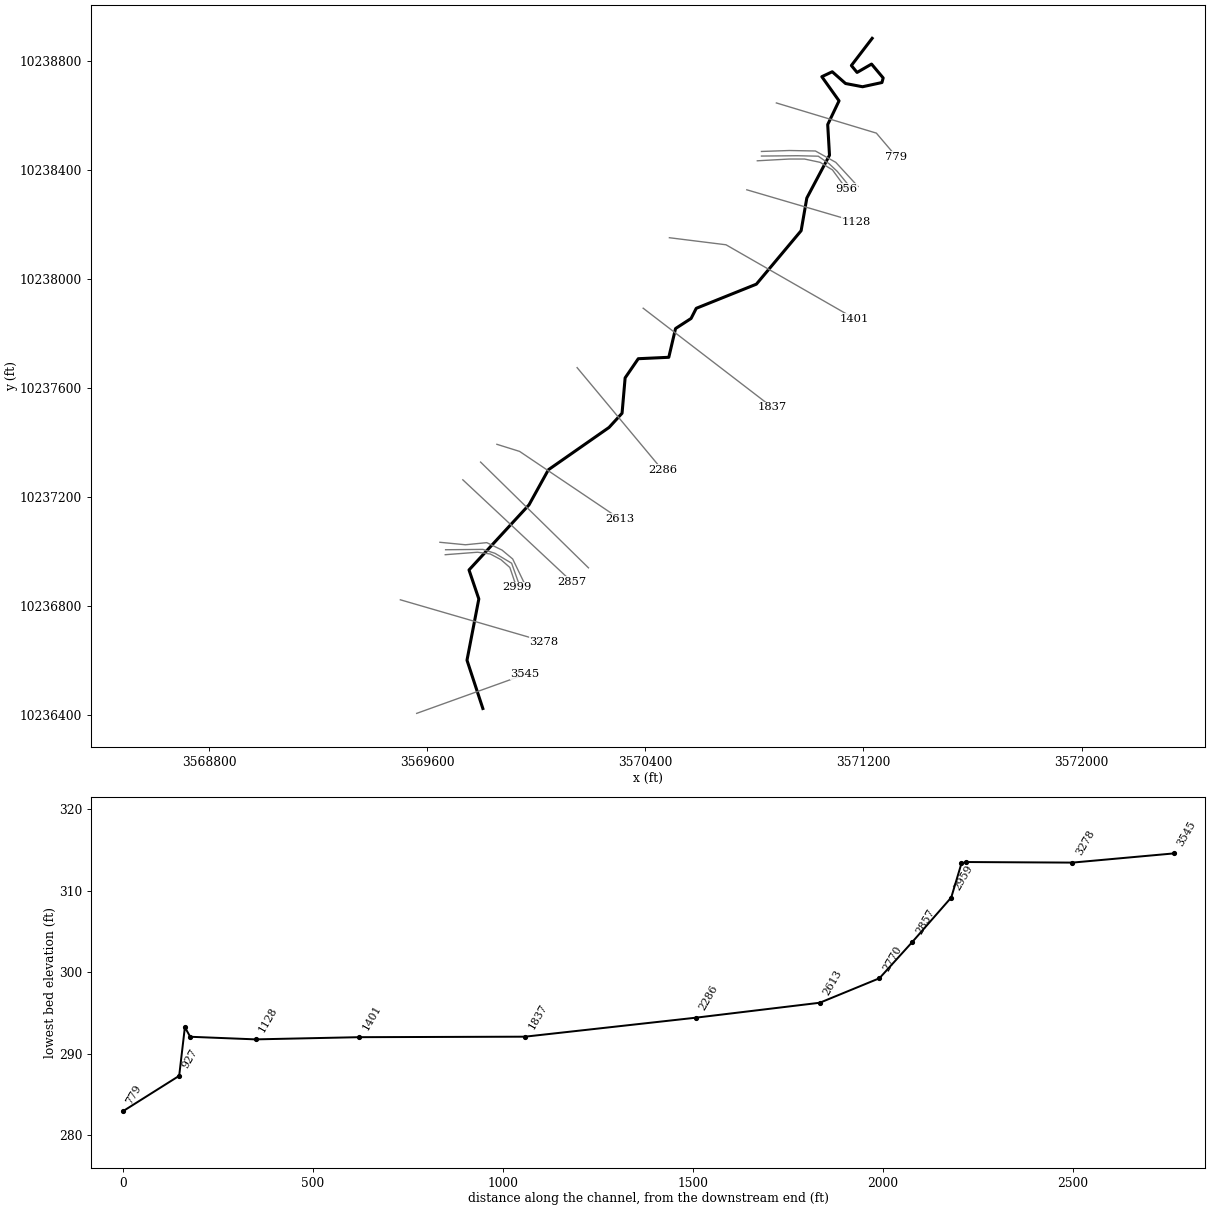
--- STEEPHOLLOWBRANCH.prj (project) ---

Proj Title=STEEP HOLLOW BRANCH TRIB 7
Current Plan=p01
Default Exp/Contr=0.3,0.1
English Units
Geom File=g01
Flow File=f01
Plan File=p01
Y Axis Title=Elevation
X Axis Title(PF)=Main Channel Distance
X Axis Title(XS)=Station
BEGIN DESCRIPTION:
UNT05244 IN WICK
END DESCRIPTION:
DSS Export Rating Curves= 0
DSS Export Rating Curve Sorted= 0
DSS Export Volume Flow Curves= 0
DXF Filename=UNT05244 IN WICK.
DXF OffsetX= 0
DXF OffsetY= 0
DXF ScaleX= 1
DXF ScaleY= 10

--- STEEPHOLLOWBRANCH.p01 (plan) ---

Plan Title=Multiple Run
Short Identifier=Multiple
Geom File=g01
Flow File=f01
Subcritical Flow
K Sum by GR= 0
Std Step Tol= 0.01
Critical Tol= 0.01
Num of Std Step Trials= 20
Max Error Tol= 0.3
Flow Tol Ratio= 0.001
Split Flow NTrial= 30
Split Flow Tol= 0.02
Split Flow Ratio= 0.02
Log Output Level= 0
Friction Slope Method= 1
Unsteady Friction Slope Method= 2
Unsteady Bridges Friction Slope Method= 1
Parabolic Critical Depth
Global Vel Dist=  1 , 1 , 1
Global Log Level= 0
CheckData=True
Encroach Param= -1, 0, 0, 0
BEGIN DESCRIPTION:
Multiple Run
END DESCRIPTION:

--- STEEPHOLLOWBRANCH.f01 (steady flow) ---

Flow Title=Multiple
Program Version=4.10
Number of Profiles= 7
Profile Names=10-year,25-year,50-year,1pct_min,100-year,1pct_plu,500-year
River Rch & RM=UNT05244 IN WICK,Reach-1         ,3545
     152     188     215     181     245     332     319
River Rch & RM=STEEPHOLLOWBRTR7,Reach-1         ,3545
     152     188     215     181     245     332     319
Boundary for River Rch & Prof#=STEEPHOLLOWBRTR7,Reach-1         , 1
Up Type= 0
Dn Type= 3
Dn Slope=0.04
Boundary for River Rch & Prof#=STEEPHOLLOWBRTR7,Reach-1         , 2
Up Type= 0
Dn Type= 3
Dn Slope=0.04
Boundary for River Rch & Prof#=STEEPHOLLOWBRTR7,Reach-1         , 3
Up Type= 0
Dn Type= 3
Dn Slope=0.04
Boundary for River Rch & Prof#=STEEPHOLLOWBRTR7,Reach-1         , 4
Up Type= 0
Dn Type= 3
Dn Slope=0.04
Boundary for River Rch & Prof#=STEEPHOLLOWBRTR7,Reach-1         , 5
Up Type= 0
Dn Type= 3
Dn Slope=0.04
Boundary for River Rch & Prof#=STEEPHOLLOWBRTR7,Reach-1         , 6
Up Type= 0
Dn Type= 3
Dn Slope=0.04
Boundary for River Rch & Prof#=STEEPHOLLOWBRTR7,Reach-1         , 7
Up Type= 0
Dn Type= 3
Dn Slope=0.04
DSS Import GetInterval= 0
DSS Import GetPeak= 0
DSS Import FillOption= 0

--- STEEPHOLLOWBRANCH.g01 (geometry) ---

Geom Title=Existing Conditions
Program Version=4.10

River Reach=STEEPHOLLOWBRTR7,Reach-1
Reach XY= 30
      3569803.98     10236423.32      3569745.82     10236600.41
      3569789.23     10236825.23      3569753.24     10236931.52
      3569973.29     10237170.33      3570044.47     10237299.14
      3570266.91      10237454.3      3570314.65     10237506.39
      3570325.92     10237636.12       3570374.1     10237706.43
      3570486.08     10237711.64      3570510.82     10237817.11
      3570567.76       10237854.      3570586.86     10237891.33
      3570807.34     10237979.87      3570971.55     10238176.09
      3570992.39     10238295.88      3571075.58     10238452.81
      3571069.01     10238565.32      3571110.59      10238652.4
      3571047.41     10238740.94      3571085.66     10238759.04
      3571134.43     10238715.93      3571196.84     10238704.07
      3571268.01     10238719.53      3571272.46     10238736.35
      3571229.86     10238787.22       3571176.7     10238756.55
      3571155.79     10238781.92      3571232.11     10238881.64

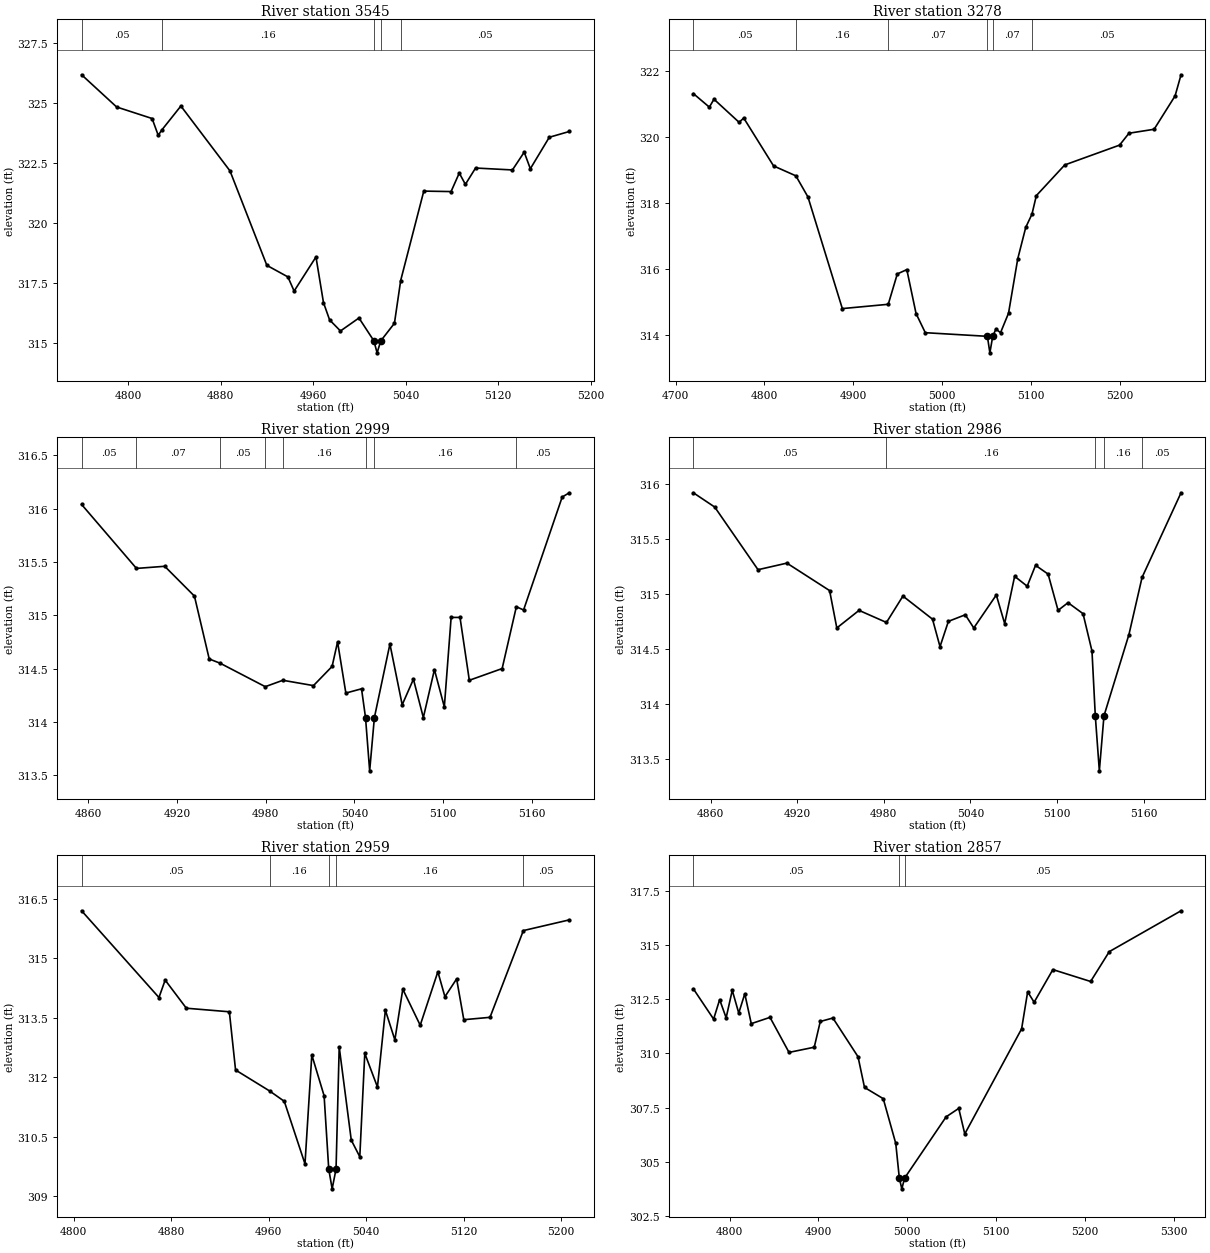
Type RM Length L Ch R = 1 ,3545    ,267,267,267
BEGIN DESCRIPTION:
UNT05244 IN WICK 7.0
END DESCRIPTION:
XS GIS Cut Line= 2
      3569561.29     10236405.45      3569958.41     10236548.21
#Sta/Elev= 30
  4759.6  326.17  4789.9  324.83  4820.6  324.35  4825.9  323.65  4828.8  323.86
  4845.5  324.87    4888  322.17  4919.9  318.24  4938.1  317.76  4943.5  317.17
  4962.4  318.59  4968.9  316.69  4974.2  315.97  4983.6  315.51  4999.6  316.05
  5012.5   315.1  5015.3   314.6  5018.5   315.1  5030.3  315.83  5035.7  317.61
  5055.7  321.33  5079.3  321.31  5086.4  322.08  5091.7  321.61  5100.5  322.29
  5132.4  322.21  5142.6  322.95  5147.9  322.26  5164.3  323.57  5181.6  323.81
#Mann= 5 ,-1 , 0
  4759.6     .05       0  4828.8     .16       0  5012.5     .07       0
  5018.5     .16       0  5035.7     .05       0
Bank Sta=5012.5,5018.5
XS Rating Curve= 0 ,0
Exp/Cntr=0.3,0.1

Type RM Length L Ch R = 1 ,3278    ,279,279,279
BEGIN DESCRIPTION:
UNT05244 IN WICK 6.0
END DESCRIPTION:
XS GIS Cut Line= 2
      3569501.37      10236822.1      3570028.56     10236668.88
#Sta/Elev= 30
    4720  321.32    4738  320.91  4743.2  321.15  4771.5  320.45  4776.7  320.58
  4810.3  319.13  4835.4  318.83    4849  318.19  4887.7  314.81  4939.4  314.94
  4949.6  315.86  4960.3  315.99  4970.7  314.66  4981.1  314.08    5051  313.97
  5053.8  313.47    5057  313.97  5060.6  314.19  5065.8  314.08  5074.8  314.67
  5085.2  316.32  5094.2  317.27  5101.2  317.67  5106.1  318.23  5138.1  319.16
  5199.8  319.76  5210.4  320.12  5238.7  320.24  5262.3  321.25    5269  321.89
#Mann= 6 ,-1 , 0
    4720     .05       0  4835.4     .16       0  4939.4     .07       0
    5051     .07       0    5057     .07       0  5101.2     .05       0
Bank Sta=5051,5057
XS Rating Curve= 0 ,0
Exp/Cntr=0.3,0.1

Type RM Length L Ch R = 1 ,2999    ,13,13,13
BEGIN DESCRIPTION:
Mapping XS 3c6cbc24
END DESCRIPTION:
XS GIS Cut Line= 6
      3569666.04     10236987.47      3569784.56     10236996.59
      3569831.43     10236990.07      3569870.49     10236969.24
      3569903.05      10236940.6      3569927.46     10236868.65
#Sta/Elev= 30
  4855.5  316.04  4892.6  315.44  4911.7  315.46  4931.8  315.18  4941.8  314.59
  4949.2  314.55  4979.7  314.33  4991.6  314.39  5012.3  314.34  5024.9  314.52
  5028.6  314.75  5034.2  314.27  5044.8  314.31  5047.5  314.04  5050.3  313.54
  5053.5  314.04    5064  314.73  5072.3  314.16  5079.9   314.4  5086.6  314.04
  5094.1  314.49  5100.8  314.14  5105.4  314.98  5111.4  314.98  5117.7  314.39
  5139.9   314.5  5149.5  315.08  5154.4  315.05  5180.5  316.11  5185.3  316.15
#Mann= 8 ,-1 , 0
  4855.5     .05       0  4892.6     .07       0  4949.2     .05       0
  4979.7     .07       0  4991.6     .16       0  5047.5     .07       0
  5053.5     .16       0  5149.5     .05       0
Bank Sta=5047.5,5053.5
XS Rating Curve= 0 ,0
Exp/Cntr=0.3,0.1

Type RM Length L Ch R = 1 ,2986    ,27,27,27
BEGIN DESCRIPTION:
Mapping XS ae7a7aa0
END DESCRIPTION:
XS GIS Cut Line= 5
      3569667.34      10237005.7      3569804.09       10237007.
      3569848.36     10236992.68      3569909.56     10236956.22
      3569937.44     10236877.64
#Sta/Elev= 30
  4848.1  315.92  4862.9  315.79  4892.9  315.22  4912.9  315.28  4942.5  315.03
  4947.5  314.69  4962.9  314.85  4981.9  314.74  4993.3  314.98  5013.8  314.77
    5019  314.52  5024.8  314.75  5036.5  314.81  5042.4  314.69    5058  314.99
  5063.8  314.73  5070.7  315.16  5079.4  315.07  5085.2  315.26  5093.9  315.18
  5100.8  314.85  5107.7  314.92  5118.1  314.82  5124.3  314.48  5126.6  313.89
  5129.4  313.39  5132.6  313.89  5149.9  314.63    5159  315.15    5186  315.92
#Mann= 5 ,-1 , 0
  4848.1     .05       0  4981.9     .16       0  5126.6     .07       0
  5132.6     .16       0    5159     .05       0
Bank Sta=5126.6,5132.6
XS Rating Curve= 0 ,0
Exp/Cntr=0.3,0.1

Type RM Length L Ch R = 1 ,2959    ,102,102,102
BEGIN DESCRIPTION:
Mapping XS 015b4f1c
END DESCRIPTION:
XS GIS Cut Line= 6
       3569646.5     10237033.05      3569740.29     10237023.93
      3569818.41     10237031.74       3569874.4      10237004.4
      3569913.46     10236971.85      3569962.95     10236868.95
#Sta/Elev= 30
  4806.4   316.2  4869.9  314.01    4875  314.45  4892.4  313.74  4927.7  313.65
  4932.8  312.18  4960.8  311.65  4972.8  311.39  4989.8  309.81  4995.4  312.56
  5005.5  311.53  5009.3  309.68  5012.1  309.18  5015.3  309.68  5017.9  312.76
  5027.8  310.41  5034.8  309.99  5038.9   312.6  5049.3  311.75  5055.8  313.69
  5063.6  312.94  5070.1  314.22  5084.4  313.31  5098.9  314.66  5104.7  314.03
  5114.3  314.48  5120.2  313.45  5141.7  313.51  5169.1   315.7  5206.8  315.97
#Mann= 5 ,-1 , 0
  4806.4     .05       0  4960.8     .16       0  5009.3     .07       0
  5015.3     .16       0  5169.1     .05       0
Bank Sta=5009.3,5015.3
XS Rating Curve= 0 ,0
Exp/Cntr=0.3,0.1

Type RM Length L Ch R = 1 ,2857    ,87,87,87
BEGIN DESCRIPTION:
Mapping XS c20256d5
END DESCRIPTION:
XS GIS Cut Line= 2
      3569730.52     10237262.21       3570131.6     10236887.18
#Sta/Elev= 30
  4759.2  312.99    4782  311.59  4788.8  312.49  4796.1  311.65    4803  312.92
  4810.3  311.87  4817.1  312.76  4824.4  311.38  4845.5  311.67  4866.9  310.05
  4895.3  310.29  4902.1  311.48  4916.3  311.64  4944.6  309.85  4951.9  308.43
    4973  307.91  4987.1  305.84  4991.1  304.24  4993.9  303.74  4997.1  304.24
  5043.8  307.07    5058  307.46  5064.8  306.28  5128.8  311.14  5135.6  312.85
  5142.9  312.37    5164  313.88  5206.5  313.33  5227.5  314.71  5308.3   316.6
#Mann= 3 ,-1 , 0
  4759.2     .05       0  4991.1     .04       0  4997.1     .05       0
Bank Sta=4991.1,4997.1
XS Rating Curve= 0 ,0
Exp/Cntr=0.3,0.1

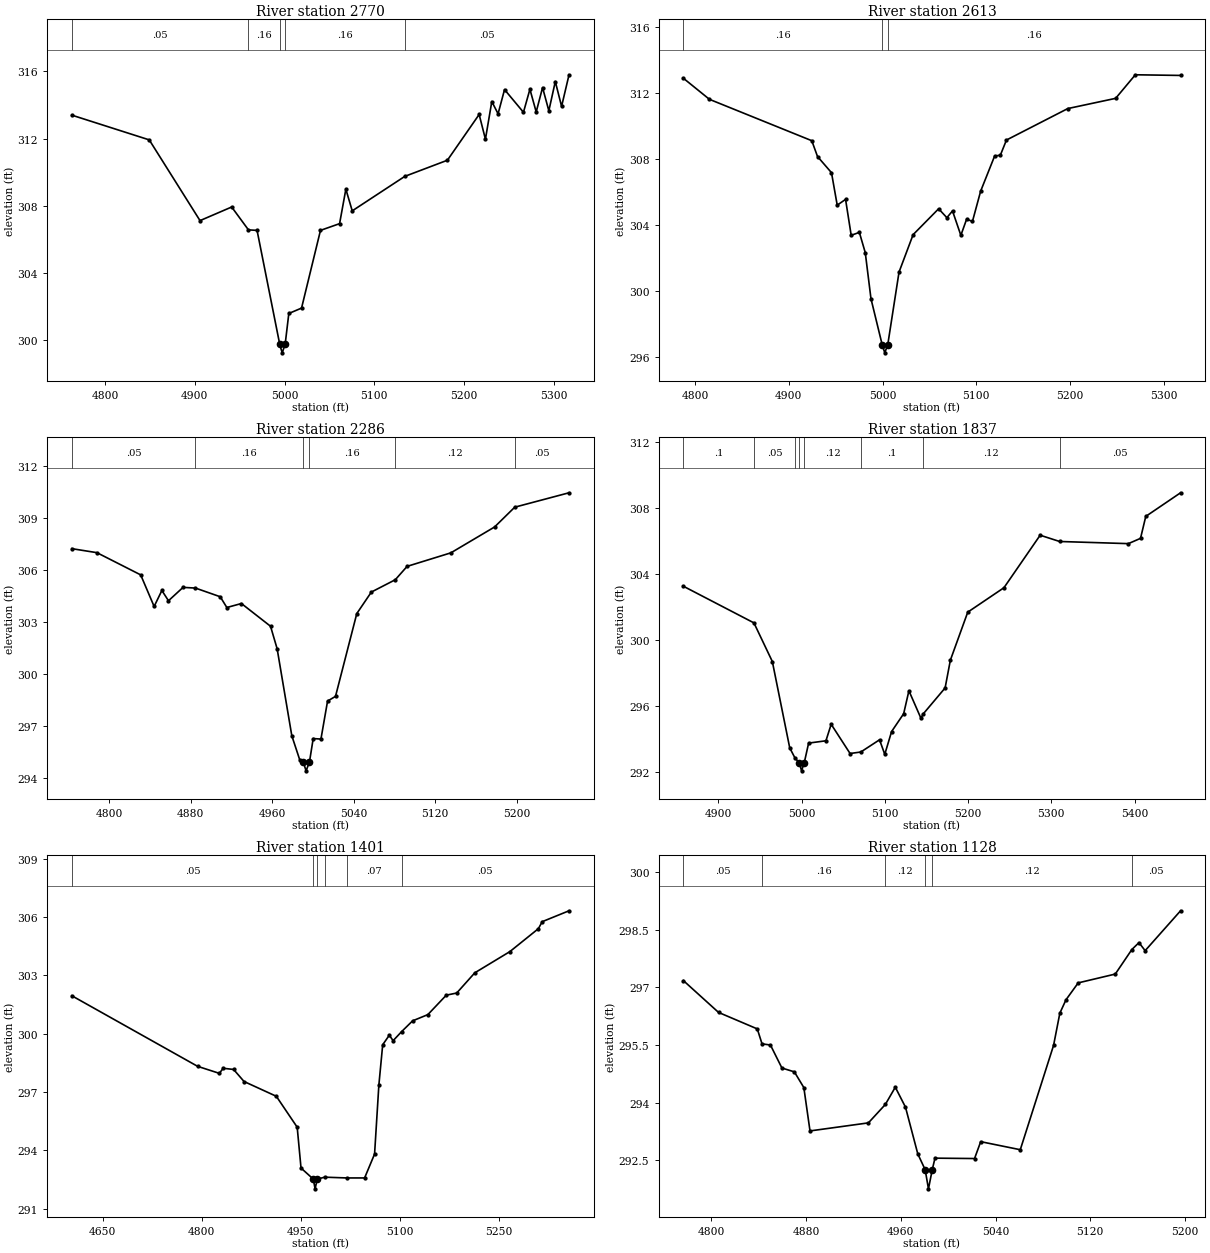
Type RM Length L Ch R = 1 ,2770    ,157,157,157
BEGIN DESCRIPTION:
Mapping XS 102f8f9d
END DESCRIPTION:
XS GIS Cut Line= 2
      3569795.66     10237327.28      3570191.49     10236939.26
#Sta/Elev= 30
  4762.9  313.39  4849.2  311.92  4905.8  307.12  4941.1  307.93  4959.8  306.57
  4969.4  306.54  4994.7  299.76  4997.4  299.26  5000.7  299.76  5004.8   301.6
    5019  301.92  5040.1  306.54  5061.4  306.94  5068.4  308.99  5075.5   307.7
  5134.1  309.75  5181.6  310.71    5217  313.43    5224  311.96  5231.1   314.2
  5238.1  313.47  5245.3  314.91  5266.4  313.56  5273.6  314.93  5280.6  313.58
  5287.7  315.03  5294.7  313.65  5301.9  315.39  5308.9  313.91  5317.2  315.79
#Mann= 5 ,-1 , 0
  4762.9     .05       0  4959.8     .16       0  4994.7     .07       0
  5000.7     .16       0  5134.1     .05       0
Bank Sta=4994.7,5000.7
XS Rating Curve= 0 ,0
Exp/Cntr=0.3,0.1

Type RM Length L Ch R = 1 ,2613    ,327,327,327
BEGIN DESCRIPTION:
UNT05244 IN WICK 5.0
END DESCRIPTION:
XS GIS Cut Line= 3
      3569855.56     10237392.41      3569938.85     10237366.38
      3570306.03     10237118.99
#Sta/Elev= 30
  4787.7  312.91  4815.5  311.63  4924.6  309.12  4930.7  308.16  4945.6  307.18
  4951.7  305.21  4960.6  305.56  4966.6  303.38  4975.3  303.56  4981.6  302.33
  4987.7  299.53  4999.6  296.75  5002.4  296.25  5005.6  296.75  5017.6  301.15
  5032.6  303.42  5059.8  304.99  5068.6  304.45  5074.6  304.86  5083.5  303.38
  5089.6  304.35  5095.9  304.23  5104.6  306.06  5119.5  308.19  5125.6  308.24
  5132.1  309.16  5197.5  311.07  5248.5  311.69  5269.5  313.12  5317.7  313.08
#Mann= 3 ,-1 , 0
  4787.7     .16       0  4999.6     .07       0  5005.6     .16       0
Bank Sta=4999.6,5005.6
XS Rating Curve= 0 ,0
Exp/Cntr=0.3,0.1

Type RM Length L Ch R = 1 ,2286    ,449,449,449
BEGIN DESCRIPTION:
UNT05244 IN WICK 4.0
END DESCRIPTION:
XS GIS Cut Line= 2
      3570149.78     10237673.68      3570462.32     10237298.63
#Sta/Elev= 30
  4763.3  307.21  4787.9  306.98  4830.9   305.7  4844.1  303.88  4851.7   304.8
  4858.2  304.21  4872.5  304.98  4884.7  304.94    4909  304.44  4915.5  303.82
  4929.8  304.05  4958.4  302.74  4964.9  301.44  4979.3  296.43  4987.1  295.04
  4990.6  294.91  4993.3  294.41  4996.6  294.91  5000.3  296.27  5007.9  296.24
  5014.4  298.43  5022.2   298.7  5043.1  303.47  5057.4  304.71  5080.9  305.42
  5092.5  306.19  5135.5  306.97  5178.4  308.46  5198.2   309.6  5251.5  310.43
#Mann= 6 ,-1 , 0
  4763.3     .05       0  4884.7     .16       0  4990.6     .07       0
  4996.6     .16       0  5080.9     .12       0  5198.2     .05       0
Bank Sta=4990.6,4996.6
XS Rating Curve= 0 ,0
Exp/Cntr=0.3,0.1

Type RM Length L Ch R = 1 ,1837    ,436,436,436
BEGIN DESCRIPTION:
UNT05244 IN WICK 3.0
END DESCRIPTION:
XS GIS Cut Line= 2
       3570392.1     10237891.64      3570865.95     10237527.83
#Sta/Elev= 30
  4857.9  303.26  4942.7  301.04  4964.8   298.7  4985.7  293.47  4992.3  292.83
  4997.2  292.58  4999.9  292.08  5003.2  292.58  5008.4  293.76  5029.2   293.9
  5035.5   294.9  5058.2  293.13  5071.1  293.22  5093.6  293.96  5099.9  293.08
  5108.1  294.46  5122.6  295.54  5128.9  296.93  5143.4  295.26  5145.8  295.51
  5172.4   297.1  5178.7  298.78  5199.6  301.69  5243.1  303.17  5286.6  306.35
    5310  305.97  5392.6  305.84  5407.2  306.16  5413.5  307.49  5455.3  308.92
#Mann= 8 ,-1 , 0
  4857.9      .1       0  4942.7     .05       0  4992.3     .12       0
  4997.2     .07       0  5003.2     .12       0  5071.1      .1       0
  5145.8     .12       0    5310     .05       0
Bank Sta=4997.2,5003.2
XS Rating Curve= 0 ,0
Exp/Cntr=0.3,0.1

Type RM Length L Ch R = 1 ,1401    ,273,273,273
BEGIN DESCRIPTION:
UNT05244 IN WICK 2.0
END DESCRIPTION:
XS GIS Cut Line= 3
      3570488.32     10238150.23      3570695.96     10238124.36
      3571167.53     10237853.64
#Sta/Elev= 30
  4603.3  301.95  4793.8  298.32  4826.7  297.96  4832.5  298.22  4848.3  298.16
  4864.1  297.54    4913  296.78  4944.6  295.19  4950.4  293.09    4969  292.52
  4971.7  292.02    4975  292.52  4986.2  292.62  5019.9  292.58  5046.7  292.58
  5061.8  293.81  5068.3  297.36  5074.1  299.43  5084.1  299.92  5089.9  299.64
  5102.6   300.1  5119.4  300.66  5142.5  300.98  5170.4  301.98  5186.2  302.09
  5213.6  303.13  5266.7  304.22  5309.9   305.4  5315.7  305.76  5356.3  306.32
#Mann= 6 ,-1 , 0
  4603.3     .05       0    4969     .07       0    4975     .05       0
  4986.2     .12       0  5019.9     .07       0  5102.6     .05       0
Bank Sta=4969,4975
XS Rating Curve= 0 ,0
Exp/Cntr=0.3,0.1

Type RM Length L Ch R = 1 ,1128    ,172,172,172
BEGIN DESCRIPTION:
Mapping XS ba861afe
END DESCRIPTION:
XS GIS Cut Line= 2
      3570772.22     10238326.05      3571174.98       10238208.
#Sta/Elev= 30
  4776.5  297.18  4806.2  296.35  4838.9  295.92  4842.9  295.53    4850   295.5
  4859.7   294.9  4870.2   294.8  4878.2  294.39  4883.4  293.26  4932.7  293.47
    4947  293.95  4955.4   294.4    4964  293.88  4974.4  292.66  4980.6  292.25
  4983.4  291.75  4986.6  292.25  4988.9  292.55  5022.3  292.54  5027.5  292.98
  5060.9  292.77    5089  295.49  5094.3  296.33  5099.5  296.68  5109.8  297.12
  5141.1  297.35  5155.1  297.99  5161.1  298.17  5166.3  297.96  5196.2     299
#Mann= 6 ,-1 , 0
  4776.5     .05       0  4842.9     .16       0    4947     .12       0
  4980.6     .07       0  4986.6     .12       0  5155.1     .05       0
Bank Sta=4980.6,4986.6
XS Rating Curve= 0 ,0
Exp/Cntr=0.3,0.1

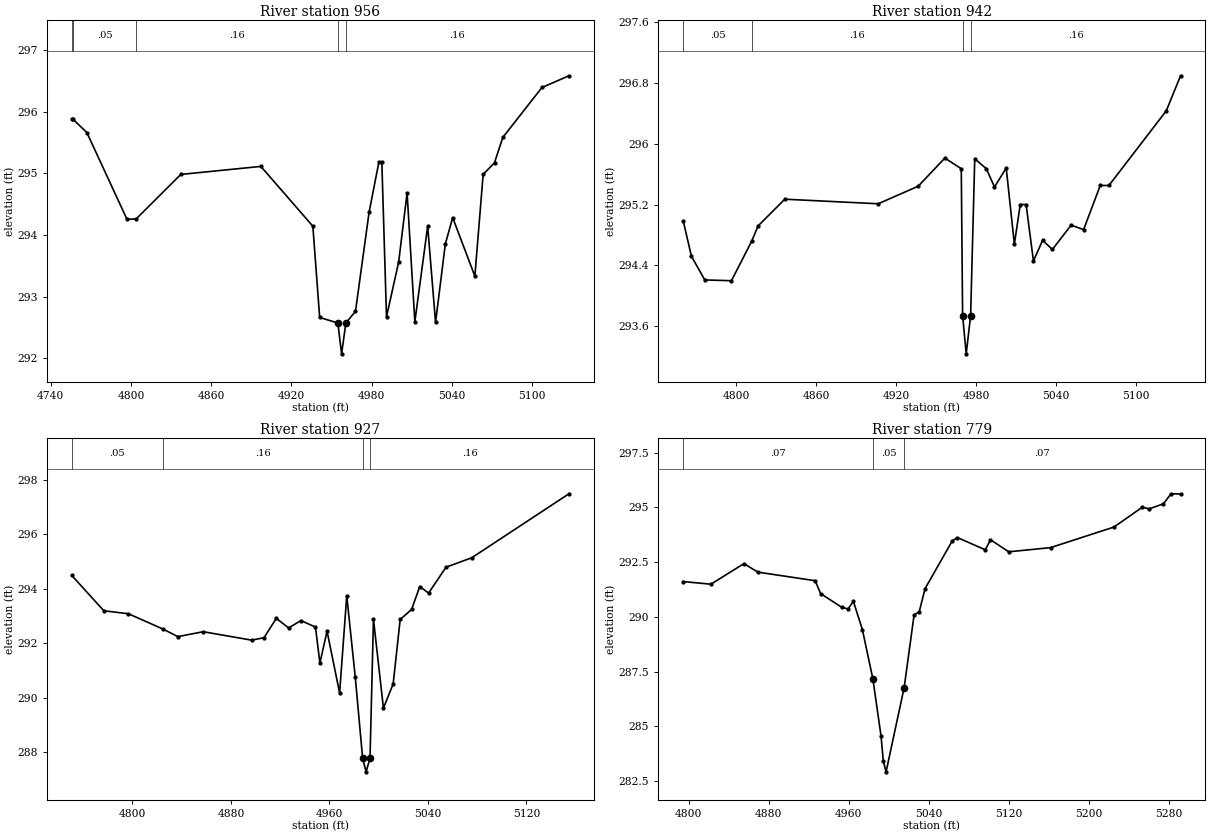
Type RM Length L Ch R = 1 ,956     ,14,14,14
BEGIN DESCRIPTION:
Mapping XS 5ba8662b
END DESCRIPTION:
XS GIS Cut Line= 6
      3570810.81     10238432.44      3570928.47      10238438.9
      3570984.03      10238438.9      3571041.32     10238426.74
      3571086.46     10238398.97      3571137.85     10238328.73
#Sta/Elev= 30
  4755.7  295.88  4756.4  295.88    4767  295.66  4797.1  294.25    4804  294.26
  4837.3  294.98  4897.2  295.11  4936.1  294.14  4941.2  292.66  4954.8  292.57
  4957.6  292.07  4960.8  292.57    4968  292.76  4978.2  294.37  4985.5  295.18
  4987.7  295.18  4991.2  292.67  5000.3  293.56  5006.6  294.68  5012.4  292.59
    5022  294.14  5027.9  292.58  5035.2  293.85  5040.7  294.28  5057.3  293.33
  5063.5  294.98    5072  295.17  5078.2  295.58  5107.5  296.39  5127.7  296.58
#Mann= 5 ,-1 , 0
  4755.7      .1       0  4756.4     .05       0    4804     .16       0
  4954.8     .07       0  4960.8     .16       0
Bank Sta=4954.8,4960.8
XS Rating Curve= 0 ,0
Exp/Cntr=0.3,0.1

Type RM Length L Ch R = 1 ,942     ,15,15,15
BEGIN DESCRIPTION:
Mapping XS 3f1c8aba
END DESCRIPTION:
XS GIS Cut Line= 6
      3570826.02      10238449.8      3570957.99     10238451.05
      3571034.38     10238449.31      3571074.31     10238421.53
      3571103.82     10238393.76      3571151.66     10238335.67
#Sta/Elev= 30
  4760.4  294.98  4766.5  294.52  4776.5  294.21  4796.5   294.2  4811.7  294.72
  4816.5  294.92  4836.5  295.27  4906.5  295.21  4936.5  295.44  4956.5  295.81
  4968.8  295.67  4969.8  293.74  4972.5  293.24  4975.8  293.74  4978.9   295.8
  4987.6  295.67  4993.7  295.43  5002.5  295.68  5008.6  294.68    5013   295.2
  5017.4   295.2  5022.9  294.46  5029.8  294.73  5037.1  294.61  5051.2  294.93
  5060.5  294.87    5073  295.45  5079.5  295.45  5122.5  296.43  5133.2  296.89
#Mann= 4 ,-1 , 0
  4760.4     .05       0  4811.7     .16       0  4969.8     .07       0
  4975.8     .16       0
Bank Sta=4969.8,4975.8
XS Rating Curve= 0 ,0
Exp/Cntr=0.3,0.1

Type RM Length L Ch R = 1 ,927     ,148,148,148
BEGIN DESCRIPTION:
Mapping XS f521f35c
END DESCRIPTION:
XS GIS Cut Line= 5
        3570826.     10238466.67      3570928.47     10238470.15
      3571023.96     10238468.41      3571098.61     10238426.74
      3571180.19     10238338.22
#Sta/Elev= 30
  4750.7  294.49  4776.8  293.19  4796.8  293.08  4824.7  292.52  4836.9  292.24
  4857.5  292.42  4896.9  292.11  4906.9   292.2  4916.9  292.91  4926.9  292.56
  4936.9  292.83  4948.7  292.59  4952.3  291.27  4958.1  292.44  4968.3  290.17
  4974.1  293.74    4981  290.76    4987  287.77  4989.8  287.27    4993  287.77
  4995.8  292.88  5003.9  289.61  5011.8   290.5  5017.5  292.87  5026.8  293.24
  5033.4  294.08  5040.6  293.84  5054.7  294.79  5075.7  295.14  5154.6  297.49
#Mann= 4 ,-1 , 0
  4750.7     .05       0  4824.7     .16       0    4987     .07       0
    4993     .16       0
Bank Sta=4987,4993
XS Rating Curve= 0 ,0
Exp/Cntr=0.3,0.1

Type RM Length L Ch R = 1 ,779     ,0,0,0
BEGIN DESCRIPTION:
UNT05244 IN WICK 1.0
END DESCRIPTION:
XS GIS Cut Line= 3
       3570880.7     10238644.63      3571247.48     10238533.95
       3571321.3     10238447.11
#Sta/Elev= 30
  4794.6  291.61  4822.2  291.49  4855.2  292.43  4869.2  292.04  4926.4  291.65
  4931.9  291.06  4952.8  290.44  4959.3  290.36  4964.6  290.71  4973.6  289.42
  4984.1  287.17  4992.3  284.55  4994.5  283.42  4997.3  282.92  5015.4  286.77
  5025.3  290.08  5030.5  290.24  5036.3  291.29  5063.5  293.47  5068.7  293.62
  5096.5  293.06  5101.7  293.52  5119.9  292.97  5161.7  293.16  5225.1   294.1
  5253.6  295.01  5260.2  294.93  5274.5  295.16  5282.2  295.62  5291.7  295.61
#Mann= 3 , 0 , 0
  4794.6     .07       0  4984.1     .05       0  5015.4     .07       0
Bank Sta=4984.1,5015.4
XS Rating Curve= 0 ,0
Exp/Cntr=0.3,0.1

Chan Stop Cuts=-1
Use User Specified Reach Order=0
Composite Channel Slope=5