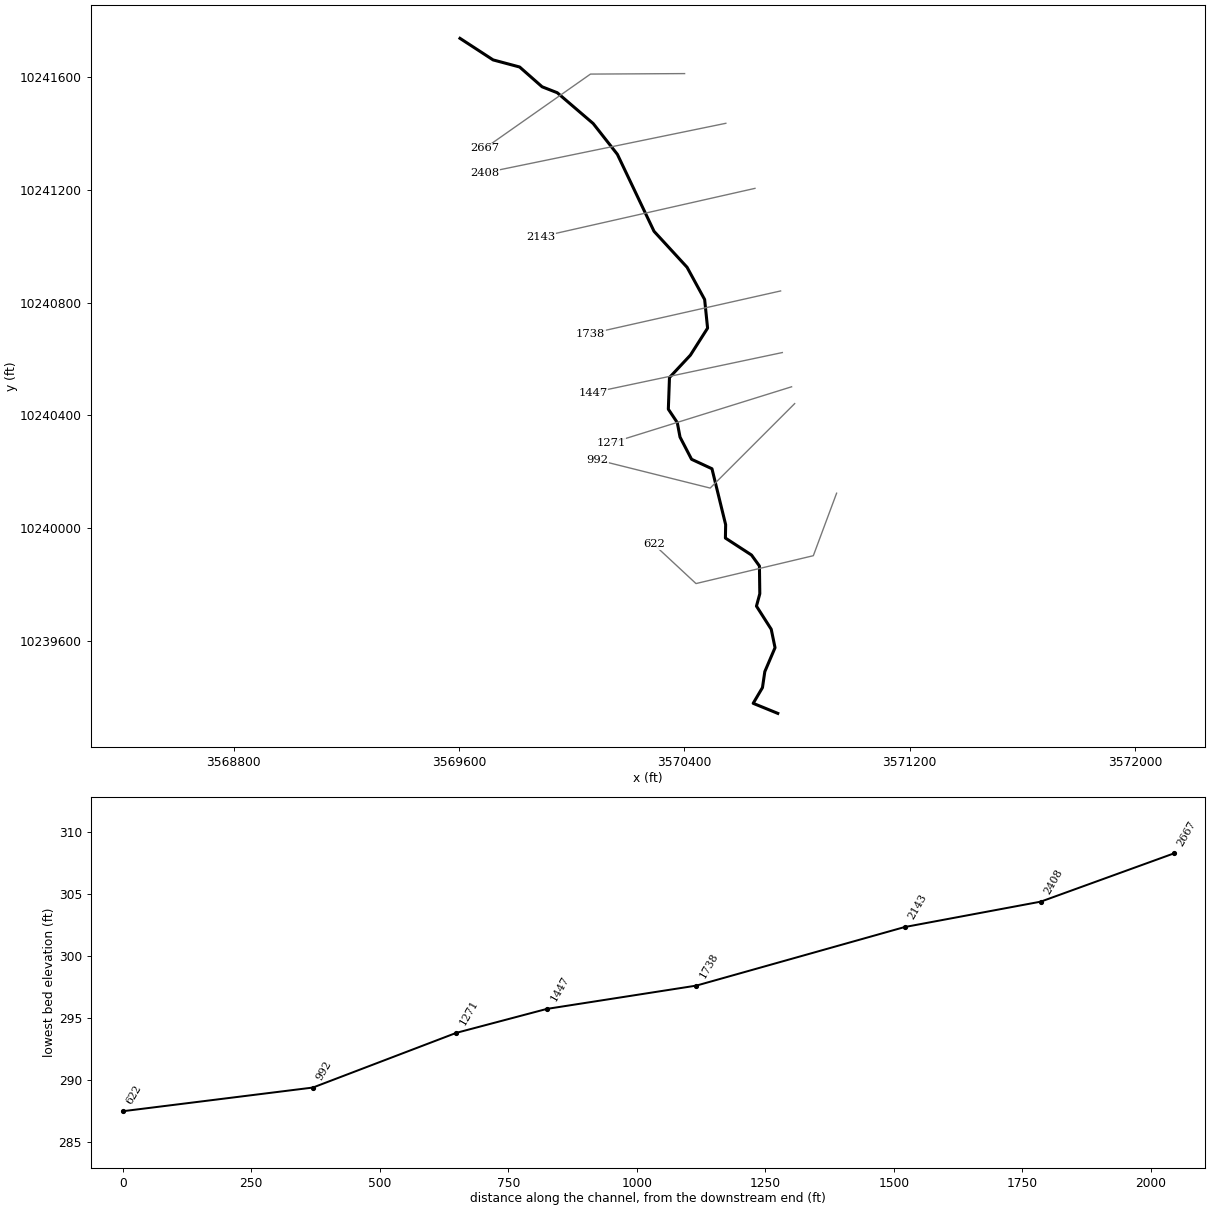
--- STEEPHOLLOWBRANCH.prj (project) ---

Proj Title=STEEP HOLLOW BRANCH TRIB 8
Current Plan=p01
Default Exp/Contr=0.3,0.1
English Units
Geom File=g01
Flow File=f01
Plan File=p01
Y Axis Title=Elevation
X Axis Title(PF)=Main Channel Distance
X Axis Title(XS)=Station
BEGIN DESCRIPTION:
UNT05243 IN WICK
END DESCRIPTION:
DSS Export Rating Curves= 0
DSS Export Rating Curve Sorted= 0
DSS Export Volume Flow Curves= 0
DXF Filename=UNT05243 IN WICK.
DXF OffsetX= 0
DXF OffsetY= 0
DXF ScaleX= 1
DXF ScaleY= 10

--- STEEPHOLLOWBRANCH.p01 (plan) ---

Plan Title=Multiple Run
Short Identifier=Multiple
Geom File=g01
Flow File=f01
Subcritical Flow
K Sum by GR= 0
Std Step Tol= 0.01
Critical Tol= 0.01
Num of Std Step Trials= 20
Max Error Tol= 0.3
Flow Tol Ratio= 0.001
Split Flow NTrial= 30
Split Flow Tol= 0.02
Split Flow Ratio= 0.02
Log Output Level= 0
Friction Slope Method= 1
Unsteady Friction Slope Method= 2
Unsteady Bridges Friction Slope Method= 1
Parabolic Critical Depth
Global Vel Dist=  1 , 1 , 1
Global Log Level= 0
CheckData=True
Encroach Param= -1, 0, 0, 0
BEGIN DESCRIPTION:
Multiple Run
END DESCRIPTION:

--- STEEPHOLLOWBRANCH.f01 (steady flow) ---

Flow Title=Multiple
Program Version=4.10
Number of Profiles= 7
Profile Names=10-year,25-year,50-year,1pct_min,100-year,1pct_plu,500-year
River Rch & RM=UNT05243 IN WICK,Reach-1         ,2667
     127     154     175     146     197     266     250
River Rch & RM=STEEPHOLLOWBRTR8,Reach-1         ,2667
     127     154     175     146     197     266     250
Boundary for River Rch & Prof#=STEEPHOLLOWBRTR8,Reach-1         , 1
Up Type= 0
Dn Type= 3
Dn Slope=0.005
Boundary for River Rch & Prof#=STEEPHOLLOWBRTR8,Reach-1         , 2
Up Type= 0
Dn Type= 3
Dn Slope=0.005
Boundary for River Rch & Prof#=STEEPHOLLOWBRTR8,Reach-1         , 3
Up Type= 0
Dn Type= 3
Dn Slope=0.005
Boundary for River Rch & Prof#=STEEPHOLLOWBRTR8,Reach-1         , 4
Up Type= 0
Dn Type= 3
Dn Slope=0.005
Boundary for River Rch & Prof#=STEEPHOLLOWBRTR8,Reach-1         , 5
Up Type= 0
Dn Type= 3
Dn Slope=0.005
Boundary for River Rch & Prof#=STEEPHOLLOWBRTR8,Reach-1         , 6
Up Type= 0
Dn Type= 3
Dn Slope=0.005
Boundary for River Rch & Prof#=STEEPHOLLOWBRTR8,Reach-1         , 7
Up Type= 0
Dn Type= 3
Dn Slope=0.005
DSS Import GetInterval= 0
DSS Import GetPeak= 0
DSS Import FillOption= 0

--- STEEPHOLLOWBRANCH.g01 (geometry) ---

Geom Title=Existing Conditions
Program Version=4.10

River Reach=STEEPHOLLOWBRTR8,Reach-1
Reach XY= 30
      3569603.61     10241738.66      3569721.23     10241662.05
      3569815.41     10241636.88      3569895.27     10241566.57
      3569948.97     10241545.55      3570076.57     10241436.17
      3570162.51      10241326.8      3570292.72     10241053.36
      3570409.91     10240925.76      3570472.41     10240811.17
      3570482.82     10240709.61      3570421.79     10240613.64
      3570347.53     10240534.14      3570343.47     10240421.78
      3570375.25      10240374.2      3570384.94      10240322.8
      3570425.96     10240243.89      3570498.41     10240210.28
      3570546.99      10240011.6      3570546.13     10239964.15
      3570638.73     10239903.97      3570666.94     10239864.94
      3570668.26     10239766.44      3570656.39     10239722.44
      3570708.87     10239640.26      3570722.35     10239574.86
      3570686.08     10239489.98      3570677.72     10239433.16
      3570644.75      10239377.3      3570732.11     10239341.64

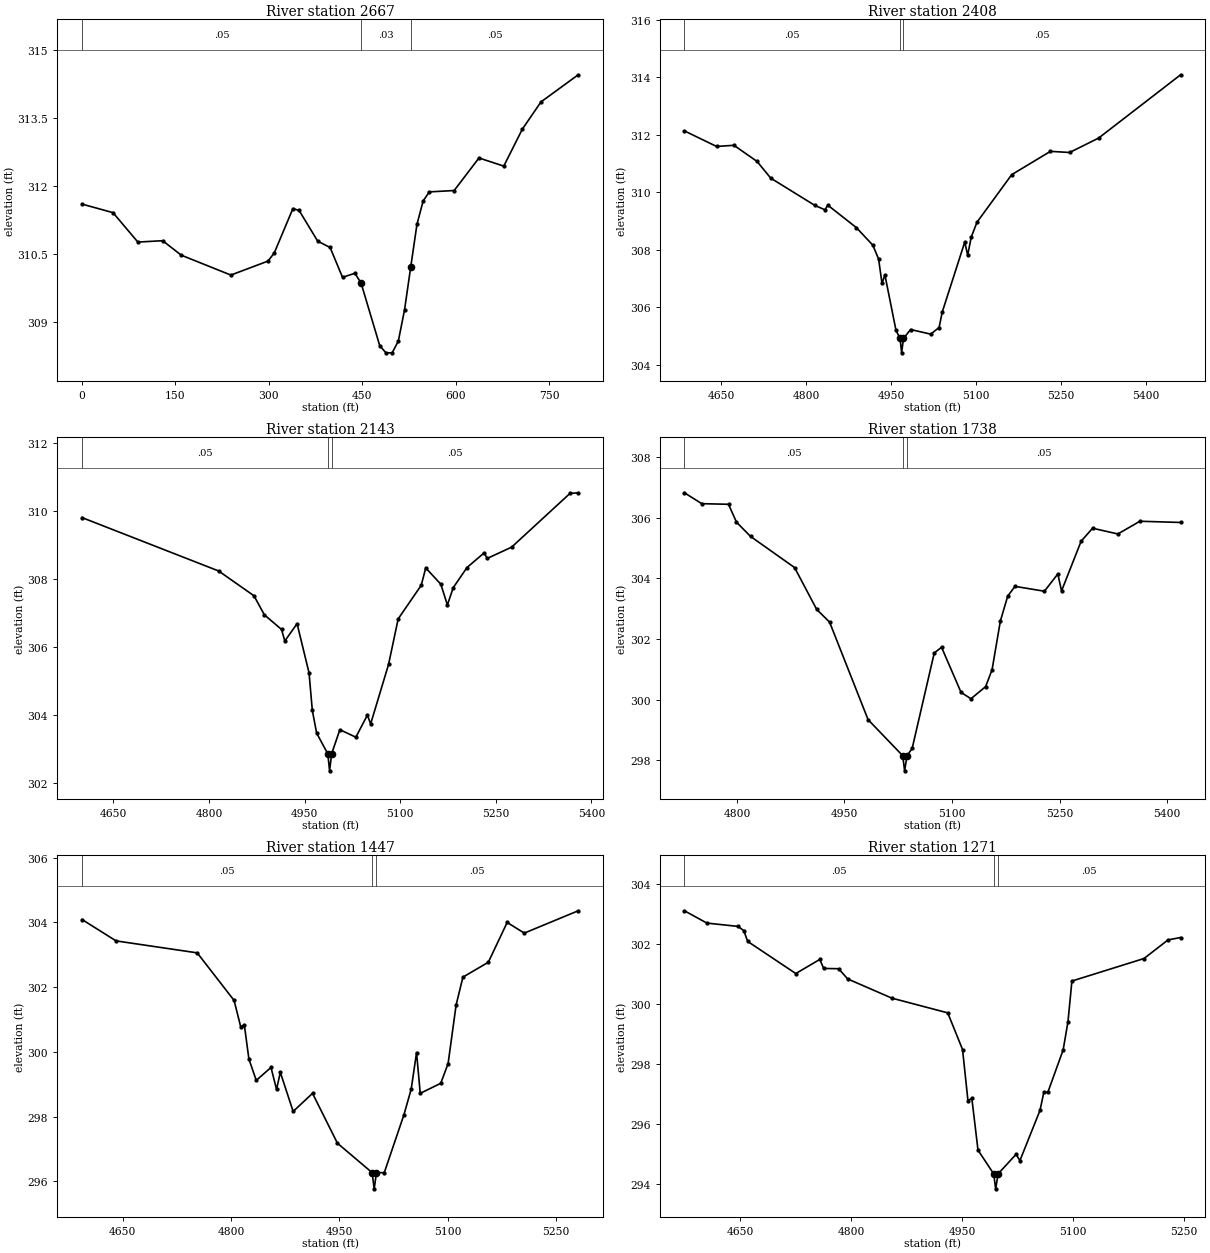
Type RM Length L Ch R = 1 ,2667    ,259,259,259
XS GIS Cut Line= 3
     3570401.193    10241613.466     3570066.991    10241611.729
     3569691.123    10241347.841
#Sta/Elev= 30
       0   311.6   49.79  311.41   89.61  310.76  129.44  310.79  159.31  310.47
  238.97  310.03  298.71  310.34  308.67  310.52  338.54   311.5   348.5  311.46
  378.38  310.78   398.3  310.64  418.22  309.98  438.14  310.07   448.1  309.85
  477.97  308.47  487.93  308.31  497.89  308.31  507.85  308.57  517.81  309.26
  527.77  310.21  537.73  311.15  547.69  311.67  557.65  311.87  597.49   311.9
  637.32  312.62  677.16  312.44  707.04  313.26  736.92  313.86  796.67  314.46
#Mann= 3 , 0 , 0
       0     .05       0   448.1     .03       0  527.77     .05       0
Bank Sta=448.1,527.77
XS Rating Curve= 0 ,0
Exp/Cntr=0.3,0.1

Type RM Length L Ch R = 1 ,2408    ,265,265,265
BEGIN DESCRIPTION:
UNT05243 IN WICK 5.0
END DESCRIPTION:
XS GIS Cut Line= 2
      3570547.63     10241436.96      3569690.34     10241260.81
#Sta/Elev= 30
  4585.4  312.13  4642.1  311.59  4672.7  311.63  4713.5  311.07  4737.6  310.49
  4815.6  309.54  4833.2  309.39  4838.3  309.55  4888.7  308.77  4917.7  308.16
  4927.9  307.68  4933.9  306.83    4939  307.13  4958.6   305.2  4965.8  304.92
  4968.5  304.42  4971.8  304.92  4984.3  305.23  5019.8  305.07  5034.6   305.3
  5040.2  305.84  5079.9  308.27    5085  307.81  5091.3  308.44  5101.5  308.96
  5162.7  310.61    5231  311.42  5264.8  311.38  5315.9  311.88  5460.6  314.08
#Mann= 3 ,-1 , 0
  4585.4     .05       0  4965.8     .03       0  4971.8     .05       0
Bank Sta=4965.8,4971.8
XS Rating Curve= 0 ,0
Exp/Cntr=0.3,0.1

Type RM Length L Ch R = 1 ,2143    ,405,405,405
BEGIN DESCRIPTION:
UNT05243 IN WICK 4.0
END DESCRIPTION:
XS GIS Cut Line= 2
      3570651.07     10241205.92      3569891.93     10241034.32
#Sta/Elev= 30
    4601  309.82  4815.2  308.25  4870.7  307.52    4887  306.96  4913.9  306.53
  4919.1  306.19  4938.3   306.7  4957.1  305.25  4962.2  304.15    4969  303.48
  4986.5  302.87  4989.3  302.37  4992.5  302.87  5005.4  303.58  5030.5  303.36
  5048.6  304.01  5053.7  303.75  5081.8   305.5  5096.9  306.84  5133.1  307.83
  5140.1  308.34  5163.8  307.86  5174.1  307.25  5183.3  307.76  5204.8  308.35
  5231.6  308.78  5236.7  308.62  5274.8  308.95  5366.3  310.53  5379.3  310.55
#Mann= 3 ,-1 , 0
    4601     .05       0  4986.5     .03       0  4992.5     .05       0
Bank Sta=4986.5,4992.5
XS Rating Curve= 0 ,0
Exp/Cntr=0.3,0.1

Type RM Length L Ch R = 1 ,1738    ,291,291,291
BEGIN DESCRIPTION:
UNT05243 IN WICK 3.0
END DESCRIPTION:
XS GIS Cut Line= 2
      3570742.08     10240841.64      3570066.73     10240689.83
#Sta/Elev= 30
  4726.7  306.83  4750.9  306.47  4788.2  306.45  4799.3  305.86  4818.9  305.39
  4880.4  304.36  4911.2  302.98  4929.2  302.56  4982.9  299.34  5031.2  298.15
  5033.9  297.65  5037.2  298.15  5044.4  298.39  5075.2  301.54  5085.4  301.73
  5112.6  300.24  5126.4  300.03  5146.9  300.43  5155.9  300.99  5167.4  302.59
  5177.7  303.42  5187.9  303.74  5228.9  303.58  5247.6  304.15  5252.8  303.59
  5280.1  305.23  5296.1  305.66  5331.4  305.47  5362.1  305.89  5418.9  305.85
#Mann= 3 ,-1 , 0
  4726.7     .05       0  5031.2     .03       0  5037.2     .05       0
Bank Sta=5031.2,5037.2
XS Rating Curve= 0 ,0
Exp/Cntr=0.3,0.1

Type RM Length L Ch R = 1 ,1447    ,176,176,176
BEGIN DESCRIPTION:
Mapping XS 0fc4a1de
END DESCRIPTION:
XS GIS Cut Line= 2
      3570748.19     10240622.89      3570075.84      10240480.8
#Sta/Elev= 30
  4593.5  304.09  4640.6  303.43    4753  303.06  4804.1  301.59  4813.2  300.78
  4818.3  300.83  4824.6  299.78  4834.8  299.12  4855.2  299.52  4862.9  298.84
  4868.1  299.37  4885.9  298.16  4912.7  298.72  4947.2  297.18  4995.3  296.27
  4998.1  295.77  5001.3  296.27  5012.1  296.27  5039.2  298.05  5049.4  298.85
  5056.8  299.98  5061.9  298.72  5090.3  299.03  5100.5  299.64  5111.6  301.45
    5121  302.31  5156.2  302.77  5182.3     304    5206  303.67  5280.7  304.36
#Mann= 3 ,-1 , 0
  4593.5     .05       0  4995.3     .03       0  5001.3     .05       0
Bank Sta=4995.3,5001.3
XS Rating Curve= 0 ,0
Exp/Cntr=0.3,0.1

Type RM Length L Ch R = 1 ,1271    ,279,279,279
BEGIN DESCRIPTION:
Mapping XS acb91f63
END DESCRIPTION:
XS GIS Cut Line= 2
      3570781.15     10240501.35      3570140.54     10240301.71
#Sta/Elev= 30
  4574.5   303.1  4604.9  302.69  4646.8  302.58  4654.8  302.44    4660  302.08
  4725.1  301.01  4757.6  301.48  4762.8  301.18    4783  301.17  4795.3  300.83
  4855.1  300.19  4930.6   299.7  4950.6  298.48  4957.9  296.78  4963.2  296.85
  4971.5  295.13  4992.7  294.34  4995.4  293.84  4998.7  294.34    5023  294.99
  5028.2  294.78  5055.3  296.45  5060.7  297.07  5065.9  297.05  5086.7  298.47
  5093.2  299.41  5098.5  300.76    5196  301.51  5228.5  302.13  5245.5  302.21
#Mann= 3 ,-1 , 0
  4574.5     .05       0  4992.7     .03       0  4998.7     .05       0
Bank Sta=4992.7,4998.7
XS Rating Curve= 0 ,0
Exp/Cntr=0.3,0.1

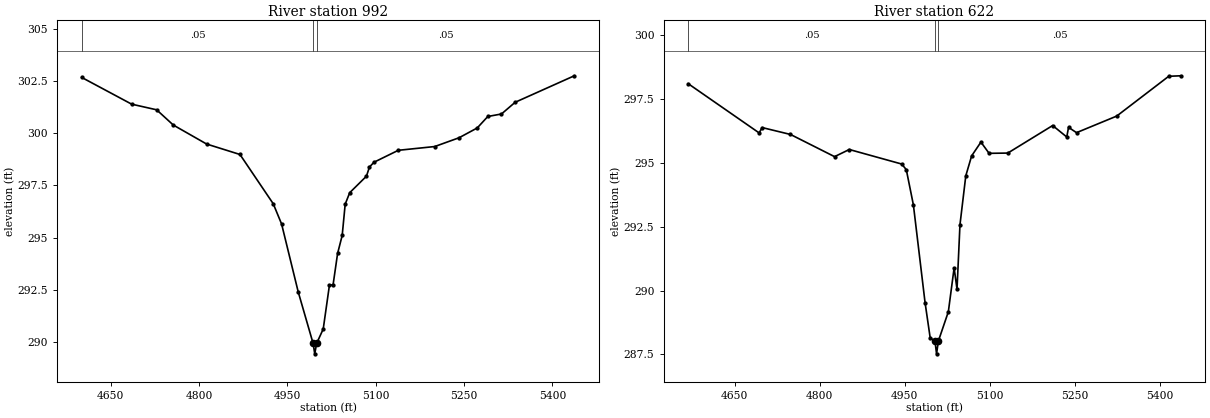
Type RM Length L Ch R = 1 ,992     ,370,370,370
BEGIN DESCRIPTION:
UNT05243 IN WICK 2.0
END DESCRIPTION:
XS GIS Cut Line= 3
      3570792.07     10240441.61      3570492.11     10240141.64
      3570092.13     10240241.64
#Sta/Elev= 30
  4600.8  302.67  4685.6  301.39    4728  301.12  4756.3  300.39  4812.9  299.48
  4869.5  298.98    4926  296.62  4940.2  295.65  4968.4   292.4  4993.7  289.93
  4996.5  289.43  4999.7  289.93  5010.9  290.62  5021.5  292.73  5027.6  292.73
  5035.3  294.24  5043.1   295.1  5048.2   296.6  5055.9  297.15  5084.3  297.94
  5089.4  298.38  5097.2  298.61  5138.4  299.18  5200.2  299.36  5241.5  299.78
  5272.4  300.25  5290.4   300.8  5313.6  300.92  5336.8  301.48  5437.3  302.75
#Mann= 3 ,-1 , 0
  4600.8     .05       0  4993.7     .03       0  4999.7     .05       0
Bank Sta=4993.7,4999.7
XS Rating Curve= 0 ,0
Exp/Cntr=0.3,0.1

Type RM Length L Ch R = 1 ,622     ,0,0,0
BEGIN DESCRIPTION:
UNT05243 IN WICK 1.0
END DESCRIPTION:
XS GIS Cut Line= 4
      3570940.97     10240123.48      3570858.34     10239901.54
      3570441.67     10239802.58      3570292.11     10239941.64
#Sta/Elev= 30
    4568  298.11  4693.2  296.18  4698.5  296.39  4748.5  296.12  4826.3  295.25
  4852.3  295.53  4944.8  294.96  4952.9  294.74  4965.4  293.36    4986  289.53
  4995.1  288.14  5003.5  288.02  5006.3  287.52  5009.5  288.02  5027.1  289.17
  5037.3  290.89  5042.4  290.05  5047.6  292.58  5057.9   294.5  5068.2  295.28
  5084.6  295.82    5099  295.38    5132  295.39  5211.2  296.47  5236.1  296.02
  5239.2   296.4  5253.3  296.19  5324.2  296.84    5416   298.4  5437.3  298.42
#Mann= 3 ,-1 , 0
    4568     .05       0  5003.5     .03       0  5009.5     .05       0
Bank Sta=5003.5,5009.5
XS Rating Curve= 0 ,0
Exp/Cntr=0.3,0.1

Chan Stop Cuts=-1
Use User Specified Reach Order=0
Composite Channel Slope=5