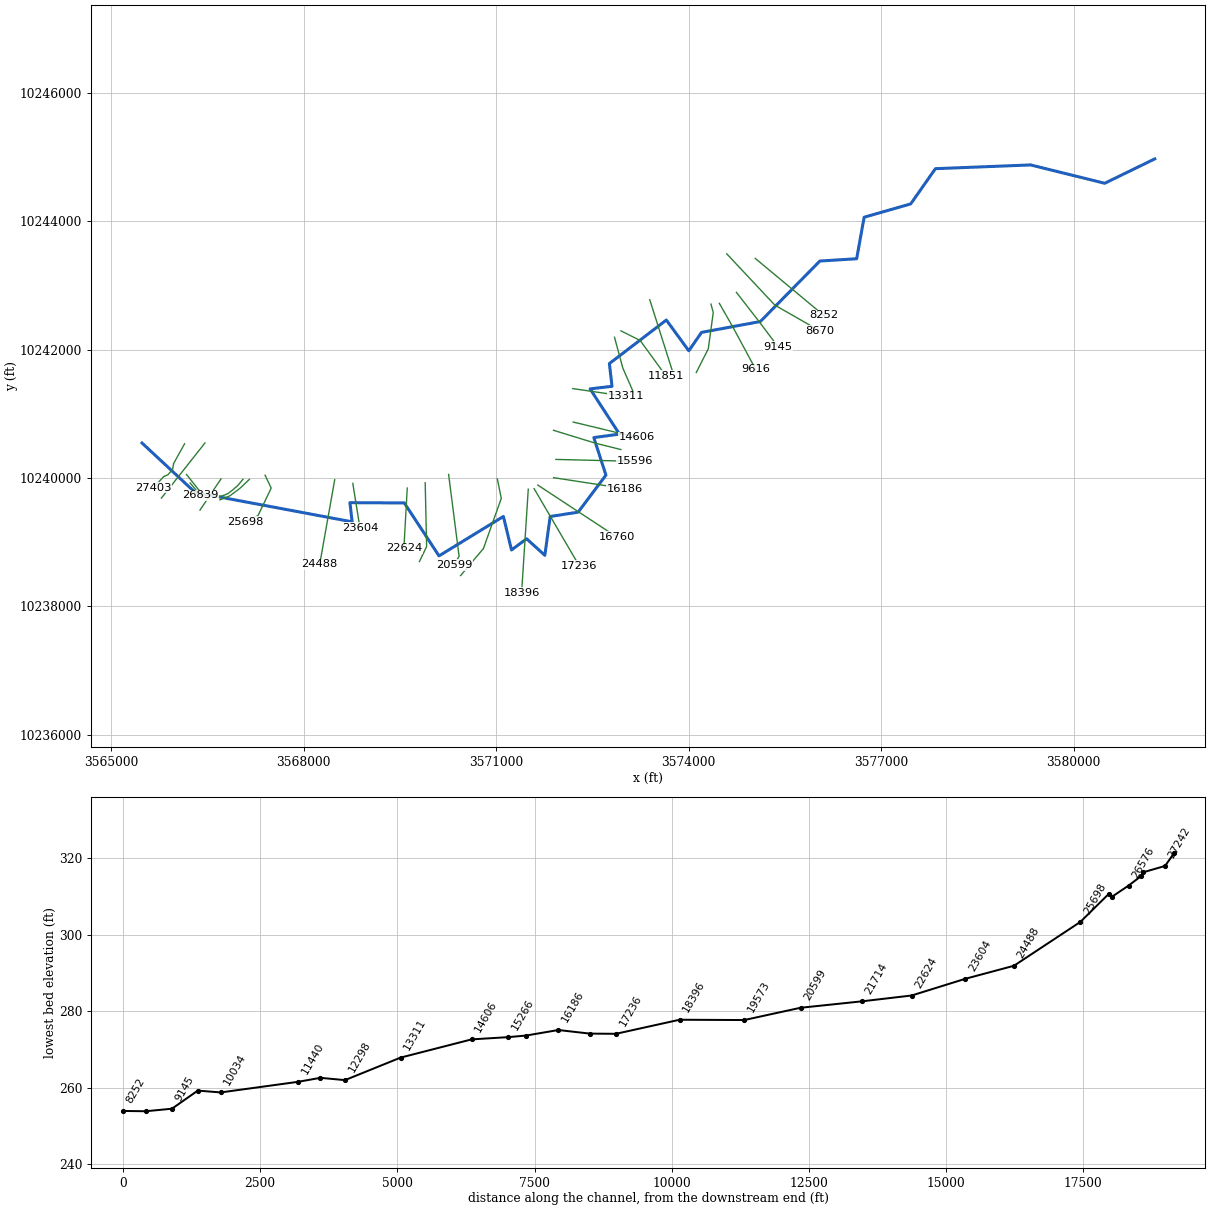
--- STEEP HOLLOW BRANCH.prj (project) ---

Proj Title=STEEP HOLLOW BRANCH Base Level Engineering
Current Plan=p01
Default Exp/Contr=0.3,0.1
English Units
Geom File=g01
Flow File=f01
Plan File=p01
Y Axis Title=Elevation
X Axis Title(PF)=Main Channel Distance
X Axis Title(XS)=Station
BEGIN DESCRIPTION:
STEEP HOLLOW BRANCH
END DESCRIPTION:
DSS Export Rating Curves= 0
DSS Export Rating Curve Sorted= 0
DSS Export Volume Flow Curves= 0
DXF OffsetX= 0
DXF OffsetY= 0
DXF ScaleX= 1
DXF ScaleY= 10

--- STEEP HOLLOW BRANCH.p01 (plan) ---

Plan Title=Multiple Run
Short Identifier=Multiple
Geom File=g01
Flow File=f01
Subcritical Flow
K Sum by GR= 0
Std Step Tol= 0.01
Critical Tol= 0.01
Num of Std Step Trials= 20
Max Error Tol= 0.3
Flow Tol Ratio= 0.001
Split Flow NTrial= 30
Split Flow Tol= 0.02
Split Flow Ratio= 0.02
Log Output Level= 0
Friction Slope Method= 1
Unsteady Friction Slope Method= 2
Unsteady Bridges Friction Slope Method= 1
Parabolic Critical Depth
Global Vel Dist=  1 , 1 , 1
Global Log Level= 0
CheckData=True
Encroach Param= -1, 0, 0, 0
BEGIN DESCRIPTION:
Multiple Run
END DESCRIPTION:

--- STEEP HOLLOW BRANCH.f01 (steady flow) ---

Flow Title=Multiple
Program Version=4.10
Number of Profiles= 7
Profile Names=10-year,25-year,50-year,1pct_min,100-year,1pct_plu,500-year
River Rch & RM=STEEP HOLLOW BRA,Reach-1         ,27403
     157     197     223     188     254     344     331
River Rch & RM=STEEP HOLLOW BRA,Reach-1         ,24488
     524     702     845     747    1010    1366    1445
River Rch & RM=STEEP HOLLOW BRA,Reach-1         ,22624
     653     882    1068     948    1282    1734    1851
River Rch & RM=STEEP HOLLOW BRA,Reach-1         ,19573
     697     944    1145    1017    1376    1861    1991
River Rch & RM=STEEP HOLLOW BRA,Reach-1         ,18396
     823    1122    1367    1218    1647    2228    2400
River Rch & RM=STEEP HOLLOW BRA,Reach-1         ,12298
     872    1190    1451    1294    1750    2367    2553
River Rch & RM=STEEP HOLLOW BRA,Reach-1         ,11851
     905    1236    1508    1346    1820    2461    2656
River Rch & RM=STEEP HOLLOW BRA,Reach-1         ,10034
     960    1317    1611    1441    1949    2636    2860
River Rch & RM=STEEP HOLLOW BRA,Reach-1         ,9616
    1016    1394    1707    1528    2066    2794    3034
River Rch & RM=STEEP HOLLOW BRA,Reach-1         ,7125
    1062    1458    1785    1596    2159    2919    3166
Boundary for River Rch & Prof#=STEEP HOLLOW BRA,Reach-1         , 1
Up Type= 0
Dn Type= 3
Dn Slope=0.005
Boundary for River Rch & Prof#=STEEP HOLLOW BRA,Reach-1         , 2
Up Type= 0
Dn Type= 3
Dn Slope=0.005
Boundary for River Rch & Prof#=STEEP HOLLOW BRA,Reach-1         , 3
Up Type= 0
Dn Type= 3
Dn Slope=0.005
Boundary for River Rch & Prof#=STEEP HOLLOW BRA,Reach-1         , 4
Up Type= 0
Dn Type= 3
Dn Slope=0.005
Boundary for River Rch & Prof#=STEEP HOLLOW BRA,Reach-1         , 5
Up Type= 0
Dn Type= 3
Dn Slope=0.005
Boundary for River Rch & Prof#=STEEP HOLLOW BRA,Reach-1         , 6
Up Type= 0
Dn Type= 3
Dn Slope=0.005
Boundary for River Rch & Prof#=STEEP HOLLOW BRA,Reach-1         , 7
Up Type= 0
Dn Type= 3
Dn Slope=0.005
DSS Import GetInterval= 0
DSS Import GetPeak= 0
DSS Import FillOption= 0

--- STEEP HOLLOW BRANCH.g01 (geometry) ---

Geom Title=Existing Conditions
Program Version=4.10

River Reach=STEEP HOLLOW BRA,Reach-1
Reach XY= 30
      3565479.29     10240543.12      3566306.61     10239773.07
      3568753.41      10239315.5      3568718.64     10239613.98
      3569566.99     10239609.45      3570107.04     10238784.71
      3571110.88     10239398.63      3571236.98     10238876.65
      3571471.75     10239051.29      3571756.42     10238793.64
      3571839.49     10239398.18      3572275.05     10239466.05
      3572708.74     10240043.03      3572519.66     10240628.07
      3572919.33     10240682.58      3572461.82     10241387.11
      3572803.14     10241427.45      3572762.45     10241781.86
      3573650.28     10242460.05      3573999.89     10241980.84
      3574198.47      10242267.6      3575114.69     10242436.85
      3576042.53     10243379.84      3576615.93     10243415.24
      3576732.84     10244062.39      3577458.61     10244270.19
      3577843.45     10244819.08      3579327.03     10244877.31
      3580481.95     10244591.68      3581262.11     10244971.64

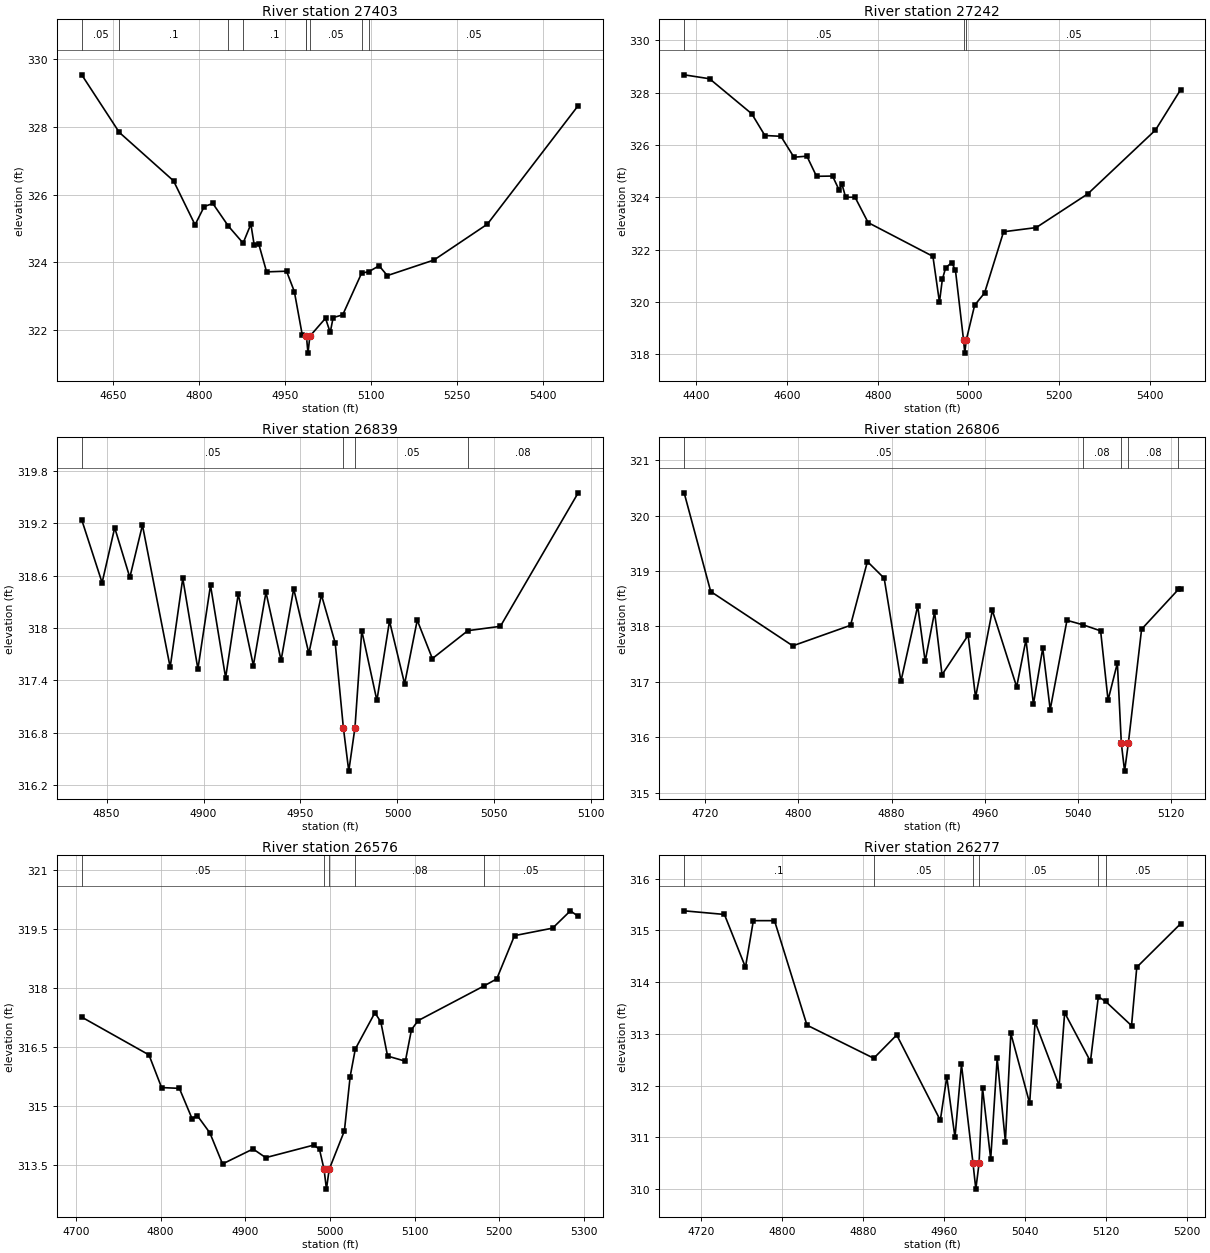
Type RM Length L Ch R = 1 ,27403   ,161,161,161
BEGIN DESCRIPTION:
Mapping XS e17b103b
END DESCRIPTION:
XS GIS Cut Line= 6
      3566141.62     10240531.76      3565969.73     10240220.97
      3565955.84     10240132.43      3565882.92     10240049.09
      3565817.84     10240021.45      3565654.87     10239845.43
#Sta/Elev= 30
  4594.7  329.54  4660.2  327.84  4754.8  326.41  4792.4  325.11  4808.4  325.65
  4823.4  325.74  4850.6  325.07  4876.2  324.57  4889.8  325.13  4895.5  324.52
  4903.4  324.55  4917.2  323.72    4952  323.74  4965.6  323.14  4979.5  321.85
  4985.7  321.82  4986.7  321.82  4989.4  321.32  4992.7  321.82    5020  322.35
  5028.2  321.93  5033.3  322.37    5050  322.45  5082.9  323.68  5095.9  323.73
  5113.5   323.9  5127.8  323.61  5209.2  324.07  5302.4  325.13  5460.8  328.63
#Mann= 9 ,-1 , 0
  4594.7     .05       0  4660.2      .1       0  4850.6     .05       0
  4876.2      .1       0  4985.7     .05       0  4986.7     .04       0
  4992.7     .05       0  5082.9      .1       0  5095.9     .05       0
Bank Sta=4986.7,4992.7
XS Rating Curve= 0 ,0
Exp/Cntr=0.3,0.1

Type RM Length L Ch R = 1 ,27242   ,403,403,403
BEGIN DESCRIPTION:
STEEP HOLLOW BRANCH 42.0
END DESCRIPTION:
XS GIS Cut Line= 2
      3566459.23     10240543.91      3565781.01     10239685.52
#Sta/Elev= 30
  4373.5  328.68  4429.5  328.53  4522.5  327.19  4551.4  326.36  4586.7  326.33
  4615.5  325.53    4644  325.57  4665.2   324.8  4700.5  324.81  4714.9  324.28
  4721.3   324.5  4729.3     324  4750.1     324    4779  323.03  4921.7  321.74
  4936.1  319.99  4942.5  320.86  4949.9  321.31  4963.3   321.5  4971.4   321.2
  4989.2  318.54  4991.9  318.04  4995.2  318.54  5013.6  319.87  5035.5  320.34
  5077.4  322.68  5149.3  322.84  5263.1  324.13  5412.2  326.57  5467.5  328.11
#Mann= 3 ,-1 , 0
  4373.5     .05       0  4989.2     .04       0  4995.2     .05       0
Bank Sta=4989.2,4995.2
XS Rating Curve= 0 ,0
Exp/Cntr=0.3,0.1

Type RM Length L Ch R = 1 ,26839   ,33,33,33
BEGIN DESCRIPTION:
Mapping XS 6327c7ff
END DESCRIPTION:
XS GIS Cut Line= 2
      3566227.65     10239921.44      3566392.89     10239725.92
#Sta/Elev= 30
  4837.2  319.24  4847.7  318.52  4854.2  319.15    4862  318.58  4868.5  319.18
  4882.8  317.55  4889.3  318.57  4897.1  317.53  4903.6  318.49  4911.4  317.43
  4917.9  318.39  4925.7  317.57  4932.2  318.41    4940  317.63  4946.5  318.45
  4954.3  317.71  4960.8  318.38  4967.9  317.83  4972.1  316.86  4974.9  316.36
  4978.1  316.86  4981.6  317.97  4989.4  317.17  4995.9  318.08  5003.7  317.36
  5010.2  318.09    5018  317.65  5036.3  317.97  5053.1  318.02  5093.2  319.55
#Mann= 4 ,-1 , 0
  4837.2     .05       0  4972.1     .04       0  4978.1     .05       0
  5036.3     .08       0
Bank Sta=4972.1,4978.1
XS Rating Curve= 0 ,0
Exp/Cntr=0.3,0.1

Type RM Length L Ch R = 1 ,26806   ,230,230,230
BEGIN DESCRIPTION:
Mapping XS eb6a6823
END DESCRIPTION:
XS GIS Cut Line= 2
      3566172.08     10240053.41      3566437.01      10239719.3
#Sta/Elev= 30
  4701.8  320.41  4724.6  318.63  4795.1  317.65  4844.7  318.02  4859.2  319.17
  4873.6  318.87    4888  317.01  4902.4  318.37  4908.8  317.37  4916.9  318.26
  4923.3  317.13  4945.7  317.84  4952.1  316.72  4966.5  318.29  4987.4  316.91
  4995.4  317.76  5001.8   316.6  5009.8  317.61  5016.2   316.5  5030.6  318.11
  5044.3  318.03  5059.5  317.92  5065.9  316.67  5073.9  317.34  5077.3  315.89
  5080.1  315.39  5083.3  315.89  5094.7  317.95  5126.4  318.67  5128.2  318.67
#Mann= 5 ,-1 , 0
  4701.8     .05       0  5044.3     .08       0  5077.3     .04       0
  5083.3     .08       0  5126.4     .05       0
Bank Sta=5077.3,5083.3
XS Rating Curve= 0 ,0
Exp/Cntr=0.3,0.1

Type RM Length L Ch R = 1 ,26576   ,299,299,299
BEGIN DESCRIPTION:
STEEP HOLLOW BRANCH 41.0
END DESCRIPTION:
XS GIS Cut Line= 2
      3566710.08     10239984.51      3566382.36     10239498.35
#Sta/Elev= 30
  4706.9  317.26  4786.3   316.3  4801.2  315.47  4822.2  315.45  4837.2  314.68
  4843.3  314.76  4858.2  314.32  4873.2  313.53  4909.2  313.91  4924.2  313.69
  4981.1  314.01  4987.7   313.9  4993.1  313.39  4995.9  312.89  4999.1  313.39
  5017.1  314.37  5023.9  315.75    5030  316.45  5053.1  317.37  5060.1  317.14
  5068.1  316.27  5089.1  316.14  5096.3  316.94  5104.1  317.17  5181.8  318.05
    5197  318.23    5218  319.33    5263  319.52    5284  319.96  5293.2  319.82
#Mann= 5 ,-1 , 0
  4706.9     .05       0  4993.1     .03       0  4999.1     .05       0
    5030     .08       0  5181.8     .05       0
Bank Sta=4993.1,4999.1
XS Rating Curve= 0 ,0
Exp/Cntr=0.3,0.1

Type RM Length L Ch R = 1 ,26277   ,55,55,55
BEGIN DESCRIPTION:
Mapping XS 269c0cd1
END DESCRIPTION:
XS GIS Cut Line= 6
      3567051.89       10239978.      3566972.65     10239882.48
      3566891.27     10239811.95      3566818.57     10239755.53
      3566756.72     10239729.49      3566660.12     10239704.52
#Sta/Elev= 30
  4703.1  315.38  4742.9  315.31  4763.7  314.29  4771.5  315.19  4792.4  315.19
  4824.5  313.17  4890.5  312.53  4913.2  312.98  4956.3  311.33  4962.7  312.17
  4970.8     311  4977.2  312.41  4988.6   310.5  4991.4     310  4994.6   310.5
    4998  311.96  5006.1  310.58  5012.5  312.53  5020.6  310.92    5026  313.01
  5044.6  311.66    5050  313.23  5073.8     312  5079.2  313.41  5104.7  312.47
  5112.5  313.72  5119.6  313.63  5145.3  313.16  5150.5  314.29  5193.8  315.13
#Mann= 6 ,-1 , 0
  4703.1      .1       0  4890.5     .05       0  4988.6     .04       0
  4994.6     .05       0  5112.5      .1       0  5119.6     .05       0
Bank Sta=4988.6,4994.6
XS Rating Curve= 0 ,0
Exp/Cntr=0.3,0.1

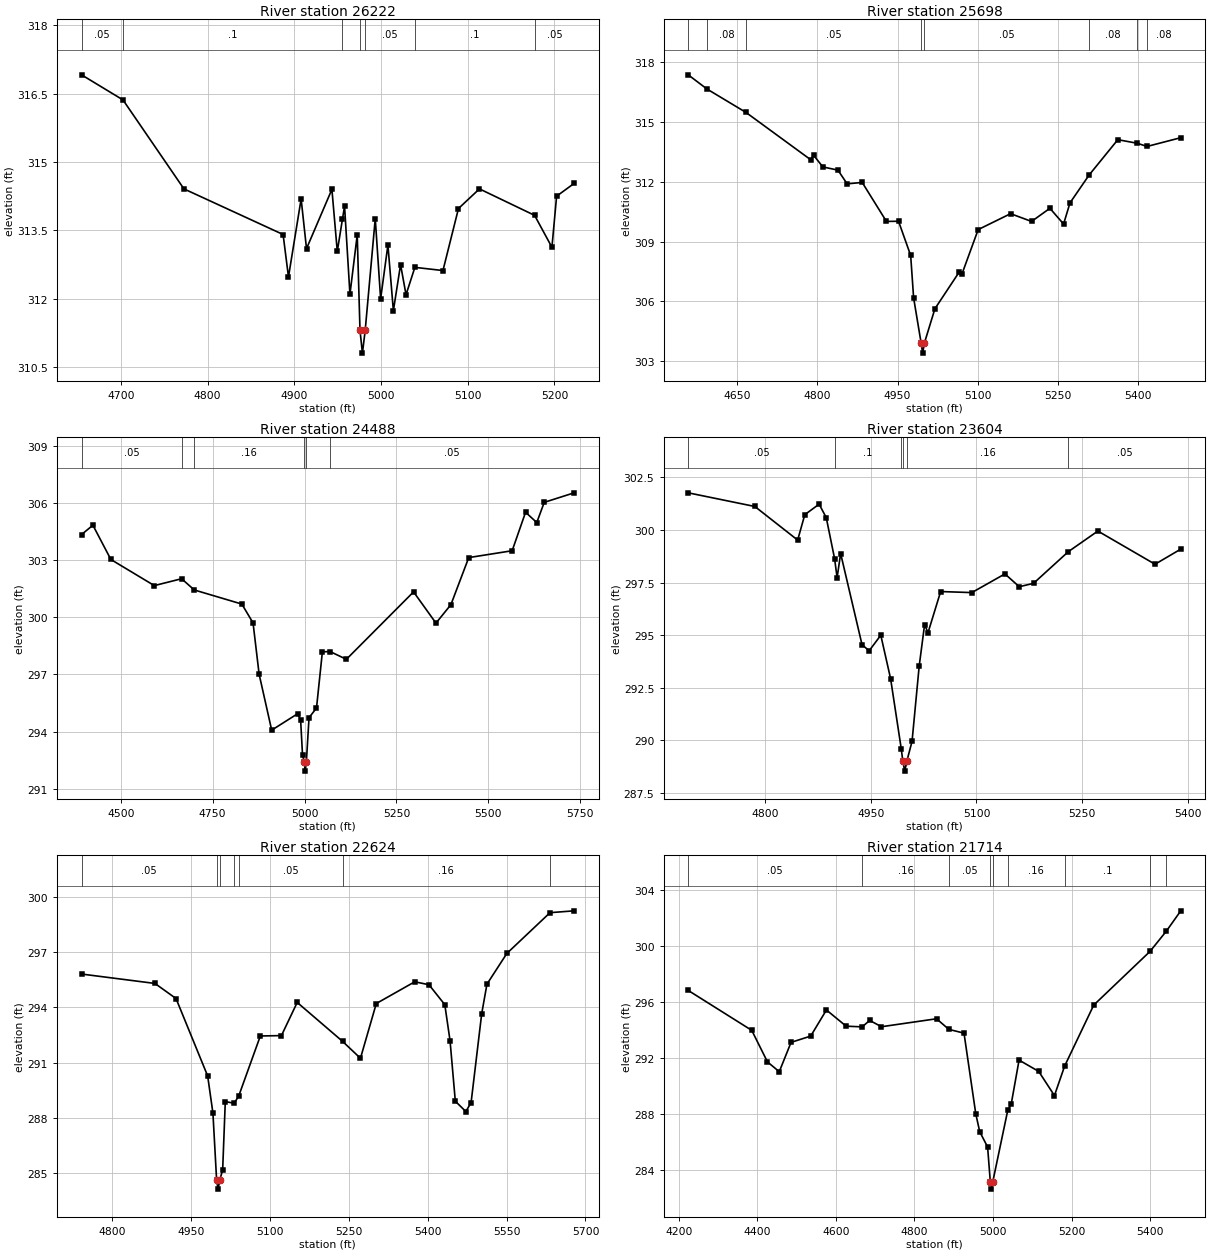
Type RM Length L Ch R = 1 ,26222   ,524,524,524
BEGIN DESCRIPTION:
Mapping XS 3c774b6a
END DESCRIPTION:
XS GIS Cut Line= 4
      3567152.74     10239977.94      3567007.37     10239839.08
      3566846.78     10239719.72      3566691.57     10239657.85
#Sta/Elev= 30
  4654.5  316.91  4702.3  316.36  4772.6  314.41    4887  313.41  4893.2  312.48
  4907.8  314.19    4914   313.1  4943.3   314.4  4949.5  313.04  4955.4  313.74
  4957.9  314.03  4964.1   312.1  4972.5   313.4  4975.7  311.31  4978.5  310.81
  4981.7  311.31  4993.3  313.76  4999.5     312  5007.9  313.18  5014.2  311.74
  5022.5  312.75  5028.8  312.09    5039  312.69  5071.4  312.62  5089.3  313.98
  5113.5  314.41  5177.1  313.83  5197.1  313.13  5202.5  314.25  5222.7  314.53
#Mann= 7 ,-1 , 0
  4654.5     .05       0  4702.3      .1       0  4955.4     .05       0
  4975.7     .04       0  4981.7     .05       0    5039      .1       0
  5177.1     .05       0
Bank Sta=4975.7,4981.7
XS Rating Curve= 0 ,0
Exp/Cntr=0.3,0.1

Type RM Length L Ch R = 1 ,25698   ,1210,1210,1210
BEGIN DESCRIPTION:
STEEP HOLLOW BRANCH 40.0
END DESCRIPTION:
XS GIS Cut Line= 4
      3567396.75     10240040.49      3567492.11     10239841.64
       3567286.3     10239412.29      3567085.71     10239312.03
#Sta/Elev= 30
  4558.6  317.38  4593.5  316.67  4666.6  315.49  4787.7  313.11  4793.2  313.33
  4810.3  312.75  4838.5  312.59  4855.7   311.9  4883.9  311.97  4929.2  310.01
  4951.8  310.02  4974.5   308.3    4980  306.17  4994.1  303.89  4996.9  303.39
  5000.1  303.89  5019.8  305.62  5065.1  307.46  5070.7  307.39  5100.7   309.6
  5161.3   310.4  5200.5  310.01  5234.8  310.67  5260.4  309.88  5272.3  310.94
  5308.3  312.35  5361.8  314.12  5398.1  313.94  5416.5  313.78  5479.5  314.22
#Mann= 8 ,-1 , 0
  4558.6     .05       0  4593.5     .08       0  4666.6     .05       0
  4994.1     .04       0  5000.1     .05       0  5308.3     .08       0
  5398.1      .1       0  5416.5     .08       0
Bank Sta=4994.1,5000.1
XS Rating Curve= 0 ,0
Exp/Cntr=0.3,0.1

Type RM Length L Ch R = 1 ,24488   ,884,884,884
BEGIN DESCRIPTION:
STEEP HOLLOW BRANCH 39.0
END DESCRIPTION:
XS GIS Cut Line= 2
      3568481.83     10239971.01      3568247.45     10238651.56
#Sta/Elev= 30
  4393.3  304.34  4424.2  304.83  4473.1  303.03  4591.3  301.66  4665.5  302.02
  4700.1  301.43  4829.4  300.69  4859.9   299.7  4876.4  297.01  4910.6  294.07
  4981.7  294.94  4989.4  294.58  4994.5  292.76    4999  292.42  5001.8  291.92
    5005  292.42  5012.2  294.73  5032.5  295.23  5048.5  298.18  5069.1   298.2
  5113.8  297.79  5296.6  301.33  5357.5  299.69  5398.2  300.66  5446.7  303.13
  5564.8  303.49  5601.3  305.51  5631.8  304.97  5652.1  306.03  5733.4  306.53
#Mann= 6 ,-1 , 0
  4393.3     .05       0  4665.5      .1       0  4700.1     .16       0
    4999     .07       0    5005     .16       0  5069.1     .05       0
Bank Sta=4999,5005
XS Rating Curve= 0 ,0
Exp/Cntr=0.3,0.1

Type RM Length L Ch R = 1 ,23604   ,980,980,980
BEGIN DESCRIPTION:
Mapping XS d0f7cd49
END DESCRIPTION:
XS GIS Cut Line= 2
      3568763.68     10239914.81      3568874.21     10239225.61
#Sta/Elev= 30
  4691.5  301.77  4785.9  301.12  4846.6  299.52  4856.7  300.73    4877  301.23
  4887.1  300.59  4898.9  298.64  4902.5  297.73  4907.5  298.88  4937.8  294.54
  4947.9  294.25  4964.4  294.99  4978.3  292.92  4993.5  289.56  4995.5  289.02
  4998.3  288.52  5001.5  289.02  5008.7  289.94  5018.8  293.52  5026.4  295.48
  5031.4  295.12  5049.2  297.07  5093.4  297.02  5140.3  297.91  5160.6   297.3
  5180.8  297.46  5230.2  298.97    5272  299.95    5353  298.37  5389.5  299.09
#Mann= 6 ,-1 , 0
  4691.5     .05       0  4898.9      .1       0  4993.5     .16       0
  4995.5     .07       0  5001.5     .16       0  5230.2     .05       0
Bank Sta=4995.5,5001.5
XS Rating Curve= 0 ,0
Exp/Cntr=0.3,0.1

Type RM Length L Ch R = 1 ,22624   ,910,910,910
BEGIN DESCRIPTION:
Mapping XS a54a46e3
END DESCRIPTION:
XS GIS Cut Line= 2
      3569612.21     10239840.95      3569560.15     10238906.19
#Sta/Elev= 30
  4742.2  295.81  4881.7   295.3  4921.8  294.48  4981.9  290.28  4991.9  288.27
  4998.9  284.64  5001.7  284.14  5004.9  284.64  5010.4  285.18  5015.4  288.89
  5032.3   288.8  5040.9  289.19    5082  292.45  5122.1  292.47  5152.1  294.27
  5238.2  292.16  5272.3  291.24  5302.4  294.21  5375.5  295.39  5402.5  295.23
  5432.6  294.15  5442.6  292.19  5452.6  288.91  5472.6  288.35  5482.6  288.84
  5502.7  293.65  5512.7  295.26  5550.6  296.93  5632.6  299.14  5678.4  299.24
#Mann= 7 ,-1 , 0
  4742.2     .05       0  4998.9     .03       0  5004.9     .05       0
  5032.3     .16       0  5040.9     .05       0  5238.2     .16       0
  5632.6     .05       0
Bank Sta=4998.9,5004.9
XS Rating Curve= 0 ,0
Exp/Cntr=0.3,0.1

Type RM Length L Ch R = 1 ,21714   ,1115,1115,1115
BEGIN DESCRIPTION:
STEEP HOLLOW BRANCH 36.0
END DESCRIPTION:
XS GIS Cut Line= 3
      3569892.11      10239923.3      3569914.12     10238929.36
      3569801.67      10238695.8
#Sta/Elev= 30
  4224.3  296.84    4386  293.98    4426  291.72    4456  291.02    4486  293.12
    4536  293.57    4576  295.44  4626.1  294.28  4666.9  294.23  4686.1  294.69
  4716.1  294.24  4856.1  294.81  4887.6  294.05  4926.1  293.78  4956.1  287.99
  4966.1  286.72  4986.1  285.63  4993.1  283.11  4995.9  282.61  4999.1  283.11
  5037.5  288.27  5046.2   288.7  5066.2  291.85  5116.2  291.04  5156.2  289.31
  5182.1  291.42  5256.2  295.79  5399.6  299.64  5440.8  301.08  5477.7  302.54
#Mann= 9 ,-1 , 0
  4224.3     .05       0  4666.9     .16       0  4887.6     .05       0
  4993.1    .035       0  4999.1     .05       0  5037.5     .16       0
  5182.1      .1       0  5399.6     .05       0  5440.8      .1       0
Bank Sta=4993.1,4999.1
XS Rating Curve= 0 ,0
Exp/Cntr=0.3,0.1

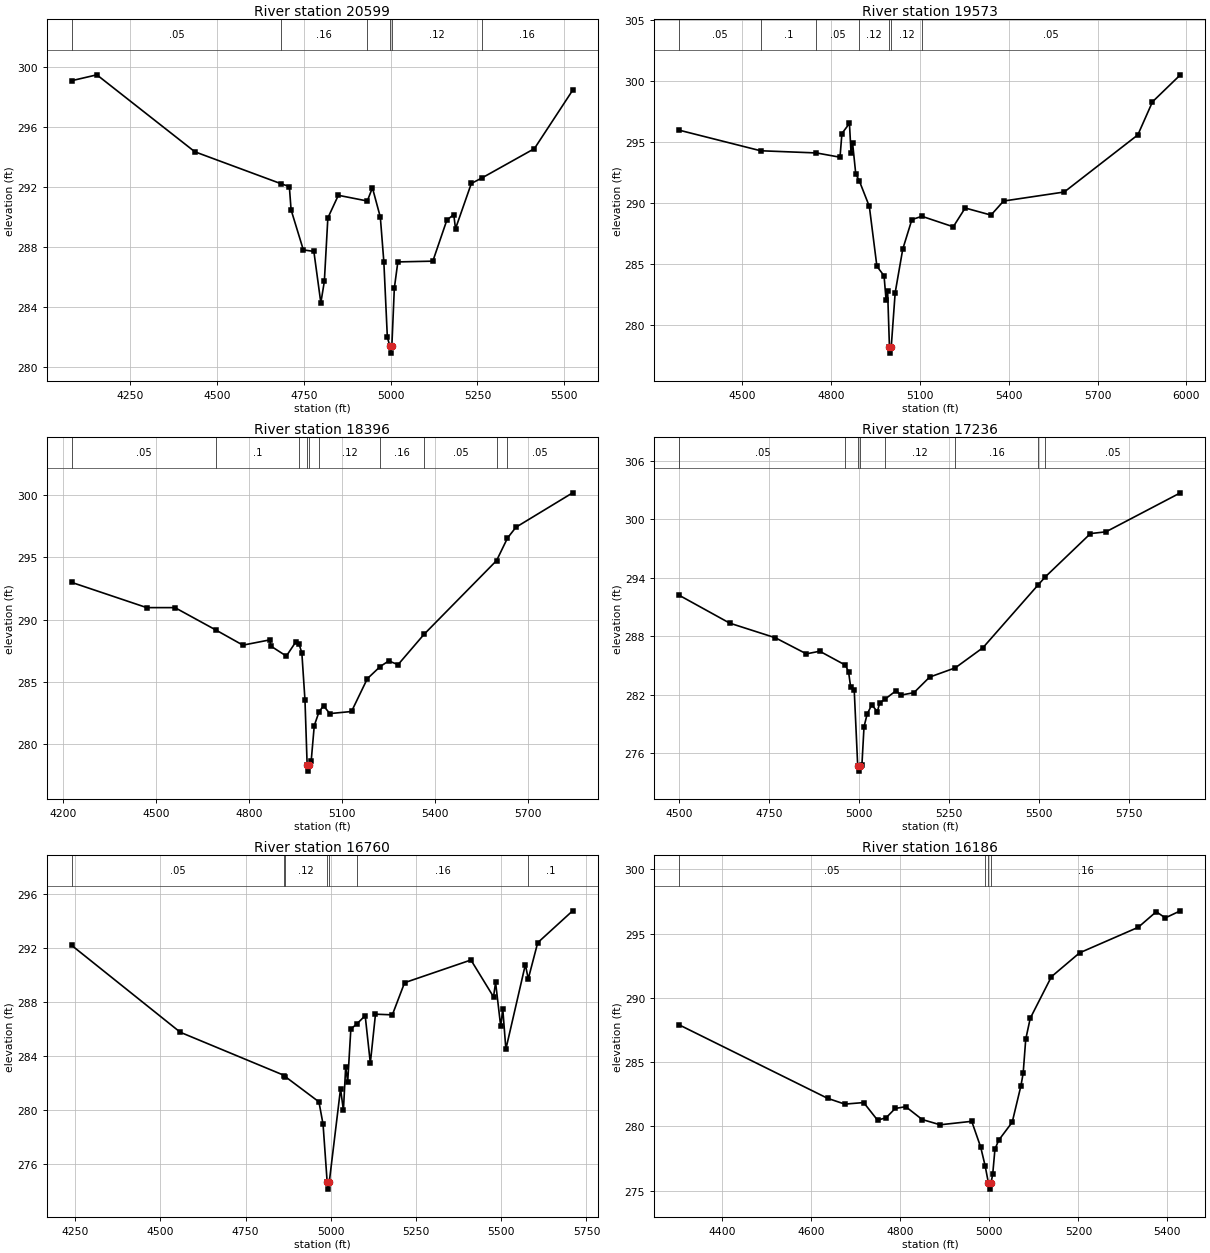
Type RM Length L Ch R = 1 ,20599   ,1026,1026,1026
BEGIN DESCRIPTION:
STEEP HOLLOW BRANCH 34.0
END DESCRIPTION:
XS GIS Cut Line= 3
      3570257.01     10240053.47      3570419.99     10238777.94
       3570342.1     10238641.63
#Sta/Elev= 30
  4081.5  299.09  4153.9  299.48  4436.2  294.35  4684.7  292.22  4708.4  292.03
  4713.4  290.48  4748.7  287.81    4779  287.71  4799.1  284.28  4809.2  285.71
  4819.3  289.94  4849.5  291.45  4932.9  291.07  4947.7  291.95  4970.5  289.99
  4980.6  287.01  4990.7  281.98  4997.7  281.43  5000.5  280.93  5003.7  281.43
  5010.8  285.26  5020.9  287.01  5121.7  287.06    5162  289.79    5182  290.17
    5187  289.22  5232.6  292.24  5263.4  292.61  5414.2  294.56  5524.4  298.45
#Mann= 6 ,-1 , 0
  4081.5     .05       0  4684.7     .16       0  4932.9     .12       0
  4997.7     .07       0  5003.7     .12       0  5263.4     .16       0
Bank Sta=4997.7,5003.7
XS Rating Curve= 0 ,0
Exp/Cntr=0.3,0.1

Type RM Length L Ch R = 1 ,19573   ,1177,1177,1177
BEGIN DESCRIPTION:
STEEP HOLLOW BRANCH 33.0
END DESCRIPTION:
XS GIS Cut Line= 4
      3571016.56     10239984.01      3571077.32     10239680.23
      3570799.54     10238898.98      3570443.66     10238478.01
#Sta/Elev= 30
  4289.3  295.98  4563.1   294.3  4751.6  294.12  4831.1  293.77  4837.5  295.71
  4862.9  296.54  4868.3  294.12  4873.6  294.92  4884.2   292.4  4895.9  291.85
    4930  289.74  4955.5  284.84  4979.7  284.05  4986.4   282.1  4991.7  282.78
  4997.9  278.22  5000.7  277.72  5003.9  278.22  5017.2  282.67  5042.8  286.24
  5073.6  288.66  5107.4  288.93  5213.2  288.07  5253.4  289.61  5340.5  289.03
    5383  290.18  5587.7  290.92    5836   295.6  5885.4  298.31  5979.5  300.52
#Mann= 7 ,-1 , 0
  4289.3     .05       0  4563.1      .1       0  4751.6     .05       0
  4895.9     .12       0  4997.9     .07       0  5003.9     .12       0
  5107.4     .05       0
Bank Sta=4997.9,5003.9
XS Rating Curve= 0 ,0
Exp/Cntr=0.3,0.1

Type RM Length L Ch R = 1 ,18396   ,1160,1160,1160
BEGIN DESCRIPTION:
STEEP HOLLOW BRANCH 32.0
END DESCRIPTION:
XS GIS Cut Line= 2
      3571498.32     10239823.43      3571394.16     10238208.89
#Sta/Elev= 30
    4227  292.99  4469.3  290.96  4560.5  290.96  4693.2  289.15  4779.9  287.94
  4866.1  288.36  4871.1  287.85  4920.2  287.06  4950.3  288.18  4960.7  288.07
  4970.3  287.32  4980.4  283.51  4987.4   278.3  4990.1   277.8  4993.4   278.3
  5000.4  278.59  5010.4  281.46    5026  282.59  5040.5  283.06  5060.5  282.43
  5130.7   282.6  5181.8  285.24  5223.4  286.22  5250.9  286.67    5281  286.37
  5365.3  288.82  5599.3  294.75  5634.5  296.56  5661.8  297.43  5844.9   300.2
#Mann= 10 ,-1 , 0
    4227     .05       0  4693.2      .1       0  4960.7     .05       0
  4987.4    .035       0  4993.4     .05       0    5026     .12       0
  5223.4     .16       0  5365.3     .05       0  5599.3     .16       0
  5634.5     .05       0
Bank Sta=4987.4,4993.4
XS Rating Curve= 0 ,0
Exp/Cntr=0.3,0.1

Type RM Length L Ch R = 1 ,17236   ,476,476,476
BEGIN DESCRIPTION:
STEEP HOLLOW BRANCH 30.0
END DESCRIPTION:
XS GIS Cut Line= 2
      3571589.47     10239832.13      3572292.61     10238629.85
#Sta/Elev= 30
  4500.4  292.19  4640.1  289.34  4767.3  287.83  4853.3  286.18  4890.5  286.45
  4961.8  285.02  4970.6  284.34  4976.4  282.78  4986.3  282.51  4996.1  274.62
  4998.9  274.12  5002.1  274.62  5007.8  274.79  5013.6  278.68  5022.3  279.99
  5035.1  280.93  5050.8  280.24    5057  281.13    5073  281.55  5103.4  282.41
  5115.3  281.93  5152.4  282.19    5196  283.79  5267.3  284.74  5344.2  286.81
  5498.4   293.3    5518  294.11  5643.3  298.55  5686.3  298.73  5893.2  302.74
#Mann= 8 ,-1 , 0
  4500.4     .05       0  4961.8     .16       0  4996.1     .07       0
  5002.1     .16       0    5073     .12       0  5267.3     .16       0
  5498.4      .1       0    5518     .05       0
Bank Sta=4996.1,5002.1
XS Rating Curve= 0 ,0
Exp/Cntr=0.3,0.1

Type RM Length L Ch R = 1 ,16760   ,574,574,574
BEGIN DESCRIPTION:
STEEP HOLLOW BRANCH 28.0
END DESCRIPTION:
XS GIS Cut Line= 2
      3571645.93     10239888.54      3572874.19     10239081.27
#Sta/Elev= 30
  4239.7  292.21  4558.4  285.78  4863.9  282.58  4866.2   282.5  4965.1  280.63
  4977.2  278.97  4989.3  274.67  4992.1  274.17  4995.3  274.67  5028.5   281.6
  5036.9     280  5043.6  283.22  5049.5  282.11  5058.7  286.02  5075.9  286.39
  5100.8  287.01  5115.9   283.5    5131  287.12  5180.5  287.07  5216.4  289.45
  5411.1  291.13  5477.4   288.4  5483.4  289.47  5498.5  286.21  5504.5  287.51
  5513.6  284.53  5570.8  290.79  5579.3  289.73    5607  292.41  5709.5  294.77
#Mann= 7 ,-1 , 0
  4239.7     .05       0  4863.9     .16       0  4866.2     .12       0
  4989.3     .07       0  4995.3     .12       0  5075.9     .16       0
  5579.3      .1       0
Bank Sta=4989.3,4995.3
XS Rating Curve= 0 ,0
Exp/Cntr=0.3,0.1

Type RM Length L Ch R = 1 ,16186   ,590,590,590
BEGIN DESCRIPTION:
STEEP HOLLOW BRANCH 27.0
END DESCRIPTION:
XS GIS Cut Line= 2
      3571892.89     10240003.29      3573005.66     10239833.16
#Sta/Elev= 30
  4303.4  287.89  4636.4  282.18    4675  281.73  4717.4  281.85  4748.6  280.48
  4767.9  280.67  4788.2  281.39    4812  281.53  4848.9  280.53  4889.3  280.12
  4960.2  280.39  4980.4  278.38  4990.4  276.92  4997.6  275.61  5000.4  275.11
  5003.6  275.61  5007.4  276.27  5012.4  278.22  5020.9  278.92  5051.2  280.32
  5070.8  283.16  5075.8  284.13  5081.6  286.78  5091.7  288.41  5139.3  291.65
  5202.7  293.51  5334.5   295.5  5374.9  296.71  5395.2  296.23  5429.1  296.78
#Mann= 4 ,-1 , 0
  4303.4     .05       0  4990.4     .16       0  4997.6     .07       0
  5003.6     .16       0
Bank Sta=4997.6,5003.6
XS Rating Curve= 0 ,0
Exp/Cntr=0.3,0.1

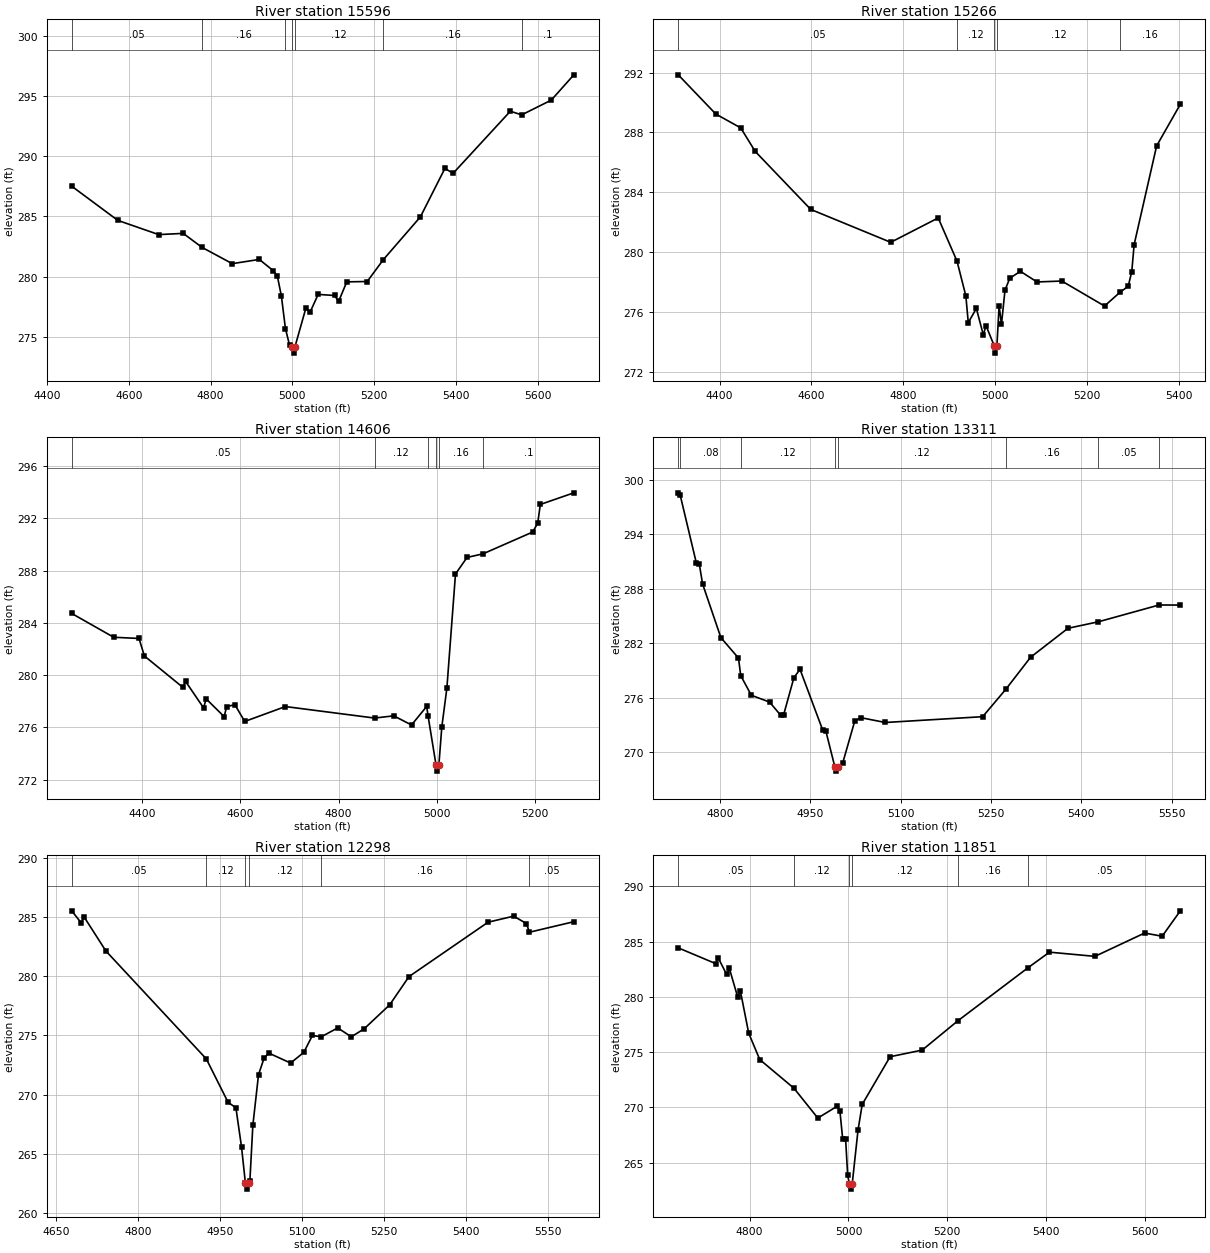
Type RM Length L Ch R = 1 ,15596   ,330,330,330
BEGIN DESCRIPTION:
STEEP HOLLOW BRANCH 26.0
END DESCRIPTION:
XS GIS Cut Line= 2
       3571929.5     10240288.01      3573157.43     10240257.64
#Sta/Elev= 30
  4460.5   287.5  4573.1  284.67  4673.2  283.49  4733.2  283.59  4779.1  282.43
  4853.2  281.08  4919.3  281.43  4953.3   280.5  4963.3  280.07  4973.3   278.4
  4983.2   275.7  4993.3  274.32  5000.3  274.16    5003  273.66  5006.3  274.16
  5033.3   277.4  5043.3  277.04  5063.3  278.53  5103.3  278.44  5113.3  277.95
  5133.3  279.57  5183.3   279.6  5222.9  281.42  5313.4  284.96  5373.4  288.98
  5393.4  288.57  5533.4  293.72  5561.2  293.42  5633.5  294.64  5688.8  296.74
#Mann= 7 ,-1 , 0
  4460.5     .05       0  4779.1     .16       0  4983.2     .12       0
  5000.3     .07       0  5006.3     .12       0  5222.9     .16       0
  5561.2      .1       0
Bank Sta=5000.3,5006.3
XS Rating Curve= 0 ,0
Exp/Cntr=0.3,0.1

Type RM Length L Ch R = 1 ,15266   ,660,660,660
BEGIN DESCRIPTION:
STEEP HOLLOW BRANCH 25.0
END DESCRIPTION:
XS GIS Cut Line= 3
      3571892.15     10240741.63      3572542.11     10240541.64
      3572942.07     10240441.65
#Sta/Elev= 30
  4310.1  291.85  4391.8  289.23  4446.1   288.3  4477.5  286.73  4598.4  282.85
  4772.4  280.65  4875.7  282.28  4916.6  279.39  4935.8  277.07  4941.1  275.28
  4958.7  276.23  4973.8  274.46  4979.7  275.08  4997.4  273.74  5000.2  273.24
  5003.4  273.74  5008.2  276.41  5013.3  275.16    5021  277.45  5031.4  278.25
  5054.5  278.71  5090.6     278  5144.7  278.06  5237.5  276.39  5271.3  277.31
    5289  277.71  5296.8  278.69  5301.9  280.49  5350.9   287.1  5402.4  289.88
#Mann= 5 ,-1 , 0
  4310.1     .05       0  4916.6     .12       0  4997.4     .07       0
  5003.4     .12       0  5271.3     .16       0
Bank Sta=4997.4,5003.4
XS Rating Curve= 0 ,0
Exp/Cntr=0.3,0.1

Type RM Length L Ch R = 1 ,14606   ,1295,1295,1295
BEGIN DESCRIPTION:
STEEP HOLLOW BRANCH 24.0
END DESCRIPTION:
XS GIS Cut Line= 2
      3572198.94     10240870.25       3573193.7     10240630.68
#Sta/Elev= 30
  4256.4  284.72  4341.9   282.9  4393.4  282.81  4404.4  281.47  4483.1  279.06
  4488.2  279.53    4525   277.5  4530.2  278.19  4566.9  276.83  4572.1   277.6
  4588.8  277.74  4608.9  276.46  4691.7   277.6  4873.5  276.72  4912.6  276.89
  4948.8  276.19  4979.7  277.61  4982.6  276.86  4998.6  273.16  5001.4  272.66
  5004.6  273.16  5010.5  276.04  5020.8  278.99  5038.4  287.74    5062  289.01
  5094.3  289.28  5195.7  290.95    5206  291.63  5211.3  293.06  5279.6  293.95
#Mann= 6 ,-1 , 0
  4256.4     .05       0  4873.5     .12       0  4982.6     .16       0
  4998.6     .07       0  5004.6     .16       0  5094.3      .1       0
Bank Sta=4998.6,5004.6
XS Rating Curve= 0 ,0
Exp/Cntr=0.3,0.1

Type RM Length L Ch R = 1 ,13311   ,1013,1013,1013
BEGIN DESCRIPTION:
STEEP HOLLOW BRANCH 23.0
END DESCRIPTION:
XS GIS Cut Line= 2
      3572192.08     10241391.65      3573016.65      10241271.3
#Sta/Elev= 30
    4731  298.56  4734.3  298.29    4761  290.84    4766   290.7  4771.4  288.52
  4801.8   282.6    4831  280.35  4834.7  278.42  4852.3  276.25  4882.6   275.5
  4900.9  274.06    4906  274.12    4923  278.19  4933.1  279.11  4970.9  272.39
    4976  272.31  4990.8  268.39  4993.5  267.89  4996.8  268.39  5003.9  268.77
  5024.1  273.44  5034.2  273.78  5074.6  273.25  5236.3  273.89  5274.7  276.91
  5315.8  280.44  5377.8  283.63  5428.4  284.35  5529.1   286.2  5564.3  286.19
#Mann= 8 ,-1 , 0
    4731     .05       0  4734.3     .08       0  4834.7     .12       0
  4990.8     .07       0  4996.8     .12       0  5274.7     .16       0
  5428.4     .05       0  5529.1     .16       0
Bank Sta=4990.8,4996.8
XS Rating Curve= 0 ,0
Exp/Cntr=0.3,0.1

Type RM Length L Ch R = 1 ,12298   ,447,447,447
BEGIN DESCRIPTION:
STEEP HOLLOW BRANCH 21.0
END DESCRIPTION:
XS GIS Cut Line= 3
      3572842.09     10242191.68      3572971.48     10241713.05
      3573140.89     10241325.03
#Sta/Elev= 30
  4678.8  285.53  4696.2   284.5  4701.4  285.01  4741.2  282.14  4925.1  273.01
    4965  269.34  4979.3  268.88  4989.6  265.56  4996.7   262.5  4999.4     262
  5002.7   262.5  5004.9  262.71  5010.3  267.38  5020.7  271.68    5031  273.09
  5039.6   273.5  5079.4  272.66  5103.6  273.56  5119.3  274.99  5135.6  274.88
  5165.7  275.63  5190.6  274.88    5214  275.55  5260.8  277.58  5296.2  279.97
    5441  284.57  5487.9  285.08  5511.3  284.45  5516.6  283.72    5598  284.61
#Mann= 6 ,-1 , 0
  4678.8     .05       0  4925.1     .12       0  4996.7     .07       0
  5002.7     .12       0  5135.6     .16       0  5516.6     .05       0
Bank Sta=4996.7,5002.7
XS Rating Curve= 0 ,0
Exp/Cntr=0.3,0.1

Type RM Length L Ch R = 1 ,11851   ,411,411,411
BEGIN DESCRIPTION:
STEEP HOLLOW BRANCH 20.0
END DESCRIPTION:
XS GIS Cut Line= 3
      3572942.14     10242291.63      3573242.11     10242141.64
      3573642.08     10241591.68
#Sta/Elev= 30
  4655.7  284.43  4731.1  283.01  4736.7  283.51  4753.5  282.03  4759.1  282.57
  4775.9  279.98  4781.4  280.53  4798.2  276.71  4820.6  274.32  4889.7  271.73
    4938  269.03  4977.1   270.1  4982.7  269.66  4988.3  267.13  4994.2  267.13
  4998.4  263.86  5001.6   263.1  5004.3   262.6  5007.6   263.1  5019.3  267.94
  5027.8  270.27  5084.2  274.58  5149.1  275.18  5221.2  277.83  5363.7  282.65
  5406.5  284.04  5498.4  283.66  5598.9  285.77  5634.4  285.48  5671.1  287.78
#Mann= 6 ,-1 , 0
  4655.7     .05       0  4889.7     .12       0  5001.6     .07       0
  5007.6     .12       0  5221.2     .16       0  5363.7     .05       0
Bank Sta=5001.6,5007.6
XS Rating Curve= 0 ,0
Exp/Cntr=0.3,0.1

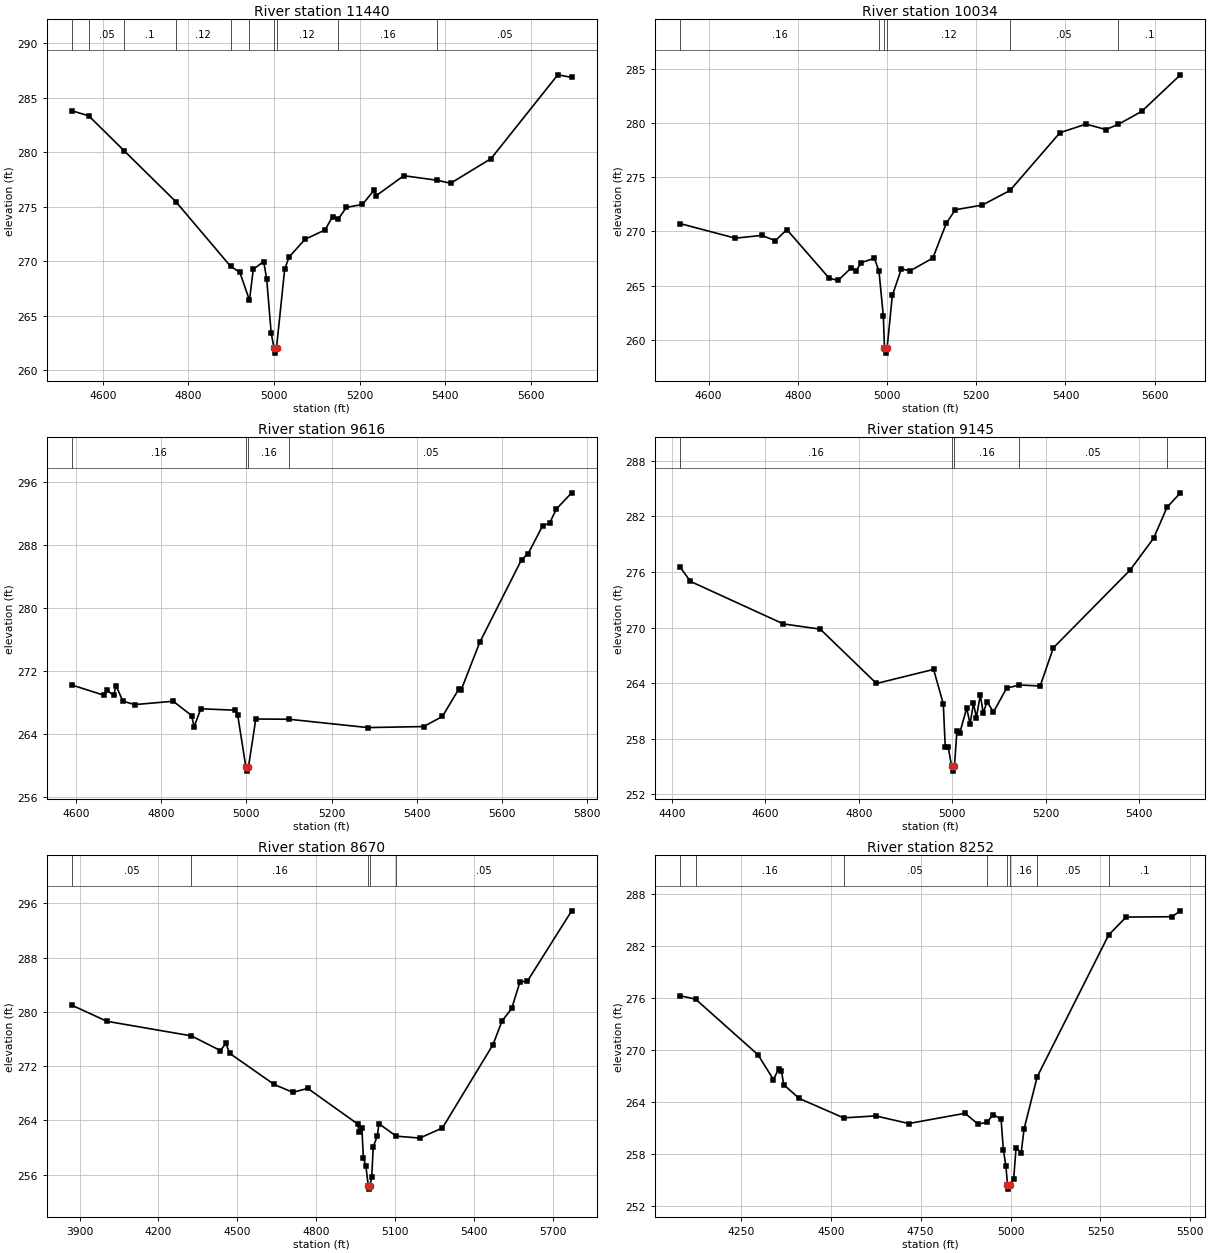
Type RM Length L Ch R = 1 ,11440   ,1406,1406,1406
BEGIN DESCRIPTION:
STEEP HOLLOW BRANCH 19.0
END DESCRIPTION:
XS GIS Cut Line= 2
       3573391.6     10242776.55      3573745.76     10241661.96
#Sta/Elev= 30
  4526.6  283.81  4566.7  283.34  4650.1  280.11  4770.3  275.46  4898.7  269.51
    4920  268.98  4942.7   266.4  4951.5  269.25  4975.9  269.96  4982.9  268.36
  4993.4  263.41  4999.9  262.05  5002.6  261.55  5005.9  262.05  5024.9  269.23
  5035.1  270.37  5072.6     272  5119.3  272.86  5137.1  274.09  5150.1  273.86
  5169.4  274.93  5206.9   275.2  5233.9  276.51  5239.1  276.01  5303.6  277.84
  5381.2  277.42  5413.1  277.15  5507.6  279.41  5663.6   287.1  5696.1  286.87
#Mann= 10 ,-1 , 0
  4526.6      .1       0  4566.7     .05       0  4650.1      .1       0
  4770.3     .12       0  4898.7     .16       0  4942.7     .12       0
  4999.9     .07       0  5005.9     .12       0  5150.1     .16       0
  5381.2     .05       0
Bank Sta=4999.9,5005.9
XS Rating Curve= 0 ,0
Exp/Cntr=0.3,0.1

Type RM Length L Ch R = 1 ,10034   ,418,418,418
BEGIN DESCRIPTION:
STEEP HOLLOW BRANCH 18.0
END DESCRIPTION:
XS GIS Cut Line= 4
      3574345.09     10242709.15      3574381.19     10242578.59
      3574303.91     10242012.48      3574116.35     10241642.65
#Sta/Elev= 30
  4536.3  270.71  4659.9  269.37  4719.1  269.63  4749.4  269.14  4775.3  270.16
  4870.5  265.67  4890.7  265.49  4919.9  266.65  4931.1  266.37  4941.2   267.1
  4971.5  267.52  4981.9  266.33  4991.7  262.16  4994.2  259.28    4997  258.78
  5000.2  259.28  5011.8  264.09    5032  266.53  5052.2  266.37  5102.7  267.54
    5133  270.76  5153.1  271.99  5213.7  272.42  5275.7  273.77  5387.5  279.08
  5445.9  279.88  5490.7  279.38  5518.8  279.86  5571.3  281.06  5657.8  284.42
#Mann= 6 ,-1 , 0
  4536.3     .16       0  4981.9     .12       0  4994.2     .07       0
  5000.2     .12       0  5275.7     .05       0  5518.8      .1       0
Bank Sta=4994.2,5000.2
XS Rating Curve= 0 ,0
Exp/Cntr=0.3,0.1

Type RM Length L Ch R = 1 ,9616    ,471,471,471
BEGIN DESCRIPTION:
STEEP HOLLOW BRANCH 17.0
END DESCRIPTION:
XS GIS Cut Line= 3
       3574476.6     10242719.59      3574692.11     10242341.64
       3575042.1     10241691.65
#Sta/Elev= 30
  4589.8  270.23  4666.9  268.89  4672.7  269.54  4688.5  268.91  4694.3  270.12
  4710.1  268.17  4737.5  267.72  4828.3  268.15  4871.5  266.33  4877.2  264.91
  4893.1  267.19  4973.7  267.01  4979.5  266.42  4998.8  259.76  5001.6  259.26
  5004.8  259.76    5022  265.89  5099.9  265.86  5284.5   264.8  5415.9  264.93
  5459.7  266.21  5497.8  269.65  5503.5  269.54  5547.3  275.63  5645.5  286.16
  5660.9  286.92    5695  290.48  5711.2   290.8  5727.4  292.62  5763.1  294.66
#Mann= 4 ,-1 , 0
  4589.8     .16       0  4998.8     .07       0  5004.8     .16       0
  5099.9     .05       0
Bank Sta=4998.8,5004.8
XS Rating Curve= 0 ,0
Exp/Cntr=0.3,0.1

Type RM Length L Ch R = 1 ,9145    ,475,475,475
BEGIN DESCRIPTION:
STEEP HOLLOW BRANCH 16.0
END DESCRIPTION:
XS GIS Cut Line= 3
      3574742.13     10242891.62      3575092.11     10242441.64
      3575392.13     10242041.61
#Sta/Elev= 30
  4417.8   276.5  4439.5  274.98  4638.6  270.39  4717.3  269.83  4837.6  263.97
  4959.8  265.49  4980.6  261.77  4984.7  257.14    4991  257.14  4998.4  255.02
  5001.1  254.52  5004.4  255.02  5009.7  258.82    5016  258.67  5030.6  261.31
  5037.9  259.62  5045.1  261.82  5051.4  260.29  5059.7  262.75    5066   260.8
  5074.3     262  5087.9  260.89    5116  263.46  5143.4  263.81  5187.9   263.7
    5216  267.81  5380.6  276.22  5430.6  279.64  5459.3  282.97  5487.9  284.53
#Mann= 5 ,-1 , 0
  4417.8     .16       0  4998.4     .07       0  5004.4     .16       0
  5143.4     .05       0  5459.3      .1       0
Bank Sta=4998.4,5004.4
XS Rating Curve= 0 ,0
Exp/Cntr=0.3,0.1

Type RM Length L Ch R = 1 ,8670    ,418,418,418
BEGIN DESCRIPTION:
STEEP HOLLOW BRANCH 15.0
END DESCRIPTION:
XS GIS Cut Line= 3
      3574592.09     10243491.66      3575342.11     10242691.64
      3576042.08     10242291.66
#Sta/Elev= 30
  3869.3     281  4003.9  278.61  4325.2  276.46  4435.2   274.3  4456.7  275.34
  4470.8  273.89  4640.4  269.29  4711.2  268.13  4767.8  268.72  4958.8  263.44
  4962.5  262.34  4973.8  262.88  4979.6  258.42  4988.9  257.32  4998.2  254.36
  5000.9  253.86  5004.2  254.36  5011.3  255.59    5017  260.08  5032.9  261.74
  5038.6  263.51  5104.5  261.67  5194.1  261.39  5280.5  262.89  5472.7  275.17
  5507.2  278.66  5543.9   280.5  5575.6  284.46    5603  284.49  5772.1   294.9
#Mann= 5 ,-1 , 0
  3869.3     .05       0  4325.2     .16       0  4998.2     .07       0
  5004.2     .16       0  5104.5     .05       0
Bank Sta=4998.2,5004.2
XS Rating Curve= 0 ,0
Exp/Cntr=0.3,0.1

Type RM Length L Ch R = 1 ,8252    ,1127,1127,1127
BEGIN DESCRIPTION:
STEEP HOLLOW BRANCH 13.0
END DESCRIPTION:
XS GIS Cut Line= 2
      3575035.81     10243420.55      3576105.14     10242531.72
#Sta/Elev= 30
  4081.8  276.24  4124.4  275.85    4298  269.43  4340.9  266.57  4355.2   267.8
    4363  267.58  4369.5  265.98  4412.5  264.39  4536.1  262.15  4624.7  262.38
  4717.2   261.5  4873.4  262.68  4909.2  261.45  4934.3  261.63  4951.5  262.53
  4973.7  262.01  4980.2  258.42  4987.2  256.58  4991.5  254.43  4994.3  253.93
  4997.5  254.43  5008.8  255.15  5015.3  258.64  5029.7  258.15  5037.5  260.84
  5074.2   266.9  5272.9  283.26  5321.3  285.32  5448.9  285.36  5472.3  286.04
#Mann= 8 ,-1 , 0
  4081.8      .1       0  4124.4     .16       0  4536.1     .05       0
  4934.3     .16       0  4991.5     .07       0  4997.5     .16       0
  5074.2     .05       0  5272.9      .1       0
Bank Sta=4991.5,4997.5
XS Rating Curve= 0 ,0
Exp/Cntr=0.3,0.1