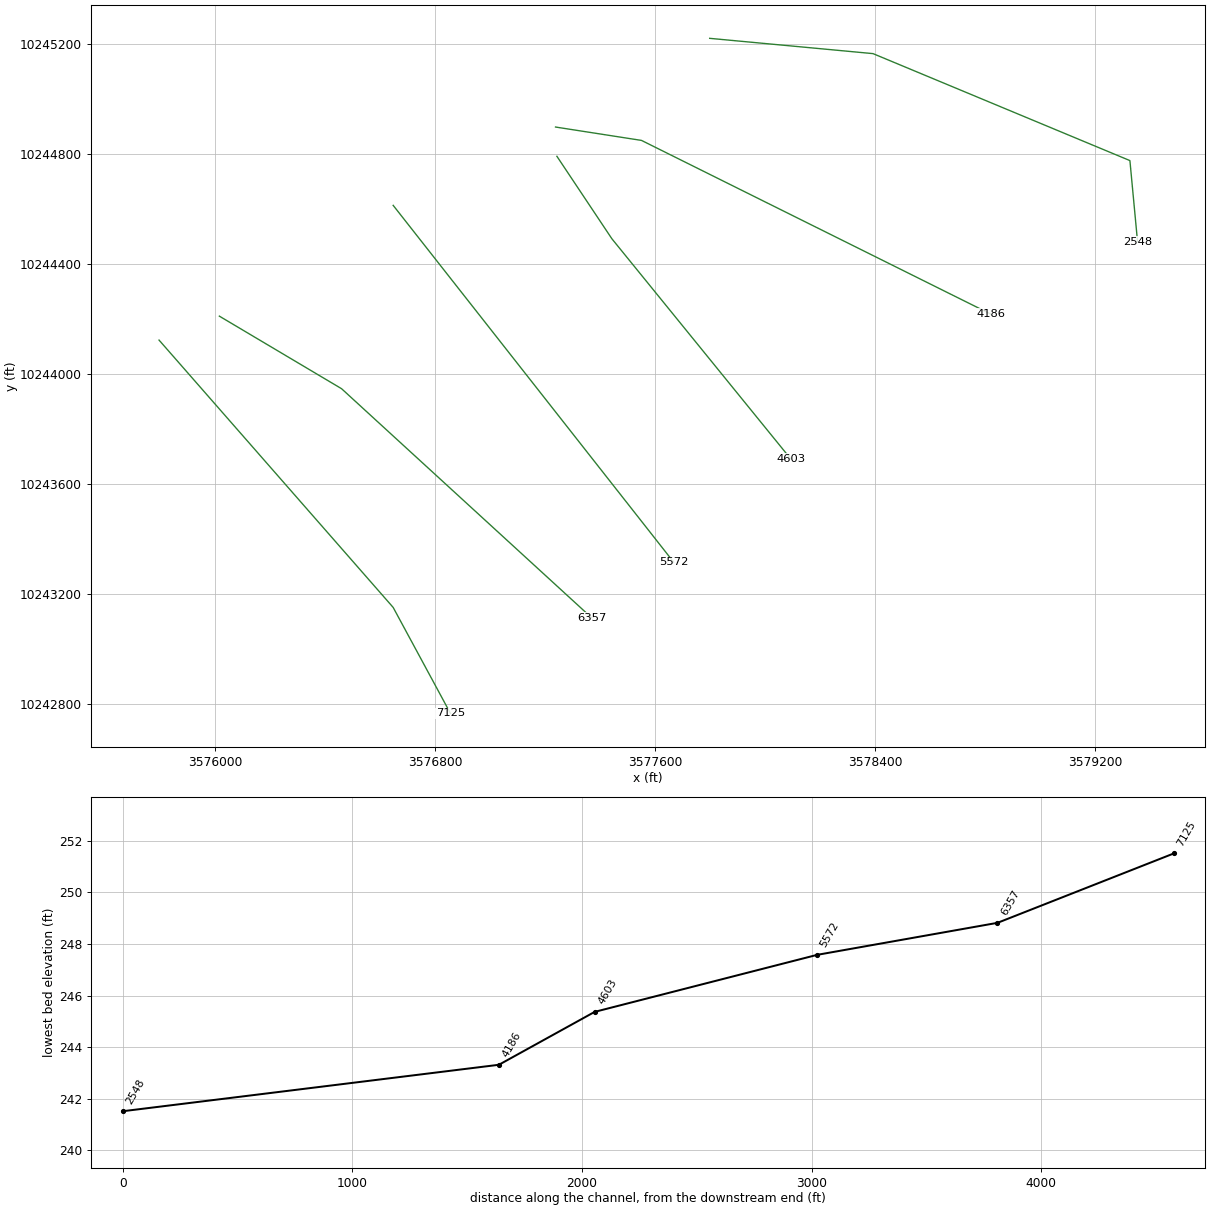
HEC-RAS study STEEP HOLLOW BRANCH.prj: STEEP HOLLOW BRANCH Base Level Engineering

--- STEEP HOLLOW BRANCH.g01 (geometry) --- (continued)

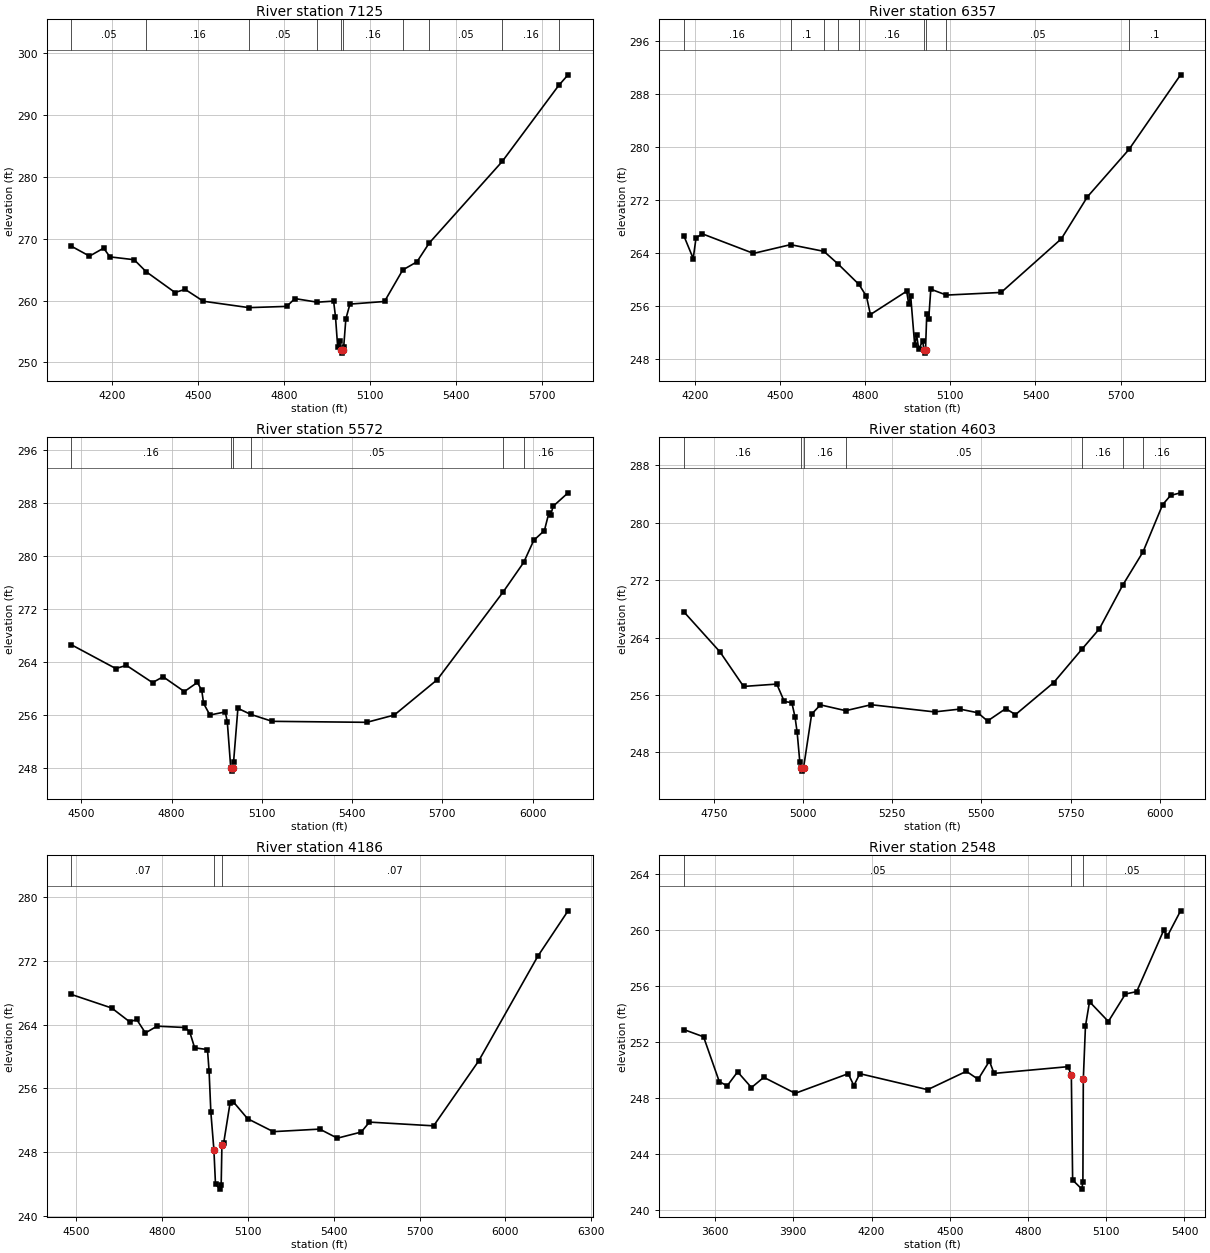
Type RM Length L Ch R = 1 ,7125    ,768,768,768
BEGIN DESCRIPTION:
STEEP HOLLOW BRANCH 12.0
END DESCRIPTION:
XS GIS Cut Line= 3
      3575795.58     10244123.55      3576646.82     10243151.51
      3576855.01     10242766.36
#Sta/Elev= 30
  4059.7  268.75  4122.4  267.16  4171.7  268.45  4193.6  267.04    4278  266.58
  4319.7  264.65  4420.4  261.29  4455.5   261.8  4519.1  259.88  4677.8  258.85
  4809.5  259.05    4838  260.31  4915.7  259.73  4972.8   259.9  4979.4  257.41
    4987  252.53  4993.6  253.48  4998.2  252.01    5001  251.51  5004.2  252.01
  5007.9  252.44  5015.5  257.03  5029.7  259.42  5150.2  259.84  5213.7  264.93
  5263.2  266.24  5305.6  269.25  5560.2  282.43  5757.1   294.7  5789.6  296.41
#Mann= 10 ,-1 , 0
  4059.7     .05       0  4319.7     .16       0  4677.8     .05       0
  4915.7     .16       0  4998.2     .07       0  5004.2     .16       0
  5213.7      .1       0  5305.6     .05       0  5560.2     .16       0
  5757.1     .05       0
Bank Sta=4998.2,5004.2
XS Rating Curve= 0 ,0
Exp/Cntr=0.3,0.1

Type RM Length L Ch R = 1 ,6357    ,785,785,785
BEGIN DESCRIPTION:
STEEP HOLLOW BRANCH 10.0
END DESCRIPTION:
XS GIS Cut Line= 3
      3576014.89     10244210.53      3576459.32     10243946.65
       3577368.1     10243114.18
#Sta/Elev= 30
  4161.9  266.46  4194.2   263.1    4204  266.16  4225.4  266.84  4406.6  263.87
  4537.1  265.19  4654.7  264.18  4704.4  262.28  4778.4  259.18  4804.6  257.38
  4818.5  254.64  4946.1  258.16  4953.5  256.24  4960.3  257.47  4974.5  250.06
  4981.3  251.51  4988.7  249.43  5002.9  250.67  5006.6  249.32  5009.4  248.82
  5012.6  249.32    5017  254.68  5023.8  253.93  5031.2  258.47  5086.2  257.58
  5279.1  257.98  5491.2  266.08  5583.1  272.42  5729.4  279.56  5911.2  290.82
#Mann= 9 ,-1 , 0
  4161.9     .16       0  4537.1      .1       0  4654.7     .16       0
  4704.4      .1       0  4778.4     .16       0  5006.6     .07       0
  5012.6     .16       0  5086.2     .05       0  5729.4      .1       0
Bank Sta=5006.6,5012.6
XS Rating Curve= 0 ,0
Exp/Cntr=0.3,0.1

Type RM Length L Ch R = 1 ,5572    ,969,969,969
BEGIN DESCRIPTION:
STEEP HOLLOW BRANCH 9.0
END DESCRIPTION:
XS GIS Cut Line= 2
      3576646.84     10244613.29      3577666.61     10243316.03
#Sta/Elev= 30
  4467.4  266.63  4614.6  263.05  4649.9  263.53  4736.6  260.93  4771.8  261.81
  4842.4  259.58  4885.7  260.95  4900.2  259.77  4906.5  257.78  4927.4  256.04
  4978.3  256.51  4985.1  255.04  4996.6  248.08  4999.3  247.58  5002.6  248.08
  5005.9   248.9  5020.4  257.05  5062.4  256.15  5134.3  255.09  5448.7  254.94
  5540.1  256.04  5682.8  261.37    5902  274.61    5970  279.05  6003.6  282.39
  6038.9  283.86  6053.3  286.44  6059.7  286.16  6067.8  287.52  6117.5  289.55
#Mann= 6 ,-1 , 0
  4467.4     .16       0  4996.6     .07       0  5002.6     .16       0
  5062.4     .05       0    5902      .1       0    5970     .16       0
Bank Sta=4996.6,5002.6
XS Rating Curve= 0 ,0
Exp/Cntr=0.3,0.1

Type RM Length L Ch R = 1 ,4603    ,417,417,417
BEGIN DESCRIPTION:
STEEP HOLLOW BRANCH 8.0
END DESCRIPTION:
XS GIS Cut Line= 3
       3577242.1     10244791.65      3577442.11     10244491.64
      3578092.08     10243691.68
#Sta/Elev= 30
  4666.9  267.56  4767.6     262  4833.7  257.18  4926.8  257.51  4947.8  255.08
  4968.9  254.92  4977.9  252.92  4983.9  250.76  4991.4  246.58  4995.9  245.87
  4998.7  245.37  5001.9  245.87  5024.5  253.32    5049  254.61  5119.9   253.8
  5191.3  254.63  5368.7  253.63  5439.8  254.02  5490.1  253.51  5517.3  252.36
  5568.4  254.09  5595.6  253.25  5702.7  257.72  5783.2  262.46  5830.5   265.2
  5895.9  271.29  5952.9  275.94  6007.9  282.53  6030.2  283.82  6058.2  284.18
#Mann= 7 ,-1 , 0
  4666.9     .16       0  4995.9     .07       0  5001.9     .16       0
  5119.9     .05       0  5783.2     .16       0  5895.9     .05       0
  5952.9     .16       0
Bank Sta=4995.9,5001.9
XS Rating Curve= 0 ,0
Exp/Cntr=0.3,0.1

Type RM Length L Ch R = 1 ,4186    ,1638,1638,1638
BEGIN DESCRIPTION:
STEEP HOLLOW BRANCH 6.0
END DESCRIPTION:
XS GIS Cut Line= 3
      3577237.08     10244898.04       3577549.6     10244849.43
      3578818.77     10244218.31
#Sta/Elev= 30
  4484.8  267.77  4625.3  266.07  4688.2  264.33  4712.5  264.63  4742.9  262.94
  4783.4  263.79  4882.1  263.62  4897.9  263.03  4914.8  261.07  4959.6  260.85
  4965.2  258.15  4971.4  252.96    4982  248.26  4987.6  243.92  5004.1  243.32
  5007.4  243.82    5010  248.87  5016.1   249.1  5038.4  254.13  5049.2  254.31
  5099.6  252.17  5189.2  250.54  5351.5  250.86  5413.1  249.72  5496.3  250.49
  5525.1  251.74  5749.1  251.27  5905.9  259.39    6113  272.58  6218.5  278.28
#Mann= 3 , 0 , 0
  4484.8     .07       0    4982     .05       0    5010     .07       0
Bank Sta=4982,5010
XS Rating Curve= 0 ,0
Exp/Cntr=0.3,0.1

Type RM Length L Ch R = 1 ,2548    ,0,0,0
BEGIN DESCRIPTION:
STEEP HOLLOW BRANCH 1.0
END DESCRIPTION:
XS GIS Cut Line= 4
      3577797.54     10245220.52      3578391.26     10245164.96
      3579325.29     10244776.07      3579353.07     10244480.95
#Sta/Elev= 30
  3480.7  252.89  3555.6  252.38  3615.8  249.19    3646  248.88  3686.2  249.88
  3739.2  248.76  3786.6  249.49  3907.1  248.35  4110.4  249.75  4132.1   248.9
  4154.9  249.75    4415  248.61  4563.5  249.92  4608.7  249.35    4652  250.65
  4669.7  249.77  4953.6  250.25  4966.2  249.63 4971.14  242.17 5006.46  241.52
 5010.48  242.04  5012.1  249.35  5020.3  253.13  5035.9  254.88  5108.2  253.47
  5173.6  255.43  5216.8   255.6  5320.4  259.97  5334.3  259.55  5385.2  261.36
#Mann= 3 , 0 , 0
  3480.7     .05       0  4966.2     .03       0  5012.1     .05       0
Bank Sta=4966.2,5012.1
XS Rating Curve= 0 ,0
Exp/Cntr=0.3,0.1

Chan Stop Cuts=-1
Use User Specified Reach Order=0
Composite Channel Slope=5