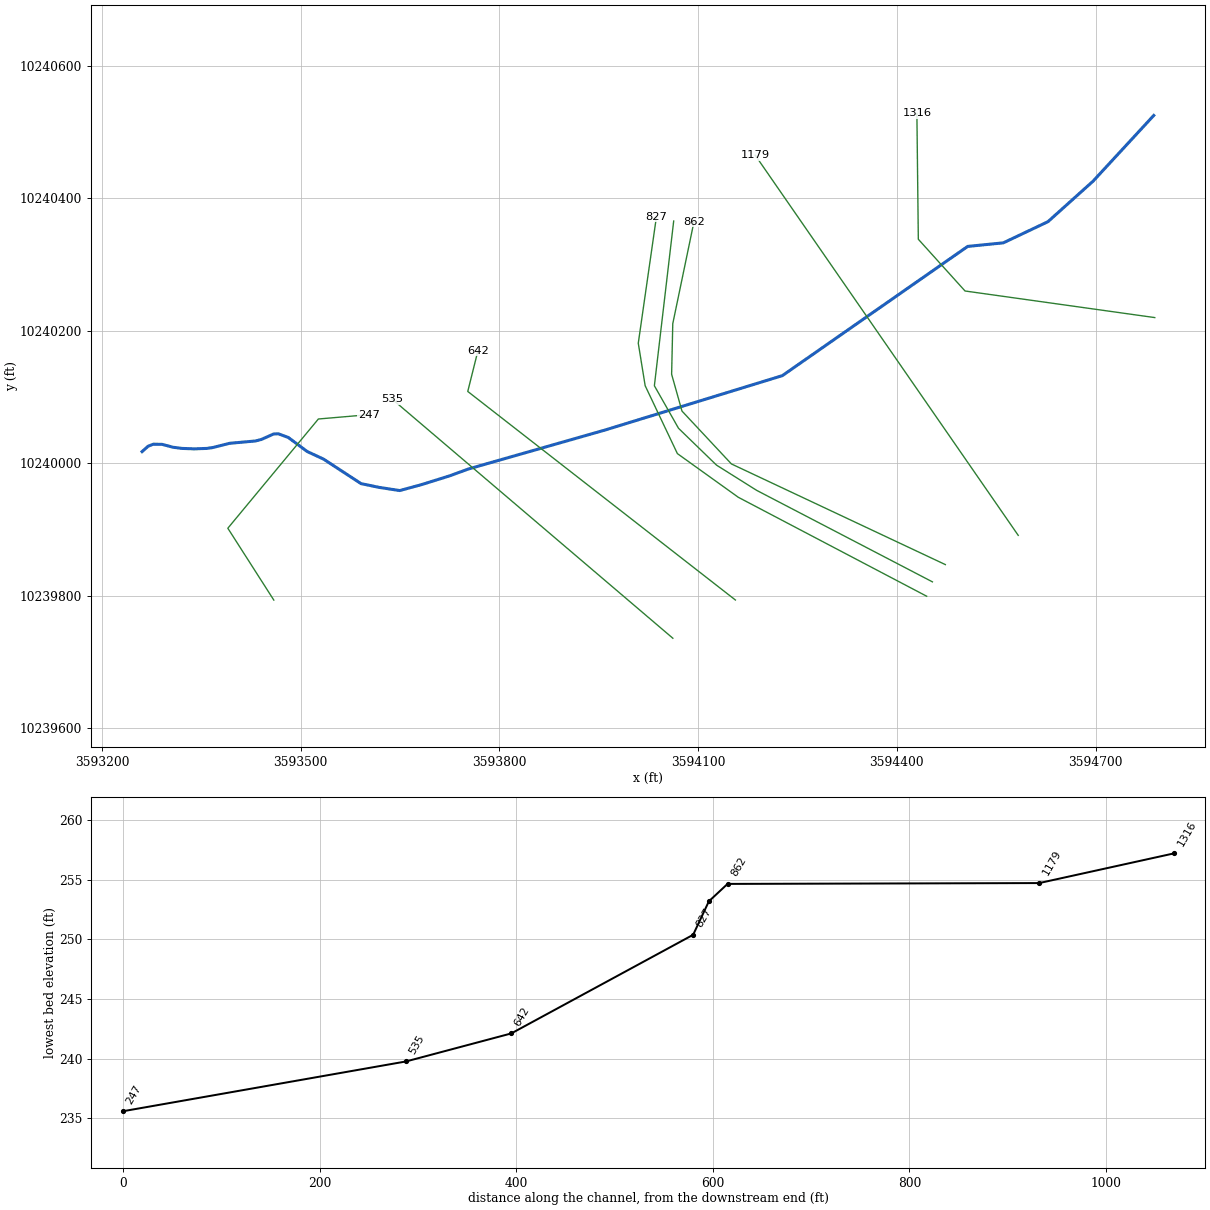
--- UNT003 IN WICK.prj (project) ---

Proj Title=UNT003 IN WICK Base Level Engineering
Current Plan=p01
Default Exp/Contr=0.3,0.1
English Units
Geom File=g01
Flow File=f01
Plan File=p01
Y Axis Title=Elevation
X Axis Title(PF)=Main Channel Distance
X Axis Title(XS)=Station
BEGIN DESCRIPTION:
UNT003 IN WICK
END DESCRIPTION:
DSS Export Rating Curves= 0
DSS Export Rating Curve Sorted= 0
DSS Export Volume Flow Curves= 0
DXF OffsetX= 0
DXF OffsetY= 0
DXF ScaleX= 1
DXF ScaleY= 10

--- UNT003 IN WICK.p01 (plan) ---

Plan Title=Multiple Run
Short Identifier=Multiple
Geom File=g01
Flow File=f01
Subcritical Flow
K Sum by GR= 0
Std Step Tol= 0.01
Critical Tol= 0.01
Num of Std Step Trials= 20
Max Error Tol= 0.3
Flow Tol Ratio= 0.001
Split Flow NTrial= 30
Split Flow Tol= 0.02
Split Flow Ratio= 0.02
Log Output Level= 0
Friction Slope Method= 1
Unsteady Friction Slope Method= 2
Unsteady Bridges Friction Slope Method= 1
Parabolic Critical Depth
Global Vel Dist=  1 , 1 , 1
Global Log Level= 0
CheckData=True
Encroach Param= -1, 0, 0, 0
BEGIN DESCRIPTION:
Multiple Run
END DESCRIPTION:

--- UNT003 IN WICK.f01 (steady flow) ---

Flow Title=Multiple
Program Version=4.10
Number of Profiles= 7
Profile Names=10-year,25-year,50-year,1pct_min,100-year,1pct_plu,500-year
River Rch & RM=UNT003 IN WICK,Reach-1         ,1316
     182     225     257     216     292     395     377
Boundary for River Rch & Prof#=UNT003 IN WICK,Reach-1         , 1
Up Type= 0
Dn Type= 3
Dn Slope=0.01661
Boundary for River Rch & Prof#=UNT003 IN WICK,Reach-1         , 2
Up Type= 0
Dn Type= 3
Dn Slope=0.01661
Boundary for River Rch & Prof#=UNT003 IN WICK,Reach-1         , 3
Up Type= 0
Dn Type= 3
Dn Slope=0.01661
Boundary for River Rch & Prof#=UNT003 IN WICK,Reach-1         , 4
Up Type= 0
Dn Type= 3
Dn Slope=0.01661
Boundary for River Rch & Prof#=UNT003 IN WICK,Reach-1         , 5
Up Type= 0
Dn Type= 3
Dn Slope=0.01661
Boundary for River Rch & Prof#=UNT003 IN WICK,Reach-1         , 6
Up Type= 0
Dn Type= 3
Dn Slope=0.01661
Boundary for River Rch & Prof#=UNT003 IN WICK,Reach-1         , 7
Up Type= 0
Dn Type= 3
Dn Slope=0.01661
DSS Import GetInterval= 0
DSS Import GetPeak= 0
DSS Import FillOption= 0

--- UNT003 IN WICK.g01 (geometry) ---

Geom Title=Existing Conditions
Program Version=4.10

River Reach=UNT003 IN WICK  ,Reach-1
Reach XY= 30
       3594787.9      10240525.2      3594696.23     10240425.89
      3594628.17     10240364.78      3594560.81     10240332.84
      3594506.97     10240327.45       3594227.2     10240132.36
      3593959.98     10240050.39      3593753.03     10239991.36
      3593724.56     10239980.94       3593682.2     10239967.75
      3593649.53     10239958.85      3593618.64     10239963.61
      3593591.13      10239969.3      3593534.54      10240006.3
      3593509.77     10240017.82      3593481.15     10240039.07
      3593466.01     10240044.59      3593458.97     10240044.19
      3593440.53     10240035.96      3593431.55     10240033.69
      3593392.78      10240030.2      3593366.54     10240023.63
      3593357.66     10240022.46      3593339.28      10240021.8
      3593320.76     10240022.48       3593307.3      10240024.2
      3593290.58     10240028.67      3593277.48     10240028.82
      3593269.75     10240025.86      3593260.48     10240017.65

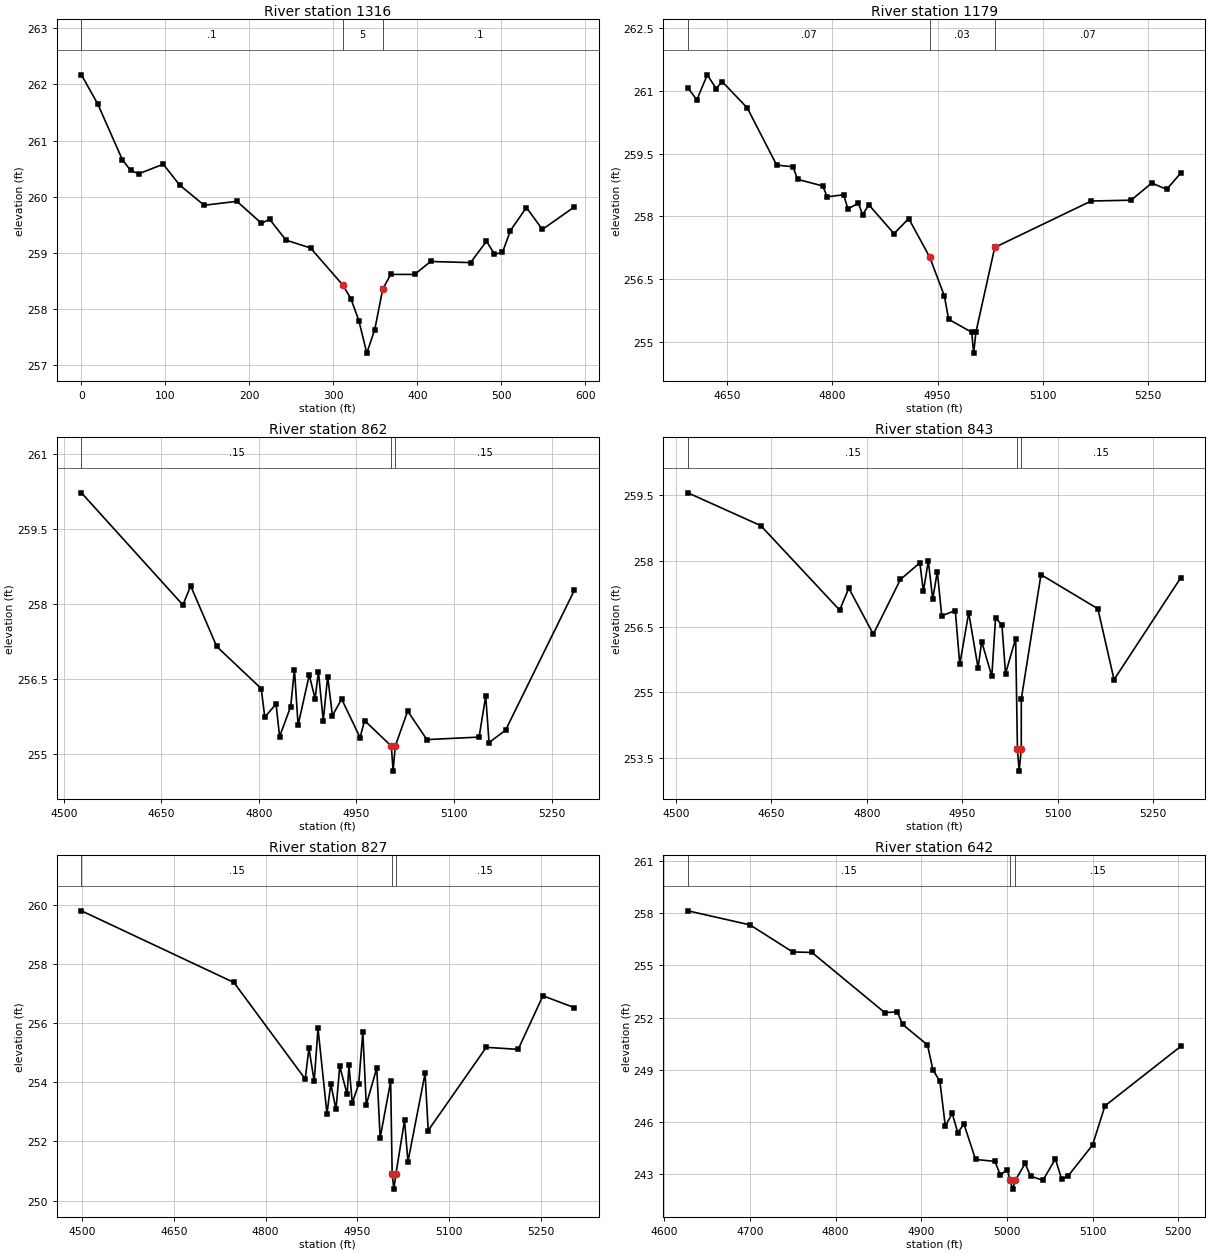
Type RM Length L Ch R = 1 ,1316    ,137,137,137
XS GIS Cut Line= 4
      3594789.45       10240220.     3594502.991    10240260.145
     3594432.462     10240338.27     3594430.292    10240528.157
#Sta/Elev= 30
       0  262.17   19.48  261.65    48.7  260.66   58.44  260.47   68.18  260.41
    97.4  260.58  116.88  260.21   146.1  259.85  185.05  259.92  214.27  259.53
  224.01   259.6  243.49  259.23  272.71  259.09  311.18  258.43  320.68  258.19
  330.17   257.8  339.67  257.22  349.16  257.64  358.66  258.36  368.15  258.62
  396.64  258.62  415.64  258.85  463.15  258.83  482.16  259.21  491.66  258.98
  501.16  259.01  510.66   259.4  529.67  259.81  548.67  259.42  586.68  259.82
#Mann= 3 , 0 , 0
       0      .1       0  311.18       5       0  358.66      .1       0
Bank Sta=311.18,358.66
XS Rating Curve= 0 ,0
Exp/Cntr=0.3,0.1

Type RM Length L Ch R = 1 ,1179    ,317,317,317
BEGIN DESCRIPTION:
Mapping XS c86f55f2
END DESCRIPTION:
XS GIS Cut Line= 2
     3594583.287    10239891.221     3594186.151    10240465.223
#Sta/Elev= 30
  4594.8  261.08  4607.5  260.79  4622.4  261.39    4635  261.06  4643.4  261.23
  4679.2   260.6  4721.1  259.23  4744.4  259.19  4750.8  258.89  4786.7  258.73
    4793  258.47  4816.4  258.52  4822.5  258.18  4837.4  258.32  4843.4  258.04
  4852.2  258.28  4888.1  257.59    4909  257.95  4938.8  257.03  4959.7   256.1
  4965.8  255.54  4998.6  255.23  5001.4  254.73  5004.6  255.23  5031.4  257.26
  5168.6  258.37  5225.4  258.39  5254.8   258.8  5276.1  258.65  5296.1  259.04
#Mann= 3 , 0 , 0
  4594.8     .07       0  4938.8     .03       0  5031.4     .07       0
Bank Sta=4938.8,5031.4
XS Rating Curve= 0 ,0
Exp/Cntr=0.3,0.1

Type RM Length L Ch R = 1 ,862     ,19,19,19
BEGIN DESCRIPTION:
Mapping XS 3decdb00
END DESCRIPTION:
XS GIS Cut Line= 6
      3594473.24     10239847.09      3594150.28     10239999.03
      3594075.63     10240078.89        3594060.     10240134.45
      3594061.74     10240210.84      3594093.81     10240364.98
#Sta/Elev= 30
  4527.1  260.22  4683.1  257.98  4695.1  258.36  4735.1  257.15  4803.5  256.31
    4809  255.74  4826.3     256  4831.8  255.35  4848.8  255.95  4854.6  256.69
  4860.2  255.58  4877.4  256.58  4886.3  256.11  4891.5  256.64  4898.9  255.67
  4905.7  256.55    4913  255.77  4927.2   256.1  4955.5  255.33  4962.4  255.67
  5003.6  255.16  5006.3  254.66  5009.6  255.16  5028.7  255.86  5058.2  255.29
  5138.5  255.34  5148.7  256.16  5153.8  255.23  5179.3  255.48  5284.9  258.27
#Mann= 3 ,-1 , 0
  4527.1     .15       0  5003.6     .07       0  5009.6     .15       0
Bank Sta=5003.6,5009.6
XS Rating Curve= 0 ,0
Exp/Cntr=0.3,0.1

Type RM Length L Ch R = 1 ,843     ,16,16,16
BEGIN DESCRIPTION:
Mapping XS 704bd9aa
END DESCRIPTION:
XS GIS Cut Line= 6
      3594453.75     10239821.02      3594188.48      10239959.1
      3594127.71      10239997.3      3594070.42     10240052.85
      3594033.96     10240117.09      3594063.13     10240365.77
#Sta/Elev= 30
  4518.6  259.56  4633.2  258.81  4757.2  256.88  4771.6  257.38  4810.1  256.33
  4852.7  257.58  4883.3  257.96  4888.8  257.31  4896.6     258  4903.5  257.13
  4910.7  257.76  4917.7  256.75    4939  256.87    4946  255.64  4960.1  256.82
  4974.8  255.56  4980.5  256.16  4996.4  255.37  5002.3   256.7  5012.3  256.54
    5018  255.43  5033.9  256.23  5036.7   253.7  5039.4   253.2  5042.7   253.7
  5042.8  254.85  5073.7  257.69  5163.2  256.91  5188.6  255.29  5293.5  257.62
#Mann= 3 ,-1 , 0
  4518.6     .15       0  5036.7     .07       0  5042.7     .15       0
Bank Sta=5036.7,5042.7
XS Rating Curve= 0 ,0
Exp/Cntr=0.3,0.1

Type RM Length L Ch R = 1 ,827     ,185,185,185
BEGIN DESCRIPTION:
Mapping XS 080d8b92
END DESCRIPTION:
XS GIS Cut Line= 6
      3594445.09     10239799.31       3594160.7     10239948.68
      3594068.69     10240014.66      3594020.07     10240117.09
      3594009.66     10240181.32      3594037.09     10240372.29
#Sta/Elev= 30
  4498.8  259.79  4748.1  257.37  4864.7  254.11  4870.8  255.15  4879.4  254.03
  4885.6  255.82  4900.3  252.93  4906.5  253.95    4915  253.08  4921.2  254.54
  4933.3  253.59  4936.2  254.57  4941.7  253.31  4952.1  253.93  4958.9  255.69
  4964.5  253.24  4981.7  254.48  4987.2  252.12  5004.4  254.03  5006.9  250.89
  5009.7  250.39  5012.9  250.89  5027.1  252.71  5032.7  251.32  5060.7   254.3
  5065.8  252.37  5160.7  255.18  5212.9  255.11  5253.4  256.92  5304.7  256.52
#Mann= 3 ,-1 , 0
  4498.8     .15       0  5006.9     .07       0  5012.9     .15       0
Bank Sta=5006.9,5012.9
XS Rating Curve= 0 ,0
Exp/Cntr=0.3,0.1

Type RM Length L Ch R = 1 ,642     ,107,107,107
BEGIN DESCRIPTION:
Mapping XS ff8c282f
END DESCRIPTION:
XS GIS Cut Line= 3
       3594156.3     10239793.62      3593752.22     10240108.49
      3593767.53     10240169.73
#Sta/Elev= 30
  4627.5  258.15    4700  257.34  4749.8  255.78  4772.3  255.75  4857.4  252.28
  4871.9  252.33  4878.2   251.6  4907.2  250.42  4913.5  248.99  4921.7  248.32
    4928  245.75  4936.1  246.47  4942.5  245.37  4949.8  245.86  4963.3  243.82
  4985.9  243.71  4992.2  242.92  5000.4  243.24  5003.7  242.61  5006.5  242.11
  5009.7  242.61  5021.2  243.59  5027.5  242.86    5042  242.62  5056.5  243.85
  5063.9  242.68  5070.9  242.84  5099.9  244.65  5114.4  246.91  5202.9  250.34
#Mann= 3 ,-1 , 0
  4627.5     .15       0  5003.7     .07       0  5009.7     .15       0
Bank Sta=5003.7,5009.7
XS Rating Curve= 0 ,0
Exp/Cntr=0.3,0.1

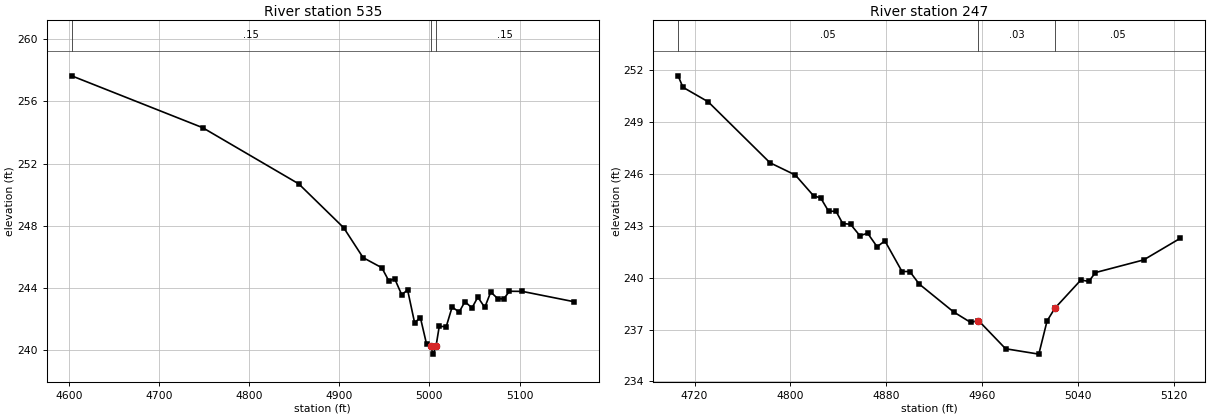
Type RM Length L Ch R = 1 ,535     ,288,288,288
BEGIN DESCRIPTION:
Mapping XS a23d049e
END DESCRIPTION:
XS GIS Cut Line= 2
      3594061.85     10239735.89      3593637.76     10240097.15
#Sta/Elev= 30
  4603.1  257.64  4748.4  254.31    4855   250.7  4904.9  247.88  4926.4  245.96
  4947.2  245.31  4954.9  244.47  4961.5   244.6  4969.2  243.58  4975.8  243.88
  4983.5  241.79    4990   242.1  4996.9  240.38  5001.3  240.26  5004.1  239.76
  5007.3  240.26  5010.9  241.55  5018.6  241.52  5025.2  242.79  5032.9  242.46
  5039.4  243.13  5047.2  242.73  5053.7  243.42  5061.4  242.76    5068  243.75
  5075.7  243.33  5082.3   243.3  5088.8   243.8  5103.1  243.79  5160.2  243.13
#Mann= 3 ,-1 , 0
  4603.1     .15       0  5001.3     .07       0  5007.3     .15       0
Bank Sta=5001.3,5007.3
XS Rating Curve= 0 ,0
Exp/Cntr=0.3,0.1

Type RM Length L Ch R = 1 ,247     ,0,0,0
BEGIN DESCRIPTION:
UNT003 IN WICK 1.0
END DESCRIPTION:
XS GIS Cut Line= 4
       3593459.4     10239793.49      3593389.98     10239901.96
      3593526.69     10240066.89       3593602.6      10240073.4
#Sta/Elev= 30
  4706.3  251.65  4710.3  250.99  4731.4  250.15    4783  246.63  4804.2  245.92
  4819.4  244.72  4825.3   244.6  4831.9  243.83  4838.1  243.83  4843.7  243.12
  4850.2  243.08    4858  242.42  4864.5  242.56  4872.4  241.78  4878.9  242.12
  4893.2  240.35  4899.7  240.35  4907.5  239.63  4936.2  238.02  4950.5  237.41
    4957  237.52 4979.67  235.89 5007.39  235.58  5014.3   237.5  5020.8  238.23
  5042.5  239.86  5049.1  239.78  5054.7  240.29  5094.9  241.02  5125.5  242.27
#Mann= 3 , 0 , 0
  4706.3     .05       0    4957     .03       0  5020.8     .05       0
Bank Sta=4957,5020.8
XS Rating Curve= 0 ,0
Exp/Cntr=0.3,0.1

Chan Stop Cuts=-1
Use User Specified Reach Order=0
Composite Channel Slope=5