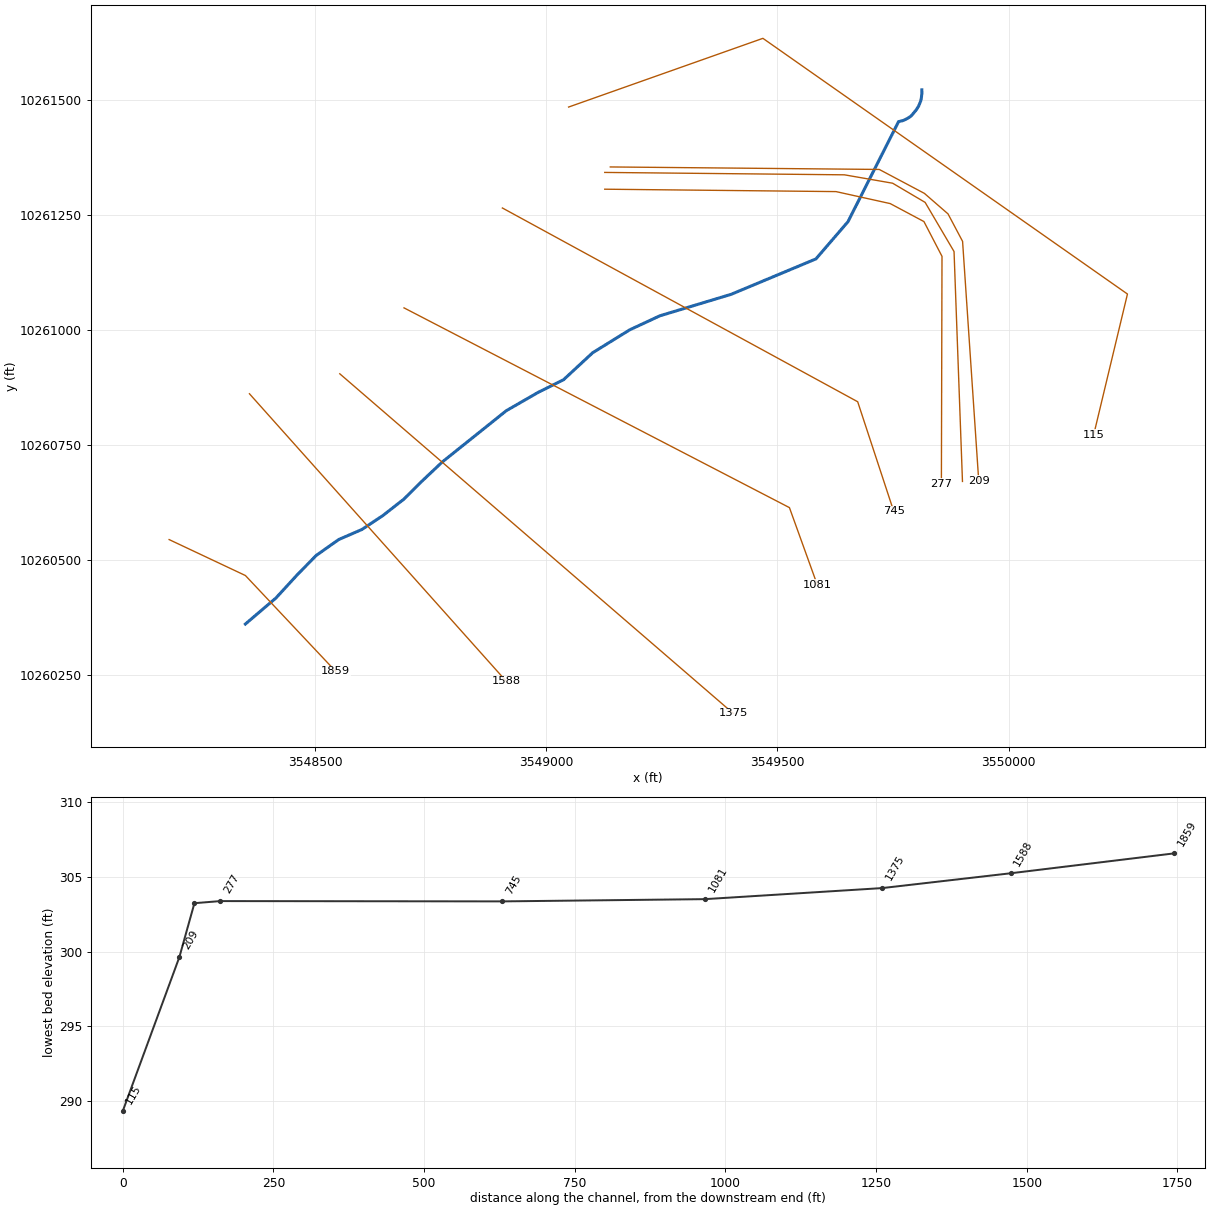
--- UNT013 IN WICK.prj (project) ---

Proj Title=UNT013 IN WICK Base Level Engineering
Current Plan=p01
Default Exp/Contr=0.3,0.1
English Units
Geom File=g01
Flow File=f01
Plan File=p01
BEGIN DESCRIPTION:
UNT013 IN WICK
END DESCRIPTION:

--- UNT013 IN WICK.p01 (plan) ---

Plan Title=Multiple Run
Short Identifier=Multiple
Geom File=g01
Flow File=f01
Subcritical Flow
K Sum by GR= 0
Std Step Tol= 0.01
Critical Tol= 0.01
Num of Std Step Trials= 20
Max Error Tol= 0.3
Flow Tol Ratio= 0.001
Split Flow NTrial= 30
Split Flow Tol= 0.02
Split Flow Ratio= 0.02
Log Output Level= 0
Friction Slope Method= 1
Unsteady Friction Slope Method= 2
Unsteady Bridges Friction Slope Method= 1
Parabolic Critical Depth
Global Vel Dist=  1 , 1 , 1
Global Log Level= 0
CheckData=True
Encroach Param= -1, 0, 0, 0
BEGIN DESCRIPTION:
Multiple Run
END DESCRIPTION:

--- UNT013 IN WICK.f01 (steady flow) ---

Flow Title=Multiple
Number of Profiles=7
Profile Names=10-year,25-year,50-year,1pct_min,100-year,1pct_plu,500-year
River Rch & RM= UNT013 IN WICK,Reach-1,1859
     170     214     248     212     286     387     381
River Rch & RM= UNT013 IN WICK,Reach-1,234
    3314    4757    5999    5507    7448   10073   11521
Boundary for River Rch & Prof#=UNT013 IN WICK,Reach-1,1
Up Type=0
Dn Type=3
Dn Slope=0.005
Boundary for River Rch & Prof#=UNT013 IN WICK,Reach-1,2
Up Type=0
Dn Type=3
Dn Slope=0.005
Boundary for River Rch & Prof#=UNT013 IN WICK,Reach-1,3
Up Type=0
Dn Type=3
Dn Slope=0.005
Boundary for River Rch & Prof#=UNT013 IN WICK,Reach-1,4
Up Type=0
Dn Type=3
Dn Slope=0.005
Boundary for River Rch & Prof#=UNT013 IN WICK,Reach-1,5
Up Type=0
Dn Type=3
Dn Slope=0.005
Boundary for River Rch & Prof#=UNT013 IN WICK,Reach-1,6
Up Type=0
Dn Type=3
Dn Slope=0.005
Boundary for River Rch & Prof#=UNT013 IN WICK,Reach-1,7
Up Type=0
Dn Type=3
Dn Slope=0.005

--- UNT013 IN WICK.g01 (geometry) ---

Geom Title=Existing Conditions

River Reach=UNT013 IN WICK,Reach-1
Reach XY= 30
      3548349.55     10260360.91      3548415.74     10260417.56
      3548461.32     10260467.47      3548502.55     10260509.79
      3548551.38     10260544.51      3548601.29     10260566.21
      3548646.86     10260596.59      3548692.44     10260632.40
      3548731.50     10260671.46      3548774.90     10260712.69
      3548913.79     10260824.46      3548983.23     10260864.60
      3549037.49     10260891.73      3549100.42     10260950.32
      3549180.72     10261000.24      3549245.82     10261030.62
      3549399.90     10261077.28      3549583.18     10261154.24
      3549652.40     10261235.09      3549761.79     10261452.44
      3549770.79     10261454.61      3549774.73     10261456.20
      3549782.08     10261460.07      3549789.02     10261464.75
      3549799.79     10261477.68      3549805.23     10261486.40
      3549809.60     10261497.11      3549810.99     10261503.07
      3549812.17     10261513.88      3549812.11     10261521.64

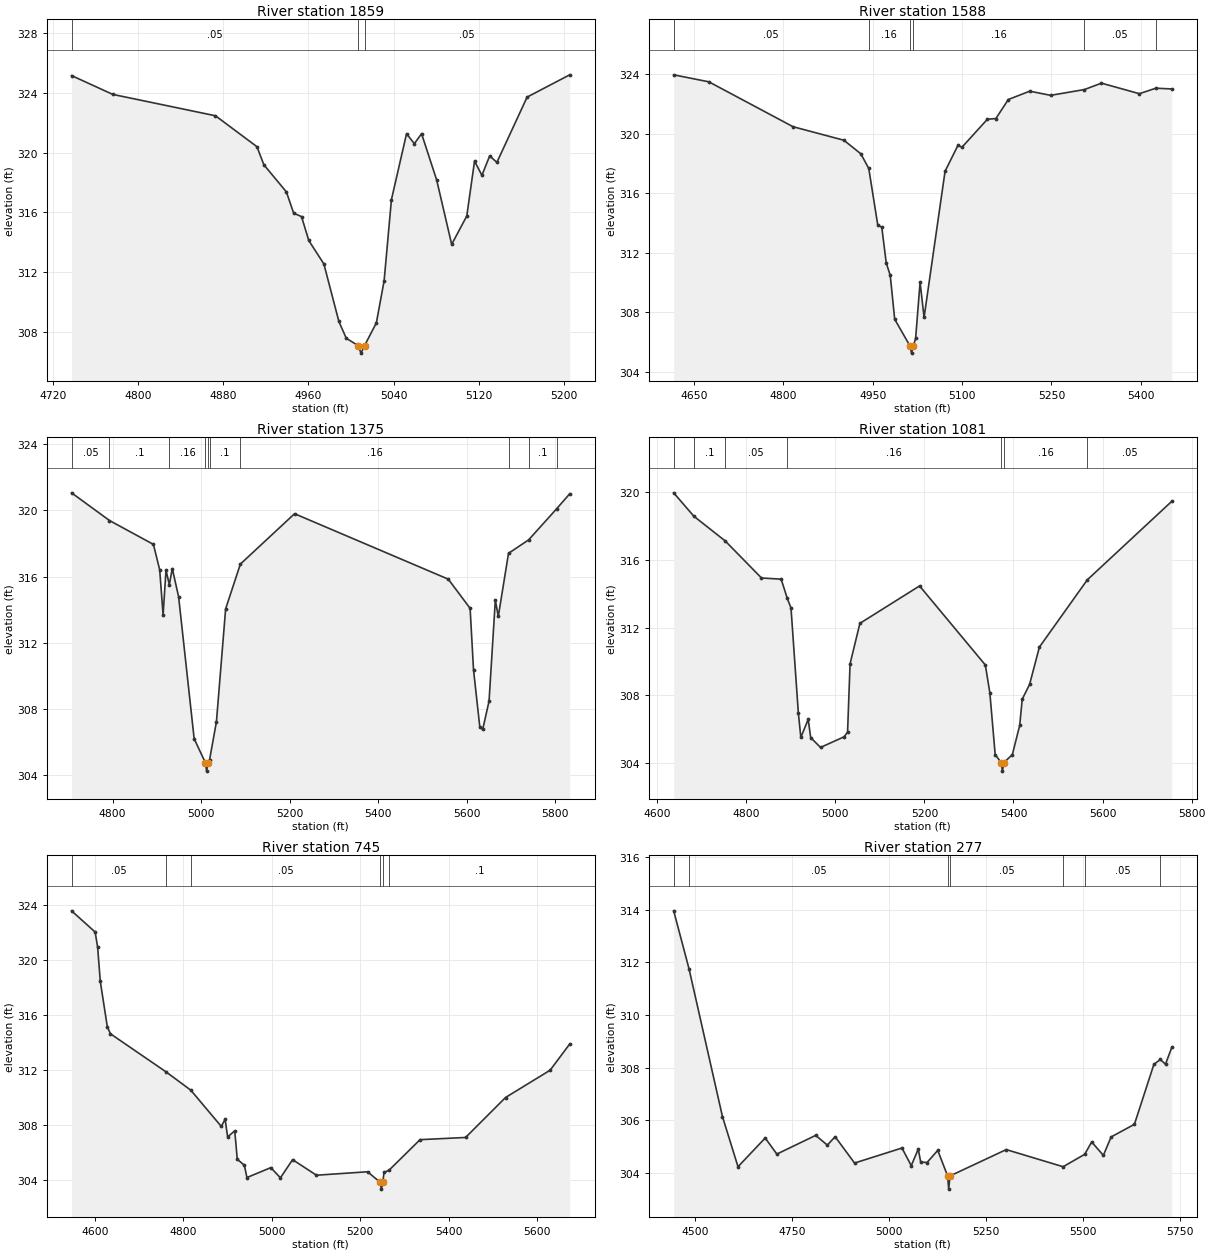
Type RM Length L Ch R = 1,1859,271,271,271
BEGIN DESCRIPTION:
UNT013 IN WICK 5.0
END DESCRIPTION:
XS GIS Cut Line= 3
      3548184.68     10260544.40      3548349.64     10260466.26
      3548544.95     10260257.93
#Sta/Elev= 30
  4737.4  325.16  4776.1  323.90  4872.6  322.47  4911.6  320.40  4918.1  319.19
  4939.3  317.37  4946.1  315.95  4953.5  315.72  4960.3  314.12  4974.5  312.55
  4988.6  308.70  4995.5  307.58  5006.7  307.08  5009.4  306.58  5012.7  307.08
  5023.8  308.60  5031.1  311.41  5038.0  316.86  5052.2  321.27  5059.5  320.60
  5066.3  321.27  5080.5  318.17  5094.6  313.86  5108.8  315.76  5116.1  319.44
  5123.0  318.48  5130.3  319.78  5137.1  319.35  5165.5  323.72  5205.5  325.21
#Mann=3,-1,0
  4737.4    0.05       0  5006.7    0.03       0  5012.7    0.05       0
Bank Sta=5006.7,5012.7
Exp/Cntr=0.3,0.1

Type RM Length L Ch R = 1,1588,213,213,213
BEGIN DESCRIPTION:
UNT013 IN WICK 4.0
END DESCRIPTION:
XS GIS Cut Line= 2
      3548358.34     10260861.21      3548913.68     10260236.45
#Sta/Elev= 30
  4616.1  323.97  4675.1  323.50  4816.4  320.48  4901.7  319.57  4930.1  318.66
  4943.5  317.67  4958.6  313.86  4965.3  313.72  4972.8  311.32  4979.5  310.48
  4987.0  307.53  5012.4  305.75  5015.2  305.25  5018.4  305.75  5022.1  306.24
  5029.6  310.02  5036.3  307.65  5071.5  317.48  5093.2  319.23  5099.9  319.10
  5142.5  320.98  5156.8  321.03  5177.7  322.31  5213.6  322.87  5248.7  322.59
  5305.4  322.98  5334.0  323.41  5397.6  322.70  5425.2  323.07  5452.0  323.02
#Mann=6,-1,0
  4616.1    0.05       0  4943.5    0.16       0  5012.4    0.07       0
  5018.4    0.16       0  5305.4    0.05       0  5425.2    0.16       0
Bank Sta=5012.4,5018.4
Exp/Cntr=0.3,0.1

Type RM Length L Ch R = 1,1375,294,294,294
BEGIN DESCRIPTION:
Mapping XS 355a6dfb
END DESCRIPTION:
XS GIS Cut Line= 2
      3548553.64     10260904.62      3549404.34     10260166.77
#Sta/Elev= 30
  4707.1  321.05  4792.8  319.38  4892.1  317.94  4906.3  316.41  4914.0  313.68
  4920.6  316.38  4928.1  315.51  4934.8  316.48  4949.1  314.78  4984.2  306.22
  5009.7  304.76  5012.4  304.26  5015.7  304.76  5019.2  304.96  5034.6  307.24
  5055.4  314.05  5088.7  316.75  5211.2  319.79  5558.8  315.84  5608.1  314.08
  5615.8  310.37  5630.0  306.93  5636.6  306.78  5650.9  308.48  5665.1  314.58
  5671.8  313.59  5694.9  317.40  5740.3  318.21  5804.1  320.10  5833.2  320.99
#Mann=10,-1,0
  4707.1    0.05       0  4792.8     0.1       0  4928.1    0.16       0
  5009.7    0.07       0  5015.7    0.16       0  5019.2     0.1       0
  5088.7    0.16       0  5694.9    0.05       0  5740.3     0.1       0
  5804.1    0.05       0
Bank Sta=5009.7,5015.7
Exp/Cntr=0.3,0.1

Type RM Length L Ch R = 1,1081,336,336,336
BEGIN DESCRIPTION:
Mapping XS bac942bc
END DESCRIPTION:
XS GIS Cut Line= 3
      3548692.56     10261047.83      3549525.86     10260613.83
      3549586.25     10260445.58
#Sta/Elev= 30
  4637.1  319.96  4682.3  318.58  4752.7  317.12  4834.2  314.93  4878.4  314.86
  4892.2  313.72  4900.5  313.16  4917.0  306.95  4922.6  305.51  4939.1  306.58
  4944.7  305.50  4966.8  304.92  5019.9  305.55  5027.5  305.83  5033.1  309.86
  5055.2  312.25  5189.1  314.46  5336.8  309.79  5346.9  308.15  5358.9  304.50
  5372.4  304.02  5375.2  303.52  5378.4  304.02  5397.5  304.50  5414.0  306.23
  5419.6  307.77  5436.1  308.64  5458.2  310.85  5565.7  314.82  5755.4  319.46
#Mann=7,-1,0
  4637.1    0.05       0  4682.3     0.1       0  4752.7    0.05       0
  4892.2    0.16       0  5372.4    0.07       0  5378.4    0.16       0
  5565.7    0.05       0
Bank Sta=5372.4,5378.4
Exp/Cntr=0.3,0.1

Type RM Length L Ch R = 1,745,468,468,468
BEGIN DESCRIPTION:
Mapping XS fe905105
END DESCRIPTION:
XS GIS Cut Line= 3
      3548905.20     10261264.87      3549673.43     10260843.86
      3549751.30     10260605.91
#Sta/Elev= 30
  4547.6  323.57  4600.9  322.03  4606.6  320.91  4612.5  318.46  4628.4  315.16
  4635.3  314.65  4761.3  311.88  4817.3  310.55  4886.2  307.92  4894.8  308.45
  4900.5  307.16  4916.6  307.60  4922.3  305.54  4938.4  305.10  4944.1  304.21
  4998.1  304.93  5019.9  304.19  5047.4  305.51  5101.4  304.38  5216.9  304.63
  5245.4  303.87  5248.1  303.37  5251.4  303.87  5254.1  304.58  5265.4  304.74
  5335.6  306.96  5438.6  307.12  5528.9  310.02  5629.7  312.00  5674.0  313.90
#Mann=6,-1,0
  4547.6    0.05       0  4761.3     0.1       0  4817.3    0.05       0
  5245.4   0.033       0  5251.4    0.05       0  5265.4     0.1       0
Bank Sta=5245.4,5251.4
Exp/Cntr=0.3,0.1

Type RM Length L Ch R = 1,277,43,43,43
BEGIN DESCRIPTION:
UNT013 IN WICK 3.0
END DESCRIPTION:
XS GIS Cut Line= 6
      3549126.52     10261305.67      3549626.55     10261300.46
      3549743.74     10261274.42      3549816.66     10261235.36
      3549855.72     10261159.83      3549854.41     10260665.40
#Sta/Elev= 30
  4445.8  313.95  4485.3  311.75  4571.4  306.14  4611.4  304.24  4681.4  305.33
  4711.4  304.72  4811.4  305.43  4841.4  305.06  4861.4  305.38  4911.4  304.38
  5033.5  304.95  5057.4  304.28  5075.4  304.91  5081.7  304.42  5098.0  304.40
  5125.6  304.86  5151.0  303.89  5153.8  303.39  5157.0  303.89  5301.9  304.89
  5448.4  304.24  5503.8  304.71  5521.9  305.18  5551.9  304.67  5571.9  305.37
  5631.9  305.85  5681.9  308.12  5698.5  308.31  5711.9  308.13  5728.1  308.77
#Mann=7,-1,0
  4445.8     0.1       0  4485.3    0.05       0  5151.0   0.033       0
  5157.0    0.05       0  5448.4     0.1       0  5503.8    0.05       0
  5698.5     0.1       0
Bank Sta=5151,5157
Exp/Cntr=0.3,0.1

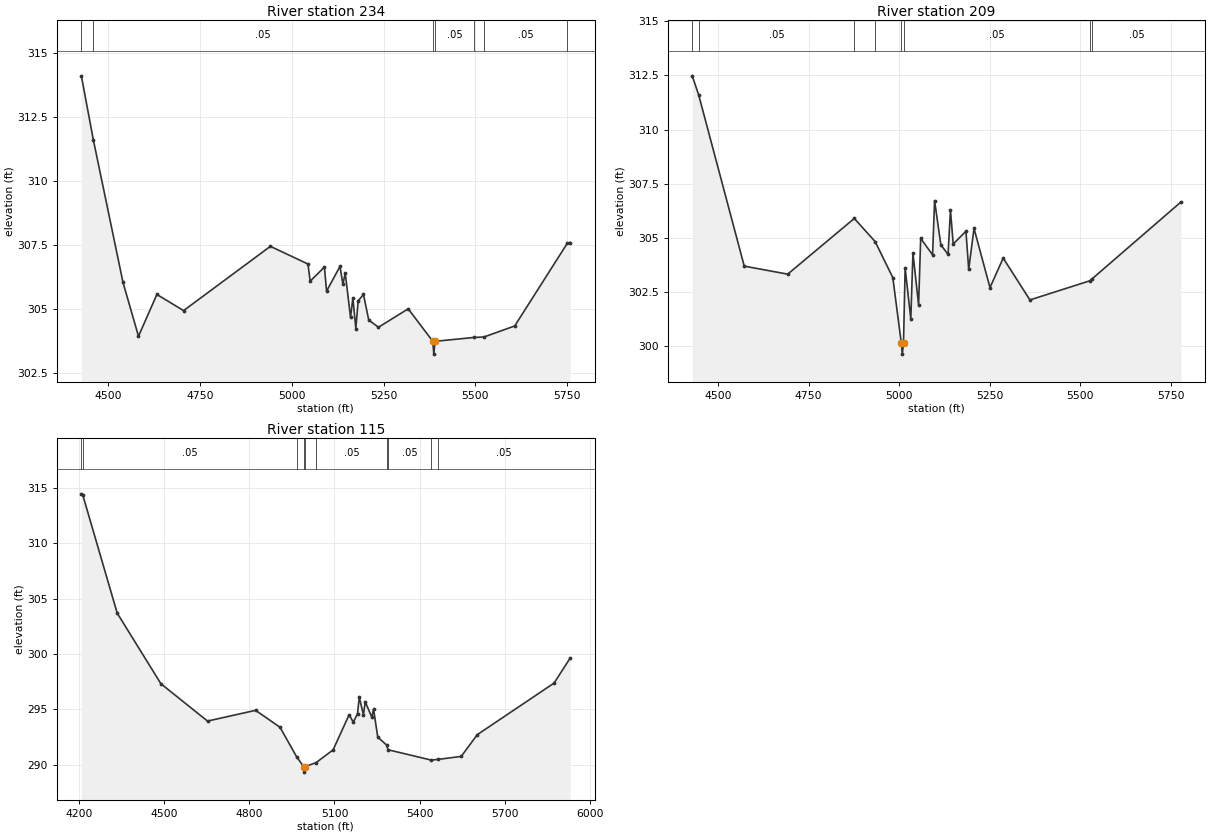
Type RM Length L Ch R = 1,234,25,25,25
BEGIN DESCRIPTION:
UNT013 IN WICK 2.0
END DESCRIPTION:
XS GIS Cut Line= 6
      3549126.54     10261342.13      3549644.78     10261336.92
      3549748.95     10261318.69      3549819.26     10261277.02
      3549881.76     10261170.25      3549899.98     10260670.70
#Sta/Elev= 30
  4426.4  314.12  4458.9  311.63  4539.9  306.05  4582.1  303.95  4632.2  305.58
  4705.0  304.95  4941.5  307.46  5043.9  306.77  5049.9  306.10  5088.8  306.65
  5094.6  305.71  5131.3  306.68  5139.1  305.98  5145.5  306.42  5159.9  304.69
  5166.3  305.44  5174.4  304.25  5180.7  305.33  5195.2  305.58  5209.6  304.58
  5236.1  304.30  5317.1  305.02  5384.1  303.75  5386.9  303.25  5390.1  303.75
  5495.6  303.90  5523.6  303.92  5607.3  304.35  5751.1  307.59  5758.3  307.61
#Mann=7,-1,0
  4426.4     0.1       0  4458.9    0.05       0  5384.1   0.033       0
  5390.1    0.05       0  5495.6     0.1       0  5523.6    0.05       0
  5751.1     0.1       0
Bank Sta=5384.1,5390.1
Exp/Cntr=0.3,0.1

Type RM Length L Ch R = 1,209,94,94,94
BEGIN DESCRIPTION:
Mapping XS 606bd1e0
END DESCRIPTION:
XS GIS Cut Line= 6
      3549138.49     10261354.03      3549720.08     10261348.60
      3549817.74     10261296.52      3549868.74     10261252.03
      3549900.21     10261192.35      3549935.13     10260672.03
#Sta/Elev= 30
  4428.7  312.48  4446.5  311.60  4572.3  303.70  4692.3  303.33  4876.1  305.90
  4933.7  304.83  4982.4  303.17  5005.9  300.14  5008.6  299.64  5011.9  300.14
  5016.4  303.61  5032.1  301.26  5037.9  304.31  5053.6  301.91  5059.3  304.98
  5092.2  304.22  5097.7  306.72  5115.0  304.68  5134.9  304.24  5141.5  306.29
  5149.1  304.72  5184.2  305.31  5191.9  303.55  5206.5  305.44  5250.6  302.71
  5287.1  304.07  5360.8  302.14  5525.6  303.02  5532.2  303.11  5777.8  306.66
#Mann=8,-1,0
  4428.7     0.1       0  4446.5    0.05       0  4876.1    0.16       0
  4933.7    0.05       0  5005.9   0.033       0  5011.9    0.05       0
  5525.6     0.1       0  5532.2    0.05       0
Bank Sta=5005.9,5011.9
Exp/Cntr=0.3,0.1

Type RM Length L Ch R = 1,115,0,0,0
BEGIN DESCRIPTION:
UNT013 IN WICK 1.0
END DESCRIPTION:
XS GIS Cut Line= 4
      3549048.39     10261484.17      3549468.49     10261633.47
      3550256.69     10261077.91      3550183.77     10260772.35
#Sta/Elev= 30
  4207.0  314.46  4212.0  314.35  4333.4  303.69  4487.7  297.31  4652.1  293.94
  4821.7  294.91  4907.9  293.38  4966.1  290.73  4991.1  289.83  4993.8  289.33
  4997.1  289.83  5035.2  290.19  5095.1  291.34  5151.7  294.51  5166.5  293.84
  5181.3  294.62  5187.4  296.09  5202.2  294.52  5208.4  295.68  5231.8  294.29
  5237.9  295.01  5252.7  292.49  5283.7  291.78  5289.1  291.35  5440.8  290.42
  5465.9  290.48  5547.1  290.75  5603.7  292.71  5874.7  297.37  5931.3  299.62
#Mann=10,-1,0
  4207.0     0.1       0  4212.0    0.05       0  4966.1    0.16       0
  4991.1    0.07       0  4997.1    0.16       0  5035.2    0.05       0
  5283.7    0.16       0  5289.1    0.05       0  5440.8    0.16       0
  5465.9    0.05       0
Bank Sta=4991.1,4997.1
Exp/Cntr=0.3,0.1

Chan Stop Cuts=-1