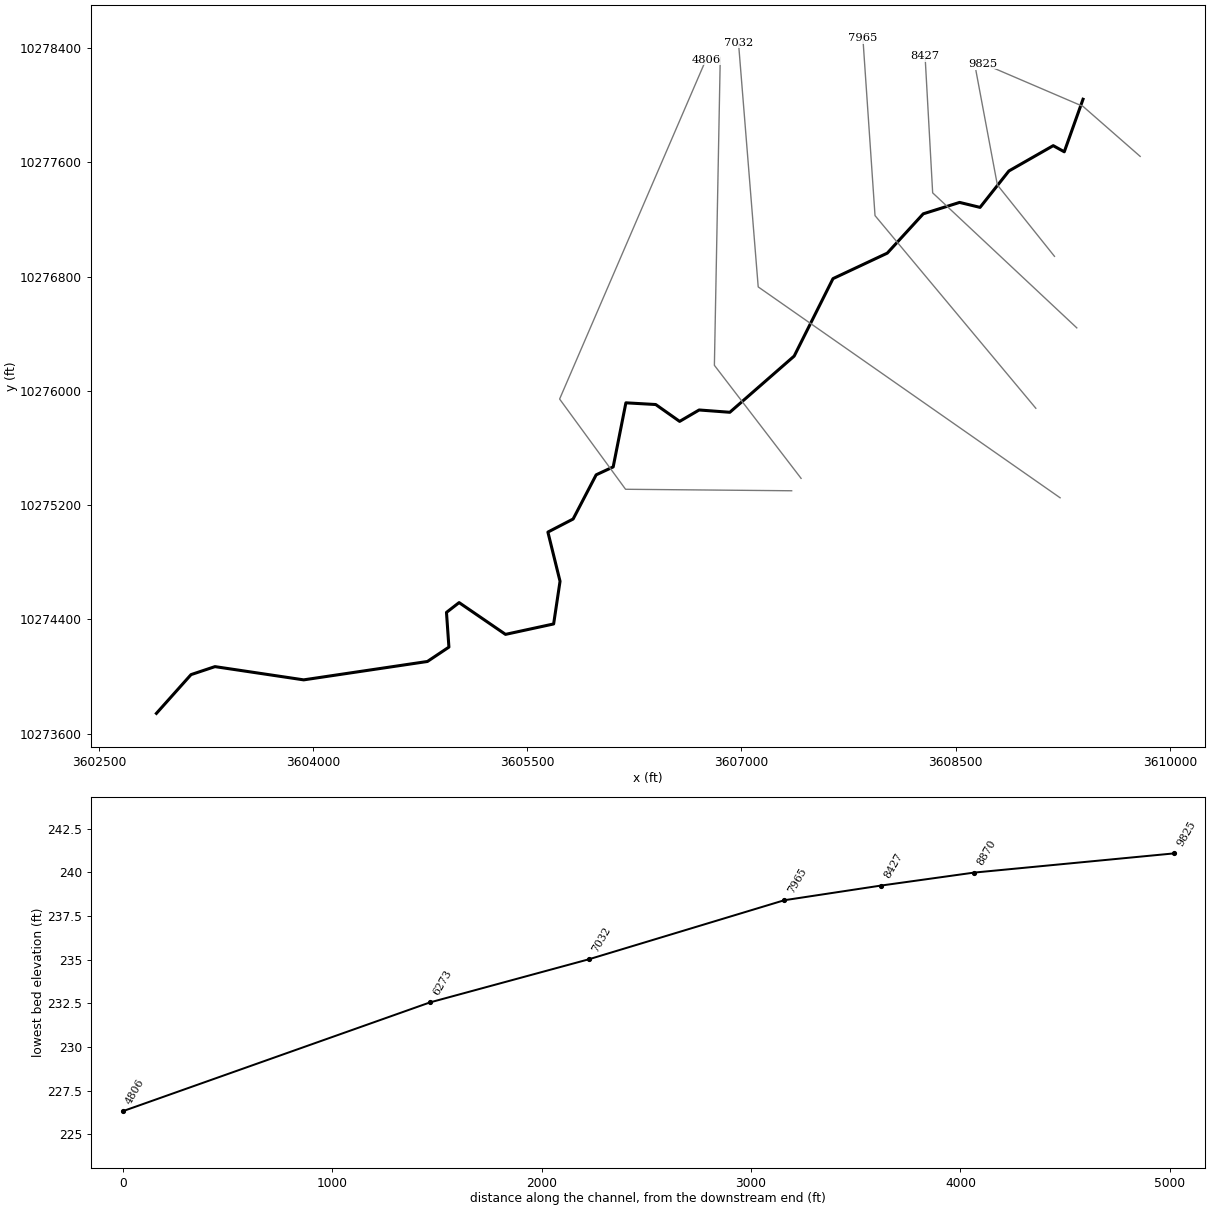
--- UNT0464 IN WICK.prj (project) ---

Proj Title=UNT0464 IN WICK Base Level Engineering
Current Plan=p01
Default Exp/Contr=0.3,0.1
English Units
Geom File=g01
Flow File=f01
Plan File=p01
Y Axis Title=Elevation
X Axis Title(PF)=Main Channel Distance
X Axis Title(XS)=Station
BEGIN DESCRIPTION:
UNT0464 IN WICK
END DESCRIPTION:
DSS Export Rating Curves= 0
DSS Export Rating Curve Sorted= 0
DSS Export Volume Flow Curves= 0
DXF OffsetX= 0
DXF OffsetY= 0
DXF ScaleX= 1
DXF ScaleY= 10

--- UNT0464 IN WICK.p01 (plan) ---

Plan Title=Multiple Run
Short Identifier=Multiple
Geom File=g01
Flow File=f01
Subcritical Flow
K Sum by GR= 0
Std Step Tol= 0.01
Critical Tol= 0.01
Num of Std Step Trials= 20
Max Error Tol= 0.3
Flow Tol Ratio= 0.001
Split Flow NTrial= 30
Split Flow Tol= 0.02
Split Flow Ratio= 0.02
Log Output Level= 0
Friction Slope Method= 1
Unsteady Friction Slope Method= 2
Unsteady Bridges Friction Slope Method= 1
Parabolic Critical Depth
Global Vel Dist=  1 , 1 , 1
Global Log Level= 0
CheckData=True
Encroach Param= -1, 0, 0, 0
BEGIN DESCRIPTION:
Multiple Run
END DESCRIPTION:

--- UNT0464 IN WICK.f01 (steady flow) ---

Flow Title=Multiple
Number of Profiles=7
Profile Names=10-year,25-year,50-year,1pct_min,100-year,1pct_plu,500-year
River Rch & RM= UNT0464 IN WICK,Reach-1,9825
     972    1330    1624    1451    1962    2654    2870
Boundary for River Rch & Prof#=UNT0464 IN WICK,Reach-1,1
Up Type=0
Dn Type=3
Dn Slope=0.005
Boundary for River Rch & Prof#=UNT0464 IN WICK,Reach-1,2
Up Type=0
Dn Type=3
Dn Slope=0.005
Boundary for River Rch & Prof#=UNT0464 IN WICK,Reach-1,3
Up Type=0
Dn Type=3
Dn Slope=0.005
Boundary for River Rch & Prof#=UNT0464 IN WICK,Reach-1,4
Up Type=0
Dn Type=3
Dn Slope=0.005
Boundary for River Rch & Prof#=UNT0464 IN WICK,Reach-1,5
Up Type=0
Dn Type=3
Dn Slope=0.005
Boundary for River Rch & Prof#=UNT0464 IN WICK,Reach-1,6
Up Type=0
Dn Type=3
Dn Slope=0.005
Boundary for River Rch & Prof#=UNT0464 IN WICK,Reach-1,7
Up Type=0
Dn Type=3
Dn Slope=0.005

--- UNT0464 IN WICK.g01 (geometry) ---

Geom Title=Existing Conditions
Program Version=4.10

River Reach=UNT0464 IN WICK ,Reach-1
Reach XY= 30
      3609391.95     10278041.79      3609260.61     10277673.83
      3609183.23     10277716.76      3608872.83     10277539.42
      3608670.86     10277284.52       3608527.6     10277319.31
      3608273.03     10277239.41      3608021.17     10276964.12
      3607641.08     10276785.59      3607369.32     10276243.28
      3606918.65      10275849.7      3606703.58     10275865.77
       3606567.1      10275785.9      3606399.66     10275903.97
      3606190.76     10275915.93      3606101.78      10275467.1
      3605982.67     10275411.72      3605821.33      10275102.3
      3605644.61     10275010.68       3605729.6     10274666.21
      3605684.79     10274367.39       3605347.7     10274294.39
      3605022.82     10274516.94      3604934.41     10274448.25
      3604951.46     10274205.18      3604800.91     10274104.61
      3603934.44     10273975.86      3603313.26     10274068.59
      3603145.56     10274012.62      3602903.19     10273741.19

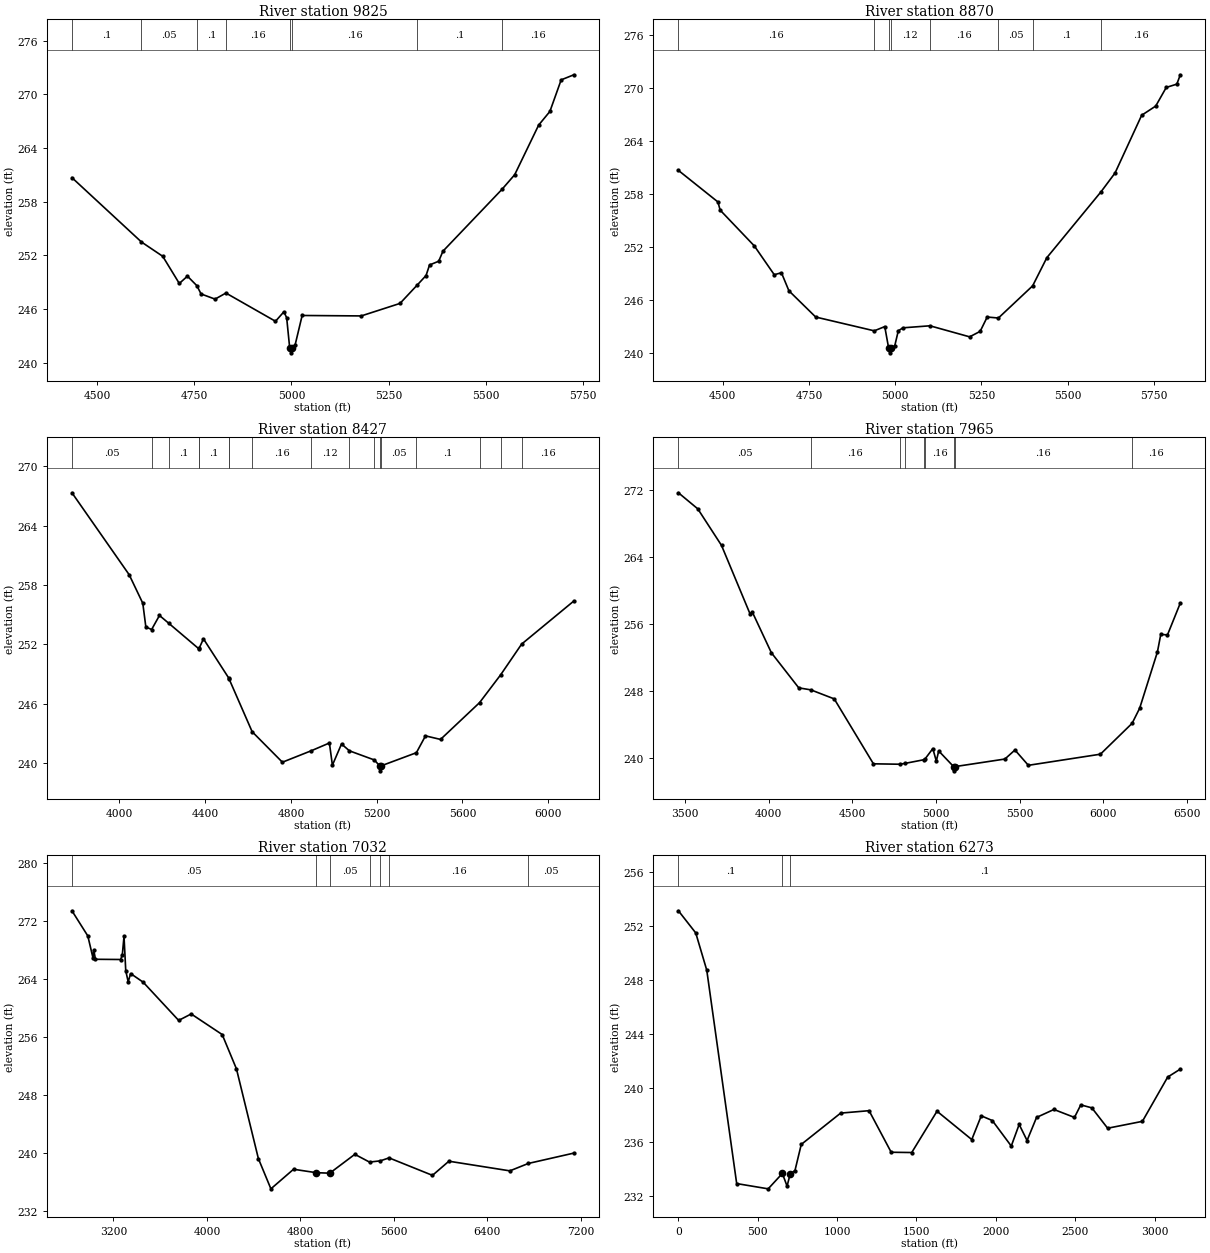
Type RM Length L Ch R = 1 ,9825    ,955,955,955
BEGIN DESCRIPTION:
UNT0464 IN WICK 12.0
END DESCRIPTION:
XS GIS Cut Line= 3
      3609792.08     10277641.66      3609392.11     10277991.64
      3608692.06     10278291.66
#Sta/Elev= 30
  4434.4  260.69  4613.5  253.49  4668.3  251.89    4711  248.85  4731.9  249.67
  4756.3   248.6    4767  247.68  4803.1   247.1  4831.1  247.78  4958.8  244.62
  4980.4  245.68  4987.6  245.02  4995.5  241.59  4998.3  241.09  5001.5  241.59
  5009.4  241.98  5027.5  245.27  5179.8  245.22  5279.6  246.62  5323.2  248.64
  5346.7  249.74  5355.7  250.92  5379.3  251.34  5390.2  252.46  5542.3  259.38
  5575.1  261.02  5636.8  266.57  5665.8   268.1  5694.8  271.63  5727.5   272.2
#Mann= 8 ,-1 , 0
  4434.4      .1       0  4613.5     .05       0  4756.3      .1       0
  4831.1     .16       0  4995.5     .07       0  5001.5     .16       0
  5323.2      .1       0  5542.3     .16       0
Bank Sta=4995.5,5001.5
XS Rating Curve= 0 ,0
Exp/Cntr=0.3,0.1

Type RM Length L Ch R = 1 ,8870    ,443,443,443
BEGIN DESCRIPTION:
UNT0464 IN WICK 10.0
END DESCRIPTION:
XS GIS Cut Line= 3
      3609192.11     10276941.64      3608792.11     10277441.64
       3608642.1     10278241.69
#Sta/Elev= 30
  4371.9  260.63  4486.4  257.06  4492.8  256.14    4592  252.08  4649.6  248.83
  4670.4  249.05  4692.1  247.01  4769.7  244.04  4939.4  242.48  4969.8  242.96
  4981.2  240.49  4983.9  239.99  4987.2  240.49  4998.6  240.76    5009  242.48
  5022.4  242.82  5100.7  243.05  5215.7   241.8  5246.2  242.42  5266.6  244.04
  5299.1  243.93  5398.3  247.57  5439.5  250.76  5596.8  258.23  5637.1  260.34
  5714.2  266.87  5754.9  267.91  5785.5  270.02    5816  270.39  5826.2  271.45
#Mann= 8 ,-1 , 0
  4371.9     .16       0  4939.4     .12       0  4981.2     .07       0
  4987.2     .12       0  5100.7     .16       0  5299.1     .05       0
  5398.3      .1       0  5596.8     .16       0
Bank Sta=4981.2,4987.2
XS Rating Curve= 0 ,0
Exp/Cntr=0.3,0.1

Type RM Length L Ch R = 1 ,8427    ,462,462,462
BEGIN DESCRIPTION:
UNT0464 IN WICK 8.0
END DESCRIPTION:
XS GIS Cut Line= 3
       3609348.3     10276440.77      3608339.03      10277386.3
      3608285.91     10278342.44
#Sta/Elev= 30
  3778.7  267.31  4045.6  259.04  4109.1  256.16  4123.3  253.77  4150.2  253.51
  4186.8  254.93  4229.7  254.15  4370.2  251.57  4372.1  251.63    4392  252.57
    4510  248.61    4511  248.55    4619   243.2  4760.1  240.12  4895.1  241.28
  4979.3  242.06  4993.3  239.82  5035.8  241.96  5072.6  241.27  5188.6  240.35
  5214.1  239.75  5216.9  239.25  5220.1  239.75    5385  241.08  5427.4  242.78
  5497.5  242.42  5679.5  246.13  5777.6  248.93  5875.8  252.04  6119.3  256.39
#Mann= 17 ,-1 , 0
  3778.7     .05       0  4150.2     .16       0  4229.7      .1       0
  4370.2     .16       0  4372.1      .1       0    4510     .16       0
    4511      .1       0    4619     .16       0  4895.1     .12       0
  5072.6     .16       0  5188.6     .05       0  5214.1     .07       0
  5220.1     .05       0    5385      .1       0  5679.5     .05       0
  5777.6      .1       0  5875.8     .16       0
Bank Sta=5214.1,5220.1
XS Rating Curve= 0 ,0
Exp/Cntr=0.3,0.1

Type RM Length L Ch R = 1 ,7965    ,933,933,933
BEGIN DESCRIPTION:
UNT0464 IN WICK 7.0
END DESCRIPTION:
XS GIS Cut Line= 3
       3609061.4     10275877.79      3607935.33     10277226.95
      3607850.46      10278468.3
#Sta/Elev= 30
  3460.1  271.65  3575.9  269.73  3717.8  265.36  3888.3  257.18  3902.6  257.37
  4015.9  252.53  4179.8  248.33  4252.2  248.09    4392  247.01  4626.3  239.25
  4782.6   239.2    4813  239.29  4928.7  239.74  4936.9  239.88  4981.6  241.07
  5002.4  239.57  5016.7  240.79  5106.1  238.91  5108.9  238.41  5112.1  238.91
  5412.6  239.82  5472.7   240.9  5552.9  239.07  5983.9   240.4  6173.4  244.09
  6218.5  245.89  6324.7  252.62  6344.8  254.72  6384.9  254.66  6461.7  258.47
#Mann= 9 ,-1 , 0
  3460.1     .05       0  4252.2     .16       0  4782.6     .05       0
    4813     .16       0  4928.7     .05       0  4936.9     .16       0
  5106.1     .07       0  5112.1     .16       0  6173.4     .16       0
Bank Sta=5106.1,5112.1
XS Rating Curve= 0 ,0
Exp/Cntr=0.3,0.1

Type RM Length L Ch R = 1 ,7032    ,759,759,759
BEGIN DESCRIPTION:
UNT0464 IN WICK 6.0
END DESCRIPTION:
XS GIS Cut Line= 3
      3609231.41     10275250.96      3607117.32     10276727.64
      3606979.27     10278437.32
#Sta/Elev= 30
  2845.4  273.38  2981.2  269.91  3025.7  266.85  3031.8  267.98  3046.6  266.69
  3261.2  266.66    3276  267.25  3290.8  269.85  3305.7  265.11  3326.6  263.58
  3347.5  264.72  3454.8  263.53  3758.4  258.26  3865.6  259.15  4130.8  256.31
  4252.9  251.57  4440.4   239.2  4547.5  235.03  4741.3  237.73    4935  237.26
    5051  237.19  5265.5  239.79  5391.1  238.72  5483.7  238.89  5558.4   239.3
  5929.8  236.89  6070.3  238.84  6591.9  237.51  6749.6  238.53  7139.4  239.96
#Mann= 7 ,-1 , 0
  2845.4     .05       0    4935    .035       0    5051     .05       0
  5391.1     .16       0  5483.7     .05       0  5558.4     .16       0
  6749.6     .05       0
Bank Sta=4935,5051
XS Rating Curve= 0 ,0
Exp/Cntr=0.3,0.1

Type RM Length L Ch R = 1 ,6273    ,1467,1467,1467
BEGIN DESCRIPTION:
UNT0464 IN WICK 1.0
END DESCRIPTION:
XS GIS Cut Line= 3
     3607417.587    10275386.889     3606810.476    10276178.556
      3606851.67    10278334.806
#Sta/Elev= 30
       0  253.16  109.15  251.52  178.61  248.76  367.15  232.95  565.61  232.56
  654.92   233.7  684.69  232.76  704.53  233.68   734.3  233.91  773.99  235.85
 1022.13  238.17 1201.33  238.35  1340.7  235.27 1470.11  235.25  1629.4  238.31
 1848.41  236.21 1908.14  237.97 1977.83  237.62 2097.29  235.73 2147.07  237.33
 2196.84  236.14 2256.57  237.85 2366.08  238.44  2495.5  237.85 2535.32  238.78
    2605  238.56 2704.55  237.05 2923.57  237.56 3082.85  240.84 3162.49  241.43
#Mann= 3 , 0 , 0
       0      .1       0  654.92     .05       0  704.53      .1       0
#XS Ineff= 2 , 0
                         5422.73           238.4
Permanent Ineff=
       F       F
Bank Sta=654.92,704.53
XS Rating Curve= 0 ,0
Exp/Cntr=0.3,0.1

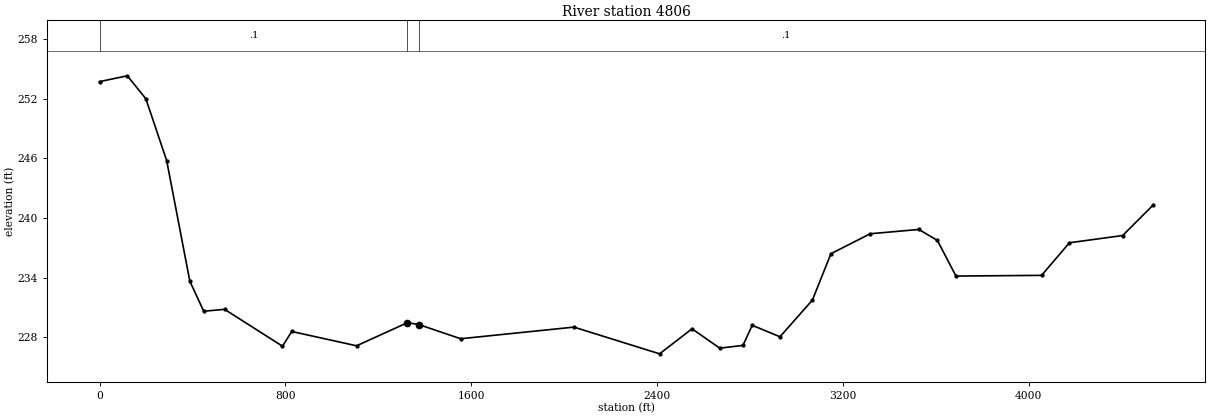
Type RM Length L Ch R = 1 ,4806    ,0,0,0
XS GIS Cut Line= 4
      3607351.67    10275300.083     3606188.476      10275310.5
      3605726.67    10275942.444     3606750.976    10278317.444
#Sta/Elev= 30
       0  253.73  119.66  254.32  199.43  252.01  289.18  245.78   388.9  233.64
  448.73  230.62  538.47  230.81  787.76   227.1  827.65  228.58 1106.86  227.14
 1325.94  229.47  1375.7  229.27 1554.85  227.85 2042.69  229.02 2411.54  226.33
  2551.1  228.85 2670.73   226.9 2770.41  227.18 2810.29   229.2 2929.91  228.05
 3069.48  231.74 3149.23  236.41 3318.69  238.42 3528.04  238.85 3607.79  237.74
 3687.54  234.16 4056.38  234.23 4176.01  237.51 4405.29  238.24 4534.88  241.27
#Mann= 3 , 0 , 0
       0      .1       0 1325.94     .05       0  1375.7      .1       0
Bank Sta=1325.94,1375.7
XS Rating Curve= 0 ,0
Exp/Cntr=0.3,0.1

Chan Stop Cuts=-1
Use User Specified Reach Order=0
Composite Channel Slope=5