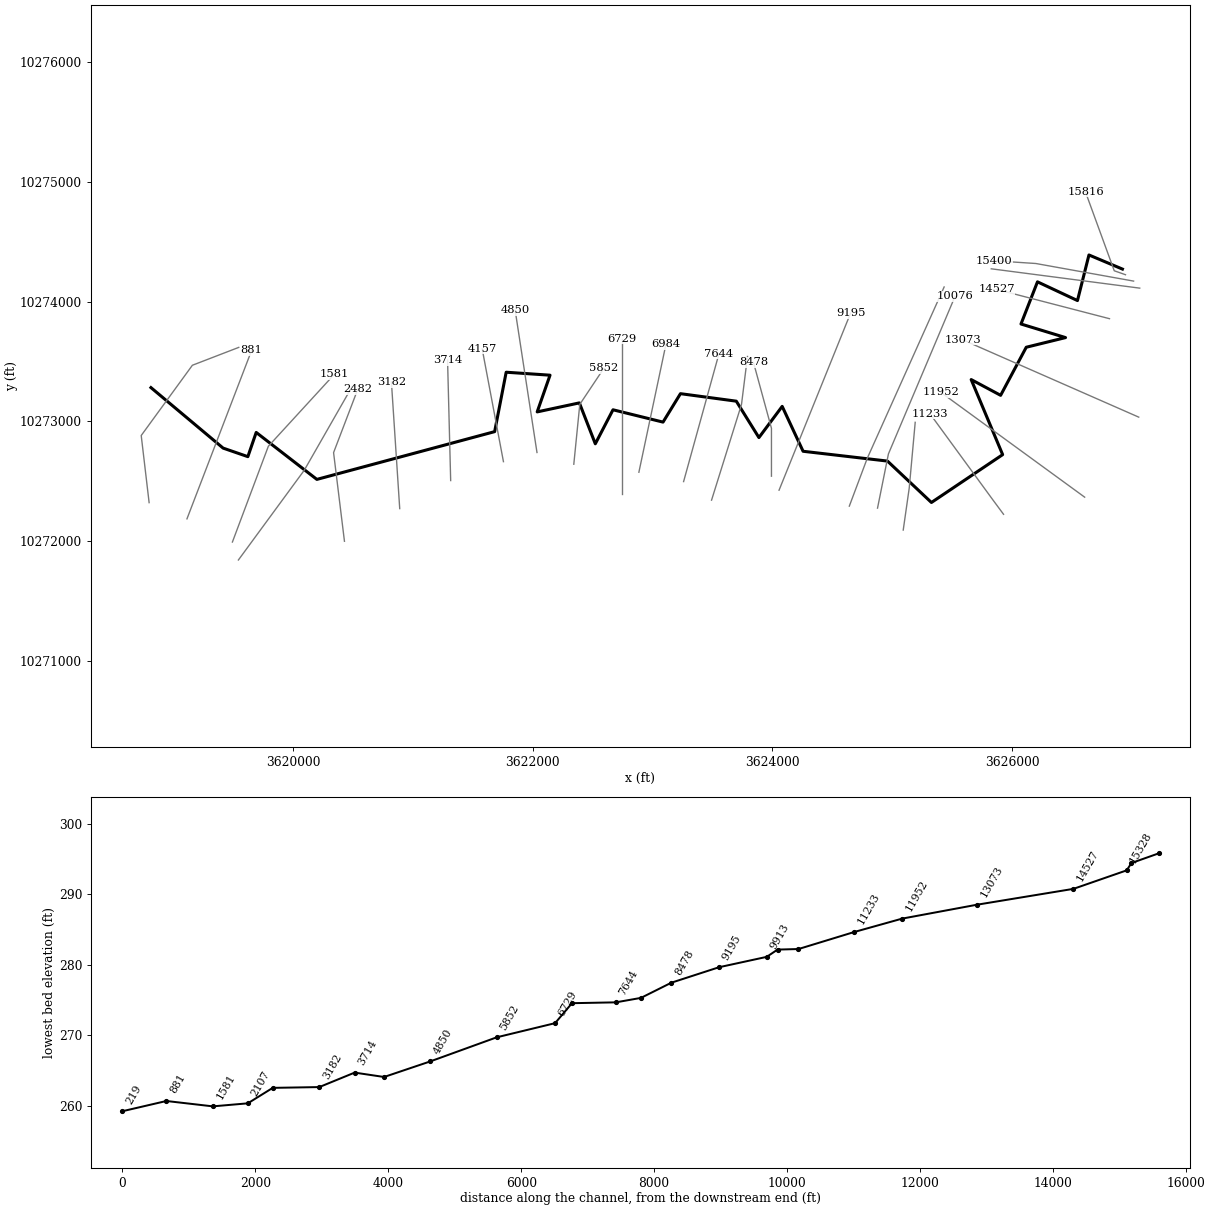
--- UNT0467 IN WICK.prj (project) ---

Proj Title=UNT0467 IN WICK Base Level Engineering
Current Plan=p01
Default Exp/Contr=0.3,0.1
English Units
Geom File=g01
Flow File=f01
Plan File=p01
Y Axis Title=Elevation
X Axis Title(PF)=Main Channel Distance
X Axis Title(XS)=Station
BEGIN DESCRIPTION:
UNT0467 IN WICK
END DESCRIPTION:
DSS Export Rating Curves= 0
DSS Export Rating Curve Sorted= 0
DSS Export Volume Flow Curves= 0
DXF OffsetX= 0
DXF OffsetY= 0
DXF ScaleX= 1
DXF ScaleY= 10

--- UNT0467 IN WICK.p01 (plan) ---

Plan Title=Multiple Run
Short Identifier=Multiple
Geom File=g01
Flow File=f01
Subcritical Flow
K Sum by GR= 0
Std Step Tol= 0.01
Critical Tol= 0.01
Num of Std Step Trials= 20
Max Error Tol= 0.3
Flow Tol Ratio= 0.001
Split Flow NTrial= 30
Split Flow Tol= 0.02
Split Flow Ratio= 0.02
Log Output Level= 0
Friction Slope Method= 1
Unsteady Friction Slope Method= 2
Unsteady Bridges Friction Slope Method= 1
Parabolic Critical Depth
Global Vel Dist=  1 , 1 , 1
Global Log Level= 0
CheckData=True
Encroach Param= -1, 0, 0, 0
BEGIN DESCRIPTION:
Multiple Run
END DESCRIPTION:

--- UNT0467 IN WICK.f01 (steady flow) ---

Flow Title=Multiple
Number of Profiles=7
Profile Names=10-year,25-year,50-year,1pct_min,100-year,1pct_plu,500-year
River Rch & RM= UNT0467 IN WICK,Reach-1,15816
     649     867    1042     917    1241    1678    1761
River Rch & RM= UNT0467 IN WICK,Reach-1,9913
     815    1100    1332    1180    1596    2158    2295
River Rch & RM= UNT0467 IN WICK,Reach-1,3714
     916    1244    1513    1345    1819    2460    2635
Boundary for River Rch & Prof#=UNT0467 IN WICK,Reach-1,1
Up Type=0
Dn Type=3
Dn Slope=0.005
Boundary for River Rch & Prof#=UNT0467 IN WICK,Reach-1,2
Up Type=0
Dn Type=3
Dn Slope=0.005
Boundary for River Rch & Prof#=UNT0467 IN WICK,Reach-1,3
Up Type=0
Dn Type=3
Dn Slope=0.005
Boundary for River Rch & Prof#=UNT0467 IN WICK,Reach-1,4
Up Type=0
Dn Type=3
Dn Slope=0.005
Boundary for River Rch & Prof#=UNT0467 IN WICK,Reach-1,5
Up Type=0
Dn Type=3
Dn Slope=0.005
Boundary for River Rch & Prof#=UNT0467 IN WICK,Reach-1,6
Up Type=0
Dn Type=3
Dn Slope=0.005
Boundary for River Rch & Prof#=UNT0467 IN WICK,Reach-1,7
Up Type=0
Dn Type=3
Dn Slope=0.005

--- UNT0467 IN WICK.g01 (geometry) ---

Geom Title=Existing Conditions
Program Version=4.10

River Reach=UNT0467 IN WICK ,Reach-1
Reach XY= 30
      3626922.11     10274271.64      3626642.59      10274389.5
      3626546.71     10274008.69      3626212.89      10274165.1
      3626075.25      10273812.9      3626447.19     10273699.38
      3626119.14     10273618.76      3625905.22     10273217.15
      3625659.38     10273348.75      3625922.11     10272721.64
      3625327.57     10272321.99      3624960.63     10272667.88
      3624256.21     10272749.78       3624081.7     10273124.92
       3623887.5     10272864.21      3623698.54     10273168.33
       3623232.5     10273230.99      3623086.96     10272993.46
      3622669.33     10273096.42      3622521.64     10272812.14
      3622388.66     10273153.98      3622036.38     10273078.69
      3622143.57     10273385.37      3621777.55     10273410.16
      3621681.31     10272913.82       3620197.2      10272514.9
      3619690.74     10272907.18      3619621.05      10272704.9
      3619414.46     10272776.28      3618812.11     10273281.64

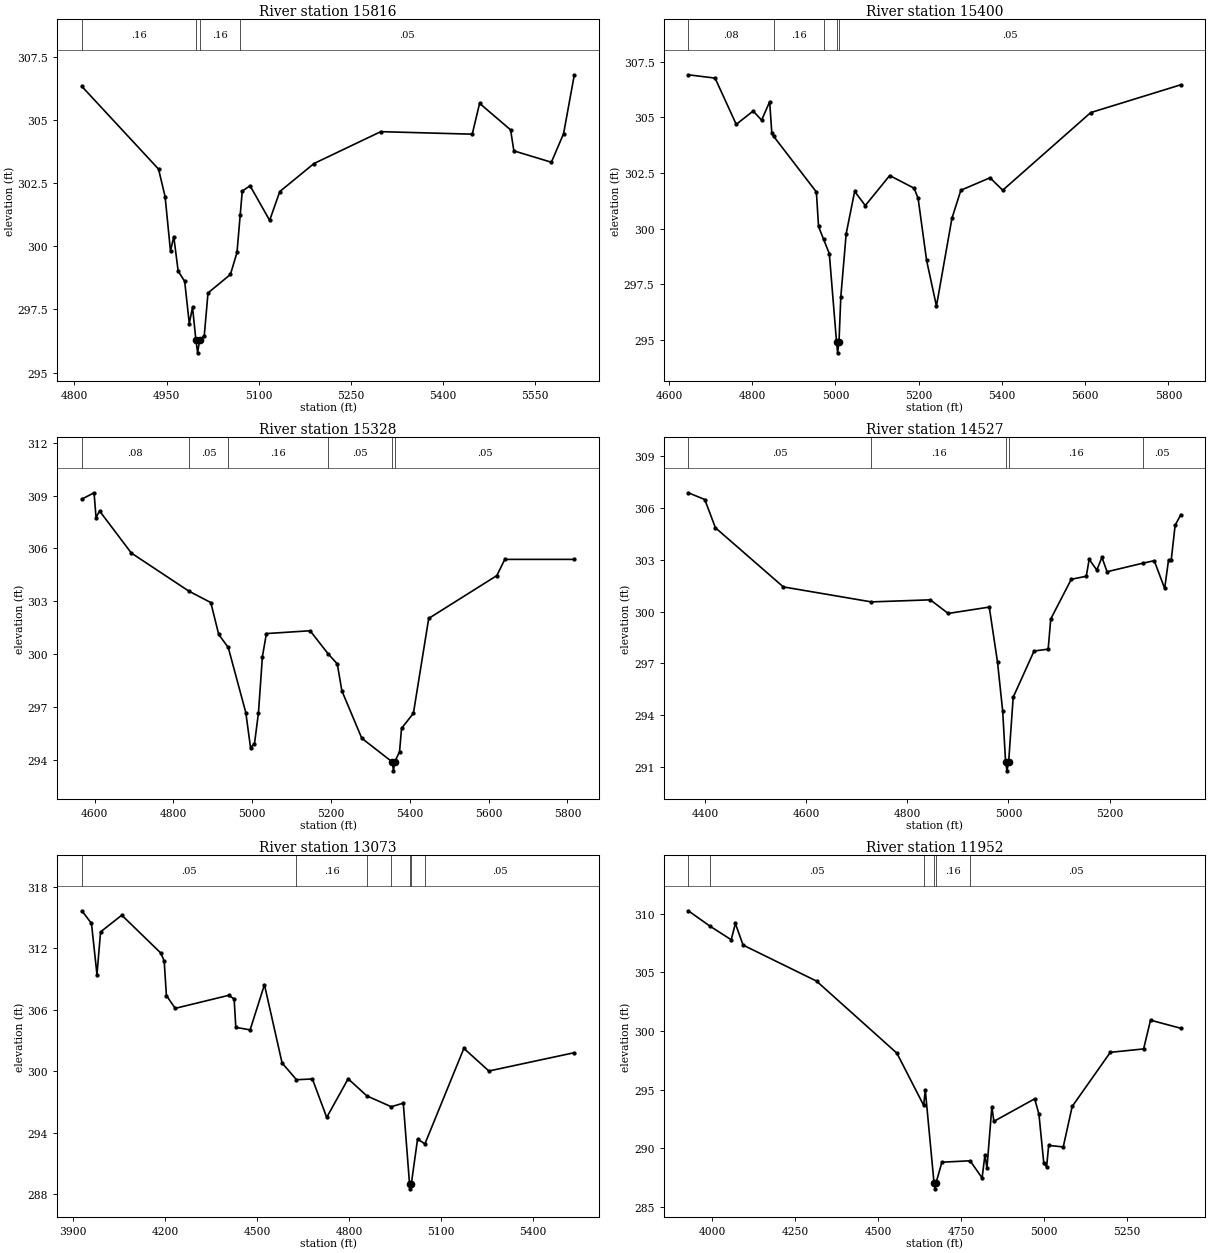
Type RM Length L Ch R = 1 ,15816   ,408,408,408
BEGIN DESCRIPTION:
UNT0467 IN WICK 25.0
END DESCRIPTION:
XS GIS Cut Line= 3
      3626947.48     10274224.64      3626853.74     10274257.62
      3626612.86     10274917.89
#Sta/Elev= 30
  4812.1  306.32    4937  303.05  4947.7  301.96  4956.5   299.8  4961.8  300.38
    4969  299.01  4979.6  298.61  4987.1  296.94  4992.4  297.58  4997.9  296.28
  5000.7  295.78  5003.9  296.28  5011.5  296.46  5017.6  298.15  5054.1  298.88
  5064.8  299.75    5070  301.22  5073.4  302.18  5086.1  302.39    5118  301.02
  5134.5  302.16  5190.3  303.27    5299  304.53    5448  304.43    5460  305.65
  5510.5   304.6  5515.8  303.77  5576.9  303.32  5596.8  304.45  5614.3  306.78
#Mann= 4 ,-1 , 0
  4812.1     .16       0  4997.9     .07       0  5003.9     .16       0
    5070     .05       0
Bank Sta=4997.9,5003.9
XS Rating Curve= 0 ,0
Exp/Cntr=0.3,0.1

Type RM Length L Ch R = 1 ,15400   ,72,72,72
BEGIN DESCRIPTION:
UNT0467 IN WICK 24.0
END DESCRIPTION:
XS GIS Cut Line= 3
      3627015.41      10274171.3       3626199.4     10274318.21
      3625846.21     10274341.59
#Sta/Elev= 30
  4646.6  306.92  4710.9  306.77  4761.7  304.69  4802.4  305.29  4822.7  304.88
    4842  305.71  4847.1  304.32  4851.3  304.16  4954.3  301.65  4959.4   300.1
  4971.7  299.52  4985.3  298.88  5002.6  294.92  5005.3  294.42  5008.6  294.92
    5013  296.95  5025.9  299.78  5046.2  301.68  5071.7  301.04  5130.4  302.39
  5189.1  301.82  5198.6  301.37    5219  298.58  5242.7  296.52  5279.9  300.47
  5301.4  301.73  5371.4  302.29  5401.9  301.73  5613.3  305.22  5829.7  306.47
#Mann= 5 ,-1 , 0
  4646.6     .08       0  4851.3     .16       0  4971.7     .05       0
  5002.6     .04       0  5008.6     .05       0
Bank Sta=5002.6,5008.6
XS Rating Curve= 0 ,0
Exp/Cntr=0.3,0.1

Type RM Length L Ch R = 1 ,15328   ,801,801,801
BEGIN DESCRIPTION:
UNT0467 IN WICK 23.0
END DESCRIPTION:
XS GIS Cut Line= 2
      3627066.62     10274112.48      3625827.09     10274273.93
#Sta/Elev= 30
  4567.6   308.8  4598.6  309.16  4603.6  307.75  4612.5  308.13  4693.2  305.74
  4839.1  303.58  4894.9  302.93    4915  301.12  4939.2  300.38  4983.8  296.68
  4995.7   294.7  5005.8  294.92  5015.9  296.68  5025.9  299.86    5036  301.17
    5147  301.33  5192.7  300.02  5215.9  299.45  5227.6  297.92  5278.1  295.23
  5355.7  293.88  5358.5  293.38  5361.7  293.88    5374  294.47    5379  295.79
  5409.2  296.65    5448  302.03  5620.9  304.46  5641.1  305.38  5817.6  305.38
#Mann= 6 ,-1 , 0
  4567.6     .08       0  4839.1     .05       0  4939.2     .16       0
  5192.7     .05       0  5355.7     .07       0  5361.7     .05       0
Bank Sta=5355.7,5361.7
XS Rating Curve= 0 ,0
Exp/Cntr=0.3,0.1

Type RM Length L Ch R = 1 ,14527   ,1454,1454,1454
BEGIN DESCRIPTION:
Mapping XS 4a4a75db
END DESCRIPTION:
XS GIS Cut Line= 2
      3626813.99     10273857.28      3625871.25     10274102.07
#Sta/Elev= 30
  4366.8  306.89  4399.3   306.5  4420.4  304.86  4554.7  301.43  4728.8  300.56
  4845.4  300.68  4880.8  299.89    4962  300.26  4978.3  297.07  4988.6  294.21
  4994.3  291.26  4997.1  290.76  5000.3  291.26  5009.3  295.03  5050.6  297.71
  5078.5  297.82  5083.6  299.57  5124.2  301.87  5153.9  302.05  5159.6  303.03
  5174.6  302.41  5184.9  303.14    5195  302.31  5266.3  302.81  5288.3  302.95
  5308.9  301.34  5316.6     303  5321.8  302.97  5329.6     305  5340.8  305.62
#Mann= 5 ,-1 , 0
  4366.8     .05       0  4728.8     .16       0  4994.3     .07       0
  5000.3     .16       0  5266.3     .05       0
Bank Sta=4994.3,5000.3
XS Rating Curve= 0 ,0
Exp/Cntr=0.3,0.1

Type RM Length L Ch R = 1 ,13073   ,1121,1121,1121
BEGIN DESCRIPTION:
UNT0467 IN WICK 22.0
END DESCRIPTION:
XS GIS Cut Line= 2
      3627058.08     10273034.95      3625586.91     10273681.57
#Sta/Elev= 30
  3928.2  315.67  3959.6  314.44  3977.5  309.44  3989.3  313.61  4058.5  315.24
  4186.2  311.53  4196.9  310.75  4204.1  307.39  4232.9  306.14  4407.2  307.41
  4425.1  307.06  4430.6  304.28  4477.3  304.04    4524  308.45  4581.6   300.8
  4628.6  299.17  4680.5  299.24  4727.2  295.49  4797.2  299.26  4858.1  297.59
  4937.8  296.53  4977.1  296.88  4997.4  289.01  5000.1  288.51  5003.4  289.01
  5023.7  293.38  5047.6   292.9  5174.8  302.23  5256.4  300.02  5535.2  301.81
#Mann= 7 ,-1 , 0
  3928.2     .05       0  4628.6     .16       0  4858.1     .05       0
  4937.8     .16       0  4997.4     .07       0  5003.4     .16       0
  5047.6     .05       0
Bank Sta=4997.4,5003.4
XS Rating Curve= 0 ,0
Exp/Cntr=0.3,0.1

Type RM Length L Ch R = 1 ,11952   ,719,719,719
BEGIN DESCRIPTION:
UNT0467 IN WICK 21.0
END DESCRIPTION:
XS GIS Cut Line= 2
      3626606.76     10272366.51      3625405.78     10273242.31
#Sta/Elev= 30
  3927.1  310.24  3991.9  308.94  4056.6  307.77  4069.1  309.16  4092.3  307.32
    4314  304.25  4556.6  298.11  4637.5  293.66  4642.3  294.97  4668.7  287.05
  4671.4  286.55  4674.7  287.05  4692.5  288.82  4777.6  288.94  4813.8  287.48
  4822.3  289.43  4828.5  288.32  4843.2  293.52  4849.4   292.3  4972.5  294.22
  4985.3  292.91    5000  288.74  5008.5  288.42  5014.7  290.25  5058.7  290.12
  5085.7  293.57  5200.8  298.18  5301.3  298.47  5322.1  300.92  5413.5  300.23
#Mann= 6 ,-1 , 0
  3927.1     .16       0  3991.9     .05       0  4637.5     .16       0
  4668.7     .03       0  4674.7     .16       0  4777.6     .05       0
Bank Sta=4668.7,4674.7
XS Rating Curve= 0 ,0
Exp/Cntr=0.3,0.1

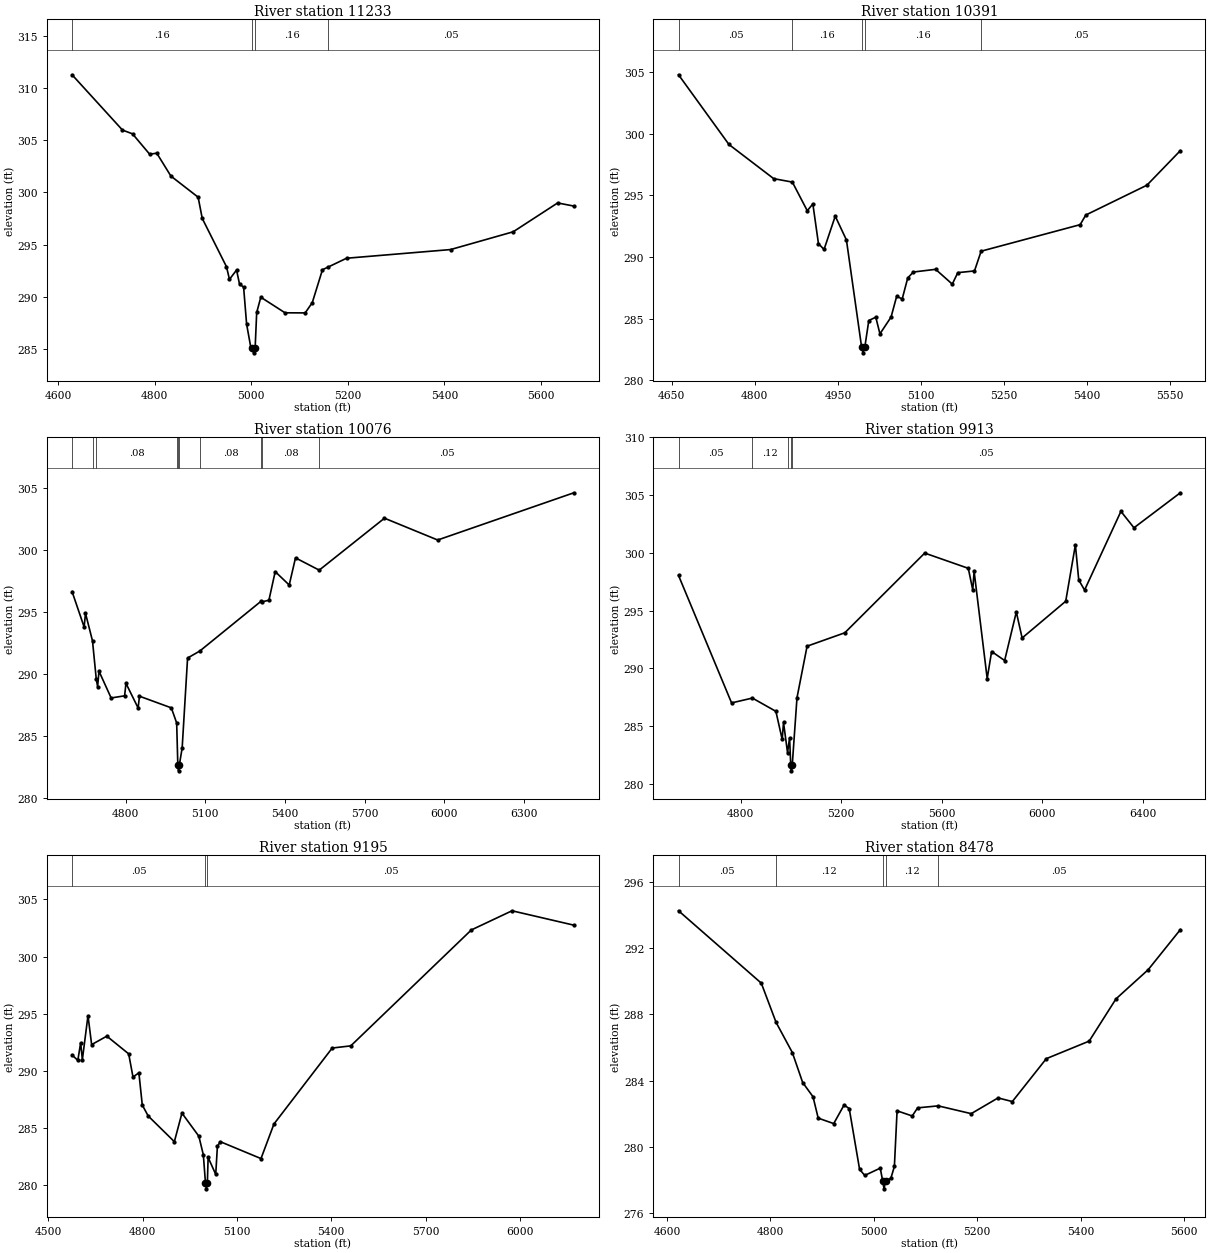
Type RM Length L Ch R = 1 ,11233   ,842,842,842
BEGIN DESCRIPTION:
UNT0467 IN WICK 20.0
END DESCRIPTION:
XS GIS Cut Line= 3
      3625929.64     10272223.32      3625842.11     10272341.64
      3625316.09     10273062.18
#Sta/Elev= 30
    4629  311.26  4733.4  305.97  4754.2  305.61  4789.7  303.66  4804.4  303.76
  4833.7  301.57  4890.1  299.55  4898.6  297.52  4948.8   292.9    4955  291.69
  4969.7  292.58  4975.8  291.24  4984.3  290.94  4990.5  287.41    4999  285.23
  5002.2  285.16  5004.9  284.66  5008.2  285.16  5011.4  288.52  5019.9  289.98
  5070.1  288.49  5111.8  288.48  5126.5  289.46  5147.6  292.61    5160  292.88
  5197.5  293.71    5413  294.54  5542.7  296.24  5634.7     299  5668.3   298.7
#Mann= 4 ,-1 , 0
    4629     .16       0  5002.2     .07       0  5008.2     .16       0
    5160     .05       0
Bank Sta=5002.2,5008.2
XS Rating Curve= 0 ,0
Exp/Cntr=0.3,0.1

Type RM Length L Ch R = 1 ,10391   ,315,315,315
BEGIN DESCRIPTION:
UNT0467 IN WICK 19.0
END DESCRIPTION:
XS GIS Cut Line= 3
       3625092.1      10272091.6      3625142.11     10272441.64
      3625192.11     10272991.68
#Sta/Elev= 30
  4662.2  304.78  4753.2  299.13    4834  296.36  4867.7  296.08  4894.6  293.76
  4904.7  294.31  4914.8  291.09  4924.9  290.62  4945.1  293.32  4965.3  291.39
  4992.6  282.74  4995.3  282.24  4998.6  282.74  5005.7  284.86  5018.3  285.13
  5025.8  283.78  5045.9  285.14    5056  286.82    5066  286.61    5076  288.31
  5086.1  288.79  5126.3  289.01  5156.4  287.81  5166.4  288.74  5196.5  288.88
  5208.5  290.48  5387.3  292.63  5397.4  293.41  5507.8  295.83  5568.1  298.63
#Mann= 5 ,-1 , 0
  4662.2     .05       0  4867.7     .16       0  4992.6     .07       0
  4998.6     .16       0  5208.5     .05       0
Bank Sta=4992.6,4998.6
XS Rating Curve= 0 ,0
Exp/Cntr=0.3,0.1

Type RM Length L Ch R = 1 ,10076   ,163,163,163
BEGIN DESCRIPTION:
Mapping XS 8b90f1c8
END DESCRIPTION:
XS GIS Cut Line= 3
      3624877.56     10272274.93      3624968.71     10272728.08
      3625524.84     10274044.18
#Sta/Elev= 30
  4597.9  296.62  4643.4  293.76  4648.5  294.87  4674.9  292.64  4689.1  289.56
  4694.2  288.95  4699.3   290.2  4745.1  288.04  4795.9  288.21    4801  289.22
  4846.8  287.23  4851.9  288.18    4972  287.24  4992.1  286.02  4996.4  282.66
  4999.1  282.16  5002.4  282.66  5012.8  284.01  5033.2  291.26    5079  291.82
  5311.2  295.86  5312.4  295.79  5339.7  295.92  5363.4  298.23  5416.2  297.15
  5439.9  299.34  5529.3  298.35  5775.2  302.54  5975.7  300.78  6488.9  304.59
#Mann= 10 ,-1 , 0
  4597.9     .08       0  4674.9     .05       0  4689.1     .08       0
  4992.1     .16       0  4996.4     .07       0  5002.4     .16       0
    5079     .08       0  5311.2     .05       0  5312.4     .08       0
  5529.3     .05       0
Bank Sta=4996.4,5002.4
XS Rating Curve= 0 ,0
Exp/Cntr=0.3,0.1

Type RM Length L Ch R = 1 ,9913    ,718,718,718
BEGIN DESCRIPTION:
UNT0467 IN WICK 18.0
END DESCRIPTION:
XS GIS Cut Line= 3
      3624642.11     10272291.66      3624792.11     10272691.64
      3625433.69     10274122.28
#Sta/Elev= 30
  4553.4  298.04  4764.3  287.01    4847  287.43  4940.5  286.28  4965.5  283.85
  4970.8  285.32  4986.8   282.7  4994.9  283.99  4999.5  281.63  5002.3  281.13
  5005.5  281.63  5024.4  287.46  5064.5  291.92  5214.5  293.08  5532.2  299.98
  5705.5  298.66  5723.2  296.79  5728.6   298.4  5780.6  289.12  5798.2  291.46
    5850  290.68  5896.4  294.88  5919.5  292.63  6092.8  295.81  6131.3  300.69
  6144.6  297.65  6167.8  296.78  6312.3  303.59  6364.2  302.17  6548.5   305.2
#Mann= 5 ,-1 , 0
  4553.4     .05       0    4847     .12       0  4986.8     .05       0
  4999.5     .03       0  5005.5     .05       0
Bank Sta=4999.5,5005.5
XS Rating Curve= 0 ,0
Exp/Cntr=0.3,0.1

Type RM Length L Ch R = 1 ,9195    ,717,717,717
BEGIN DESCRIPTION:
Mapping XS 2a92380d
END DESCRIPTION:
XS GIS Cut Line= 2
      3624055.53     10272424.72      3624652.76      10273903.9
#Sta/Elev= 30
  4575.9  291.38  4594.2  290.91  4603.2  292.45  4608.6  290.97  4626.5  294.83
  4638.1  292.29  4686.4  293.03  4755.9  291.48  4769.6  289.45  4788.3  289.82
  4799.1     287  4817.9  286.04  4901.1  283.79  4925.2  286.29  4978.9  284.27
  4993.2  282.64    5000  280.16  5002.8  279.66    5006  280.16  5008.4  282.41
  5032.6  280.93  5037.9  283.38  5047.1  283.79  5176.5  282.31  5217.7  285.34
  5402.9  291.99  5461.9  292.18  5845.1  302.33  5974.5  304.01  6171.1  302.75
#Mann= 3 ,-1 , 0
  4575.9     .05       0    5000     .03       0    5006     .05       0
Bank Sta=5000,5006
XS Rating Curve= 0 ,0
Exp/Cntr=0.3,0.1

Type RM Length L Ch R = 1 ,8478    ,457,457,457
BEGIN DESCRIPTION:
UNT0467 IN WICK 16.0
END DESCRIPTION:
XS GIS Cut Line= 3
      3623992.11     10272541.64      3623992.11     10272941.64
       3623842.1     10273491.65
#Sta/Elev= 30
  4622.4  294.26  4782.4  289.89    4811  287.52  4842.4   285.7  4862.4  283.89
  4882.4  283.03  4892.4  281.74  4922.4  281.41  4942.4  282.53  4952.4  282.32
  4972.4  278.65  4982.4  278.28  5012.4  278.72  5016.9  277.97  5019.7  277.47
  5022.9  277.97  5032.8   278.1  5039.7  278.82  5044.9  282.18  5074.2  281.87
  5084.6  282.36  5124.4  282.48  5188.2  282.01  5240.1  282.96  5267.7  282.74
  5333.4  285.33  5416.3  286.39  5468.1  288.94  5530.3   290.7  5592.5  293.12
#Mann= 5 ,-1 , 0
  4622.4     .05       0    4811     .12       0  5016.9     .07       0
  5022.9     .12       0  5124.4     .05       0
Bank Sta=5016.9,5022.9
XS Rating Curve= 0 ,0
Exp/Cntr=0.3,0.1

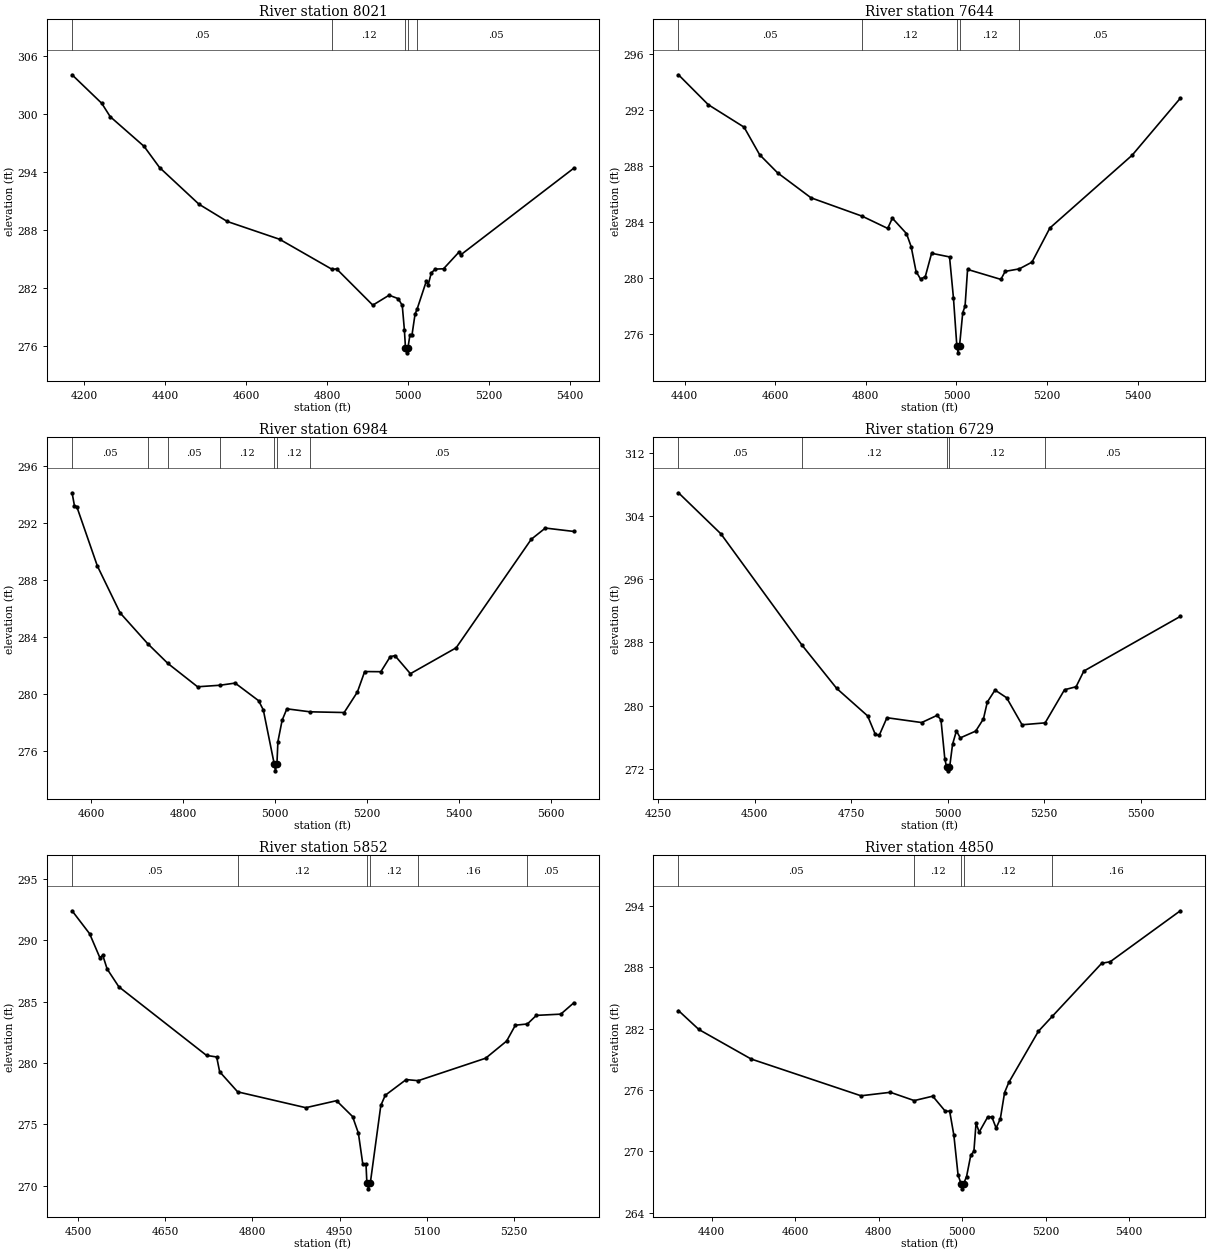
Type RM Length L Ch R = 1 ,8021    ,377,377,377
BEGIN DESCRIPTION:
UNT0467 IN WICK 15.0
END DESCRIPTION:
XS GIS Cut Line= 3
       3623492.1     10272341.61      3623742.11     10273141.64
      3623792.11     10273541.65
#Sta/Elev= 30
  4169.4  304.07  4242.8  301.12  4263.7  299.74  4347.5  296.67  4385.8  294.48
  4483.2  290.69  4553.4   288.9  4682.8  287.06  4812.6  283.95  4823.7     284
  4913.3  280.25  4953.6  281.28  4976.2  280.92  4986.1  280.22  4991.3  277.73
  4994.1  275.82  4996.9  275.32  5000.1  275.82    5005  277.14  5010.1  277.14
  5017.7  279.31  5023.2  279.89  5045.4   282.7  5050.4  282.38    5058   283.6
  5068.1  283.98  5088.2  284.01    5126  285.72    5131  285.46  5410.7  294.42
#Mann= 5 ,-1 , 0
  4169.4     .05       0  4812.6     .12       0  4994.1     .07       0
  5000.1     .12       0  5023.2     .05       0
Bank Sta=4994.1,5000.1
XS Rating Curve= 0 ,0
Exp/Cntr=0.3,0.1

Type RM Length L Ch R = 1 ,7644    ,660,660,660
BEGIN DESCRIPTION:
UNT0467 IN WICK 14.0
END DESCRIPTION:
XS GIS Cut Line= 2
      3623258.66     10272496.57      3623553.79     10273564.23
#Sta/Elev= 30
  4386.5  294.49  4452.3  292.36  4531.3  290.76  4565.6   288.8  4605.2  287.51
    4679  285.73    4792  284.42  4848.3  283.55  4858.6  284.28  4889.8  283.18
  4900.1  282.25  4910.9  280.48  4920.9  279.94  4931.3  280.12  4945.2  281.78
  4984.8  281.52  4993.5  278.58  5000.9  275.19  5003.6  274.69  5006.9  275.19
  5013.9  277.54  5019.1  278.03  5024.6  280.63  5098.1  279.92  5107.6  280.49
  5138.9  280.67  5166.8  281.15  5206.3  283.58  5387.8  288.76  5494.2  292.82
#Mann= 5 ,-1 , 0
  4386.5     .05       0    4792     .12       0  5000.9     .07       0
  5006.9     .12       0  5138.9     .05       0
Bank Sta=5000.9,5006.9
XS Rating Curve= 0 ,0
Exp/Cntr=0.3,0.1

Type RM Length L Ch R = 1 ,6984    ,255,255,255
BEGIN DESCRIPTION:
UNT0467 IN WICK 13.0
END DESCRIPTION:
XS GIS Cut Line= 2
       3622885.4     10272574.69      3623111.09     10273642.39
#Sta/Elev= 30
  4558.3  294.12  4563.4  293.22  4568.5  293.15  4613.2  288.98  4662.9  285.67
  4722.8  283.51  4766.7  282.12  4831.2  280.48  4880.6  280.59  4912.9  280.74
    4964   279.5  4974.2  278.85  4997.8  275.07  5000.5  274.57  5003.8  275.07
  5005.9  276.62  5015.1  278.13  5025.4  278.93  5075.7  278.72    5150  278.67
  5178.7  280.11  5194.6  281.55  5229.8  281.54  5250.2   282.6  5260.4  282.67
    5294   281.4  5393.5  283.22  5556.8  290.85  5587.5  291.64  5649.6   291.4
#Mann= 7 ,-1 , 0
  4558.3     .05       0  4722.8     .12       0  4766.7     .05       0
  4880.6     .12       0  4997.8     .07       0  5003.8     .12       0
  5075.7     .05       0
Bank Sta=4997.8,5003.8
XS Rating Curve= 0 ,0
Exp/Cntr=0.3,0.1

Type RM Length L Ch R = 1 ,6729    ,877,877,877
BEGIN DESCRIPTION:
UNT0467 IN WICK 12.0
END DESCRIPTION:
XS GIS Cut Line= 3
      3622742.11     10272391.66      3622742.11     10273091.64
      3622742.11     10273691.66
#Sta/Elev= 30
  4302.5  306.92  4412.5  301.72  4621.9  287.68  4712.5  282.16  4792.5  278.69
  4812.5  276.34  4822.5  276.23  4842.5  278.46  4932.5  277.85  4972.5  278.76
  4982.5  278.19  4992.5  273.23    4997  272.24  4999.7  271.74    5003  272.24
    5005  272.24  5012.5   275.1  5022.5  276.79  5032.5  275.91  5072.5  276.77
  5092.5  278.31  5102.5  280.44  5122.5  281.96  5152.5  280.99  5192.5  277.57
  5252.3  277.81  5302.5     282  5332.5  282.38  5352.5  284.36  5602.5  291.28
#Mann= 5 ,-1 , 0
  4302.5     .05       0  4621.9     .12       0    4997     .07       0
    5003     .12       0  5252.3     .05       0
Bank Sta=4997,5003
XS Rating Curve= 0 ,0
Exp/Cntr=0.3,0.1

Type RM Length L Ch R = 1 ,5852    ,1002,1002,1002
BEGIN DESCRIPTION:
UNT0467 IN WICK 10.0
END DESCRIPTION:
XS GIS Cut Line= 3
      3622342.11     10272641.64      3622392.11     10273141.64
      3622592.13     10273441.68
#Sta/Elev= 30
  4489.9  292.39  4520.1  290.52  4537.6  288.58  4542.7  288.76  4550.2  287.65
  4570.3   286.2  4721.1  280.61  4738.6  280.48  4743.7  279.28  4774.7  277.64
  4891.9  276.35  4944.7  276.92  4972.3  275.63  4982.3  274.28  4989.9  271.76
  4995.4  271.76  4996.9  270.24  4999.7  269.74  5002.9  270.24  5020.9  276.53
  5028.5  277.36  5064.5  278.64  5085.2  278.55  5201.2  280.38  5237.3  281.78
  5252.3  283.07    5273  283.17  5288.4  283.87  5330.4  283.97    5353   284.9
#Mann= 6 ,-1 , 0
  4489.9     .05       0  4774.7     .12       0  4996.9     .07       0
  5002.9     .12       0  5085.2     .16       0    5273     .05       0
Bank Sta=4996.9,5002.9
XS Rating Curve= 0 ,0
Exp/Cntr=0.3,0.1

Type RM Length L Ch R = 1 ,4850    ,693,693,693
BEGIN DESCRIPTION:
UNT0467 IN WICK 9.0
END DESCRIPTION:
XS GIS Cut Line= 2
       3622034.7     10272739.63      3621852.58     10273927.75
#Sta/Elev= 30
  4320.7  283.77  4369.5  281.92  4494.7  279.03  4757.8  275.43  4828.2  275.77
  4885.4  274.96  4929.7  275.39  4959.9  273.91  4970.2  273.93  4980.3  271.57
  4990.4  267.66  4997.6  266.82  5000.3  266.32  5003.6  266.82  5010.7  267.52
  5020.8  269.61  5028.3     270  5033.4  272.74    5041  271.88  5061.3  273.35
  5071.4  273.35  5081.5  272.27  5091.6  273.18  5101.8  275.75  5111.8  276.73
  5182.7  281.74  5216.1  283.21  5334.4   288.4  5354.7  288.55  5522.7  293.54
#Mann= 5 ,-1 , 0
  4320.7     .05       0  4885.4     .12       0  4997.6     .07       0
  5003.6     .12       0  5216.1     .16       0
Bank Sta=4997.6,5003.6
XS Rating Curve= 0 ,0
Exp/Cntr=0.3,0.1

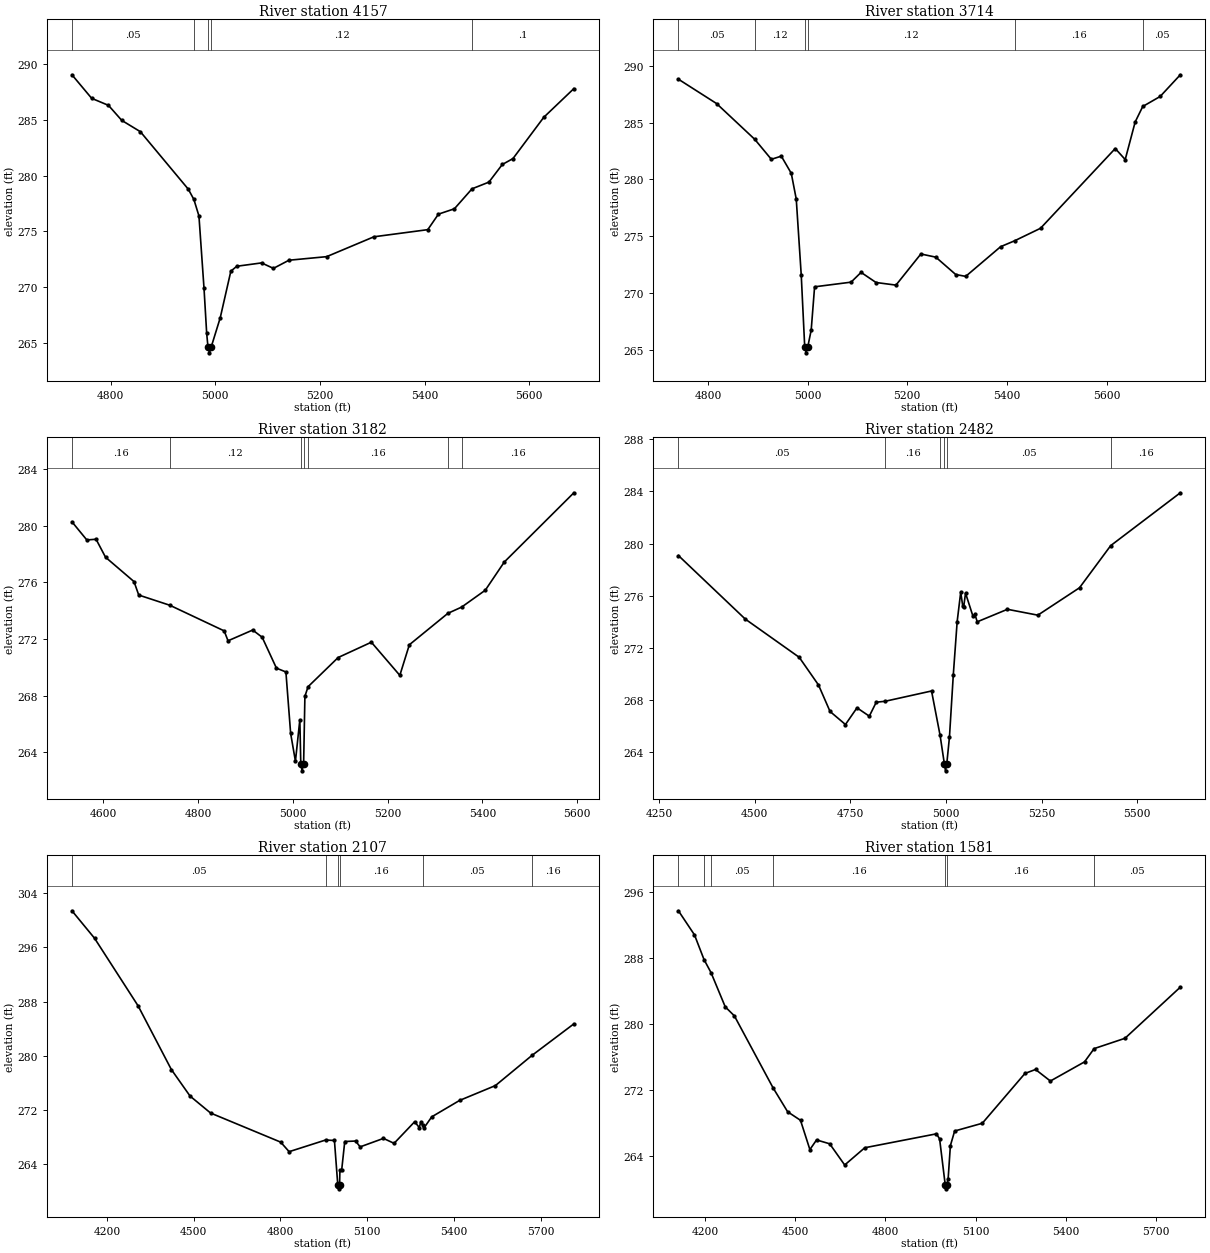
Type RM Length L Ch R = 1 ,4157    ,443,443,443
BEGIN DESCRIPTION:
Mapping XS 2445e682
END DESCRIPTION:
XS GIS Cut Line= 2
      3621754.76     10272663.08        3621577.     10273606.07
#Sta/Elev= 30
  4725.8  289.04  4763.5  286.93  4795.6   286.3  4821.1  284.95  4856.6  283.94
  4948.2  278.79  4958.9  277.87  4968.6  276.39  4978.3   269.9  4983.4  265.86
  4985.9  264.62  4988.7  264.12  4991.9  264.62  5009.3  267.26  5029.6  271.44
    5041  271.88  5088.3  272.18    5111  271.69  5140.7  272.42  5212.8  272.74
  5303.1  274.52  5406.1  275.16  5426.5  276.55    5457  277.03  5490.7  278.82
    5523  279.42  5548.6     281    5569  281.53  5627.9  285.23  5685.4   287.8
#Mann= 5 ,-1 , 0
  4725.8     .05       0  4958.9     .12       0  4985.9     .07       0
  4991.9     .12       0  5490.7      .1       0
Bank Sta=4985.9,4991.9
XS Rating Curve= 0 ,0
Exp/Cntr=0.3,0.1

Type RM Length L Ch R = 1 ,3714    ,532,532,532
BEGIN DESCRIPTION:
UNT0467 IN WICK 8.0
END DESCRIPTION:
XS GIS Cut Line= 2
      3621314.22     10272505.21      3621288.17     10273512.18
#Sta/Elev= 30
  4740.7  288.82  4817.2  286.68  4893.9  283.53  4927.2  281.77  4947.2  282.05
  4967.2  280.54  4977.2  278.27  4987.2  271.59  4994.2  265.24    4997  264.74
  5000.2  265.24  5007.2  266.75    5014  270.55  5087.2  270.96  5107.3  271.82
  5137.3  270.93  5177.3   270.7  5227.3  273.44  5257.3  273.16  5297.3  271.63
  5317.3  271.47  5387.3  274.08  5415.4   274.6  5467.4   275.7  5617.4  282.72
  5637.4  281.75  5657.4  285.06  5672.6  286.42  5707.5   287.3    5748  289.21
#Mann= 6 ,-1 , 0
  4740.7     .05       0  4893.9     .12       0  4994.2     .07       0
  5000.2     .12       0  5415.4     .16       0  5672.6     .05       0
Bank Sta=4994.2,5000.2
XS Rating Curve= 0 ,0
Exp/Cntr=0.3,0.1

Type RM Length L Ch R = 1 ,3182    ,700,700,700
BEGIN DESCRIPTION:
UNT0467 IN WICK 6.0
END DESCRIPTION:
XS GIS Cut Line= 2
      3620888.87      10272270.9      3620819.53     10273328.22
#Sta/Elev= 30
  4533.6  280.27    4565  278.99  4584.5  279.04  4604.5  277.77  4664.6  276.05
  4674.6   275.1  4740.2  274.38    4855  272.57  4863.1  271.87  4915.2  272.63
  4935.2  272.12  4965.3  269.94  4985.3  269.67  4995.3  265.33  5005.4  263.37
  5014.7  266.29  5016.7  263.19  5019.4  262.69  5022.7  263.19  5025.4  267.95
  5032.1  268.63  5095.6  270.69  5165.7  271.77  5225.8  269.43  5245.9  271.59
  5327.3  273.81  5356.3  274.25  5406.2  275.44  5446.3  277.43  5593.2  282.32
#Mann= 7 ,-1 , 0
  4533.6     .16       0  4740.2     .12       0  5016.7     .07       0
  5022.7     .12       0  5032.1     .16       0  5327.3     .12       0
  5356.3     .16       0
Bank Sta=5016.7,5022.7
XS Rating Curve= 0 ,0
Exp/Cntr=0.3,0.1

Type RM Length L Ch R = 1 ,2482    ,375,375,375
BEGIN DESCRIPTION:
UNT0467 IN WICK 5.0
END DESCRIPTION:
XS GIS Cut Line= 3
      3620427.52     10271998.01       3620336.7     10272738.52
      3620538.75     10273268.02
#Sta/Elev= 30
  4300.1  279.08    4475  274.21  4616.1  271.28  4666.5  269.16  4696.7  267.13
    4737  266.13  4767.2  267.41  4799.4  266.77  4817.6  267.84  4840.6  267.91
  4962.2   268.7  4984.6  265.29  4995.9  263.08  4998.7  262.58  5001.9  263.08
    5009  265.15  5019.1  269.94  5029.2  274.02  5038.5  276.27  5043.6  275.25
  5046.2  275.14  5051.1   276.2  5070.4  274.44  5075.8  274.57  5081.6     274
  5160.7  274.96  5240.2  274.51  5349.2  276.61  5430.8  279.84  5612.9  283.89
#Mann= 6 ,-1 , 0
  4300.1     .05       0  4840.6     .16       0  4984.6     .05       0
  4995.9     .03       0  5001.9     .05       0  5430.8     .16       0
Bank Sta=4995.9,5001.9
XS Rating Curve= 0 ,0
Exp/Cntr=0.3,0.1

Type RM Length L Ch R = 1 ,2107    ,526,526,526
BEGIN DESCRIPTION:
UNT0467 IN WICK 4.0
END DESCRIPTION:
XS GIS Cut Line= 3
      3619542.13     10271841.67      3620092.11     10272591.64
      3620492.08     10273291.61
#Sta/Elev= 30
  4078.9   301.4  4157.2  297.34  4307.7  287.38  4422.7  277.99  4487.5  274.07
  4558.5  271.57  4800.9  267.28  4830.2  265.87  4956.3  267.59  4986.9  267.52
  4998.6  260.89  5001.3  260.39  5004.6  260.89  5005.8   263.1  5011.8   263.1
  5022.6  267.37    5060  267.44  5075.9  266.58  5156.5  267.83  5193.2   267.1
  5264.5  270.29  5280.3  269.43  5286.1  270.29  5291.9  269.74  5296.1  269.34
  5323.5  271.01  5419.9  273.43  5543.8  275.62    5670  280.06  5815.1  284.72
#Mann= 6 ,-1 , 0
  4078.9     .05       0  4956.3     .16       0  4998.6     .07       0
  5004.6     .16       0  5291.9     .05       0    5670     .16       0
Bank Sta=4998.6,5004.6
XS Rating Curve= 0 ,0
Exp/Cntr=0.3,0.1

Type RM Length L Ch R = 1 ,1581    ,699,699,699
BEGIN DESCRIPTION:
UNT0467 IN WICK 3.0
END DESCRIPTION:
XS GIS Cut Line= 3
      3619492.12     10271991.67      3619792.11     10272791.64
       3620342.1     10273391.63
#Sta/Elev= 30
  4111.7  293.67  4165.1  290.75    4197  287.74    4220  286.18  4267.4  282.02
  4297.7  280.93  4425.9  272.23  4474.8   269.3  4517.5  268.27  4548.7  264.72
  4570.9  265.89  4614.5  265.42  4664.4  262.85  4731.1  264.94  4969.5  266.63
  4979.9  266.01  4998.5  260.46  5001.3  259.96  5004.5  260.46  5008.3  261.21
  5015.7   265.2  5029.9  266.97  5121.8  267.91  5263.6  273.95  5298.7  274.43
  5348.1  273.03  5461.5  275.35  5493.5  276.96    5596  278.21    5780  284.41
#Mann= 7 ,-1 , 0
  4111.7     .05       0    4197     .16       0    4220     .05       0
  4425.9     .16       0  4998.5     .07       0  5004.5     .16       0
  5493.5     .05       0
Bank Sta=4998.5,5004.5
XS Rating Curve= 0 ,0
Exp/Cntr=0.3,0.1

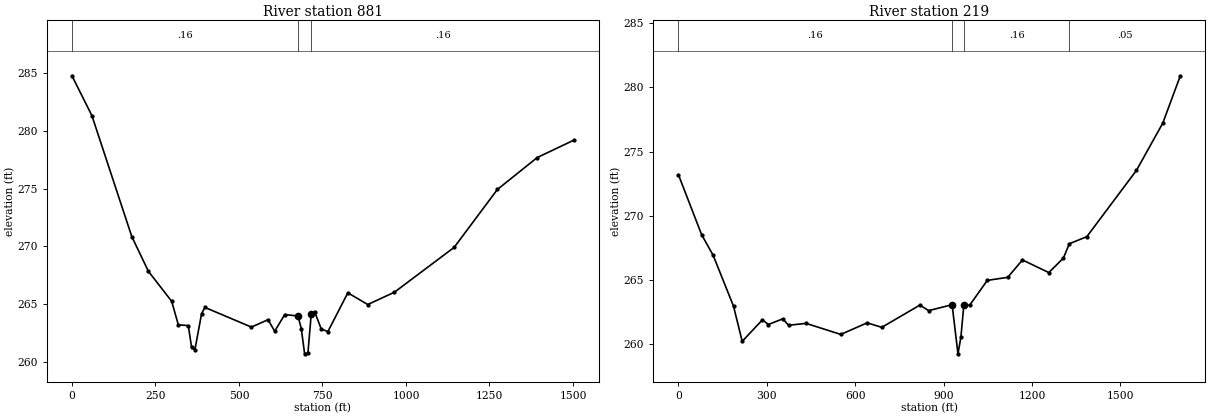
Type RM Length L Ch R = 1 ,881     ,662,662,662
XS GIS Cut Line= 2
     3619112.817    10272185.297     3619652.747    10273593.283
#Sta/Elev= 30
       0  284.74   59.71   281.3  179.13  270.85  228.88  267.85  298.54  265.26
  318.45  263.23   348.3  263.16  358.25  261.27   368.2  261.08  388.11  264.19
  398.06  264.73  537.38  263.03  587.13  263.67  607.04  262.67  636.89  264.11
   676.7  263.99  686.65   262.9   696.6  260.72  706.55   260.8   716.5   264.2
  726.46  264.37  746.36  262.87  766.26  262.64  825.97  265.99  885.68  264.98
  965.29  266.04 1144.42  269.92 1273.78  274.92  1393.2  277.68 1502.67  279.18
#Mann= 3 , 0 , 0
       0     .16       0   676.7     .07       0   716.5     .16       0
Bank Sta=676.7,716.5
XS Rating Curve= 0 ,0
Exp/Cntr=0.3,0.1

Type RM Length L Ch R = 1 ,219     ,,,
XS GIS Cut Line= 4
     3618796.845    10272320.714     3618730.872    10272881.478
     3619157.956    10273468.283     3619545.108    10273617.589
#Sta/Elev= 30
       0   273.2   78.73  268.54   118.1  266.92  186.99  262.98  216.52  260.24
  285.41  261.92   305.1  261.55   354.3  261.99  373.99  261.49  433.04  261.64
  551.14  260.78  640.56  261.68   690.3  261.33  819.61  263.06  849.45  262.63
  929.03  263.09  948.93  259.27  958.87  260.56  968.82  263.06  988.72  263.05
  1048.4  264.98 1118.03  265.22 1167.77  266.57 1257.29  265.59 1306.97  266.72
 1326.81  267.83 1386.32  268.38 1554.93  273.54 1644.19  277.21  1703.7  280.89
#Mann= 4 ,-1 , 0
       0     .16       0  929.03     .07       0  968.82     .16       0
 1326.81     .05       0
Bank Sta=929.03,968.82
XS Rating Curve= 0 ,0
Exp/Cntr=0.3,0.1

Chan Stop Cuts=-1
Use User Specified Reach Order=0
Composite Channel Slope=5