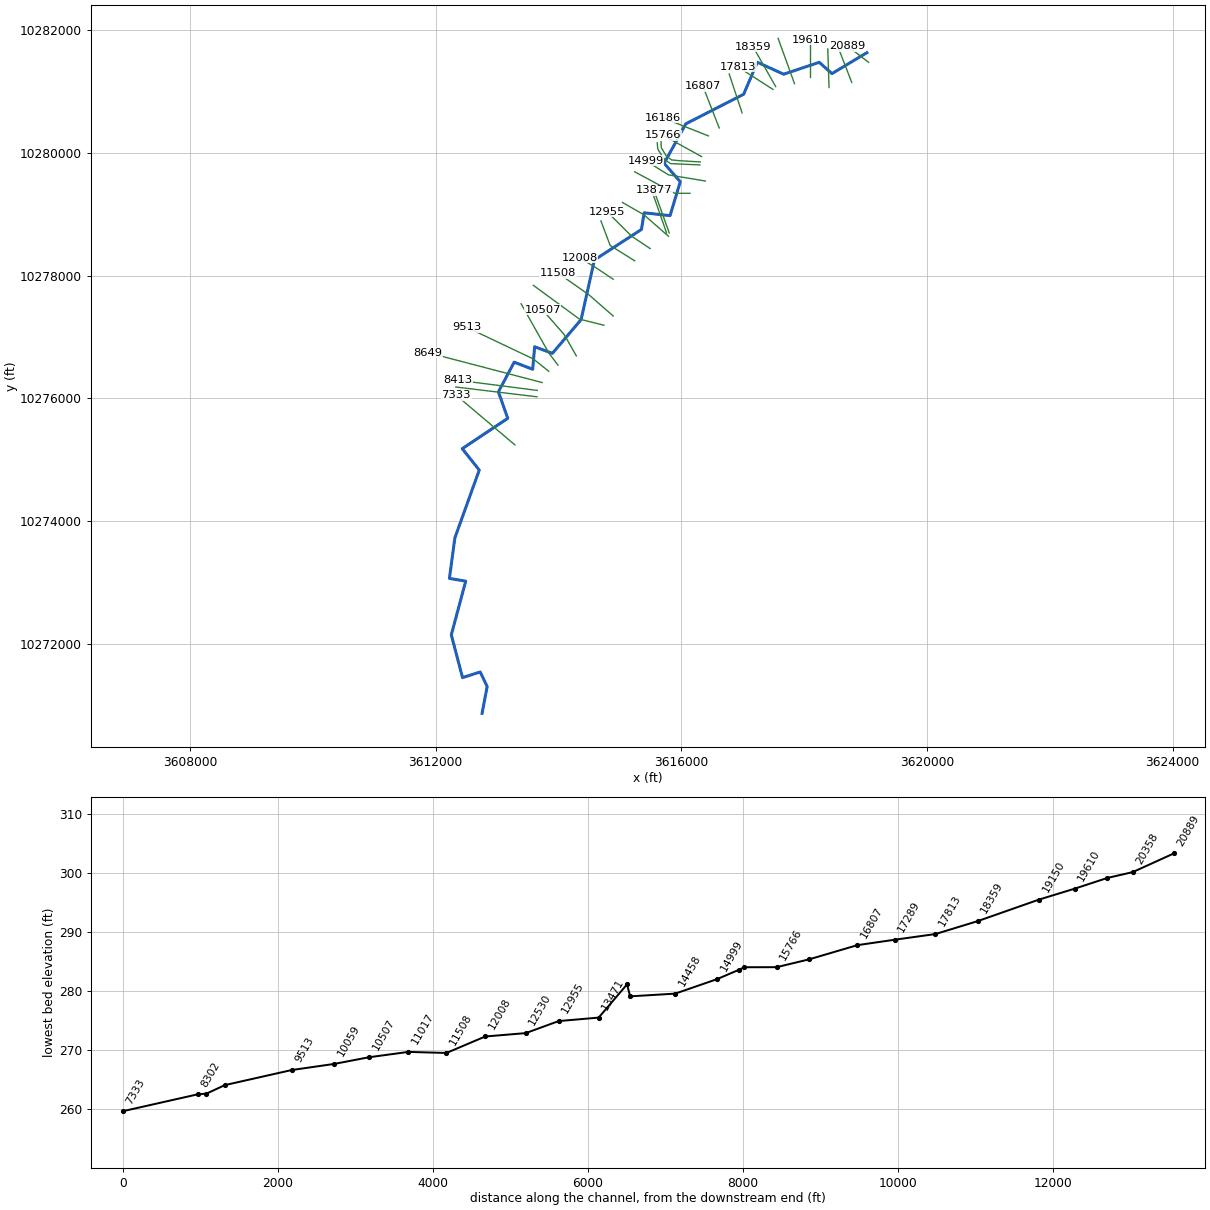
--- UNT0468 IN WICK.prj (project) ---

Proj Title=UNT0468 IN WICK Base Level Engineering
Current Plan=p01
Default Exp/Contr=0.3,0.1
English Units
Geom File=g01
Flow File=f01
Plan File=p01
Y Axis Title=Elevation
X Axis Title(PF)=Main Channel Distance
X Axis Title(XS)=Station
BEGIN DESCRIPTION:
UNT0468 IN WICK
END DESCRIPTION:
DSS Export Rating Curves= 0
DSS Export Rating Curve Sorted= 0
DSS Export Volume Flow Curves= 0
DXF OffsetX= 0
DXF OffsetY= 0
DXF ScaleX= 1
DXF ScaleY= 10

--- UNT0468 IN WICK.p01 (plan) ---

Plan Title=Multiple Run
Short Identifier=Multiple
Geom File=g01
Flow File=f01
Subcritical Flow
K Sum by GR= 0
Std Step Tol= 0.01
Critical Tol= 0.01
Num of Std Step Trials= 20
Max Error Tol= 0.3
Flow Tol Ratio= 0.001
Split Flow NTrial= 30
Split Flow Tol= 0.02
Split Flow Ratio= 0.02
Log Output Level= 0
Friction Slope Method= 1
Unsteady Friction Slope Method= 2
Unsteady Bridges Friction Slope Method= 1
Parabolic Critical Depth
Global Vel Dist=  1 , 1 , 1
Global Log Level= 0
CheckData=True
Encroach Param= -1, 0, 0, 0
BEGIN DESCRIPTION:
Multiple Run
END DESCRIPTION:

--- UNT0468 IN WICK.f01 (steady flow) ---

Flow Title=Multiple
Number of Profiles=7
Profile Names=10-year,25-year,50-year,1pct_min,100-year,1pct_plu,500-year
River Rch & RM= UNT0468 IN WICK,Reach-1,20889
     455     598     712     622     841    1137    1173
River Rch & RM= UNT0468 IN WICK,Reach-1,16186
     666     893    1077     951    1286    1740    1837
River Rch & RM= UNT0468 IN WICK,Reach-1,8302
     765    1032    1249    1106    1496    2023    2151
Boundary for River Rch & Prof#=UNT0468 IN WICK,Reach-1,1
Up Type=0
Dn Type=3
Dn Slope=0.005
Boundary for River Rch & Prof#=UNT0468 IN WICK,Reach-1,2
Up Type=0
Dn Type=3
Dn Slope=0.005
Boundary for River Rch & Prof#=UNT0468 IN WICK,Reach-1,3
Up Type=0
Dn Type=3
Dn Slope=0.005
Boundary for River Rch & Prof#=UNT0468 IN WICK,Reach-1,4
Up Type=0
Dn Type=3
Dn Slope=0.005
Boundary for River Rch & Prof#=UNT0468 IN WICK,Reach-1,5
Up Type=0
Dn Type=3
Dn Slope=0.005
Boundary for River Rch & Prof#=UNT0468 IN WICK,Reach-1,6
Up Type=0
Dn Type=3
Dn Slope=0.005
Boundary for River Rch & Prof#=UNT0468 IN WICK,Reach-1,7
Up Type=0
Dn Type=3
Dn Slope=0.005

--- UNT0468 IN WICK.g01 (geometry) ---

Geom Title=Existing Conditions
Program Version=4.10

River Reach=UNT0468 IN WICK ,Reach-1
Reach XY= 30
      3619022.01     10281632.98      3618453.72      10281291.7
      3618245.97     10281475.78       3617667.4     10281281.28
       3617239.3     10281477.04      3617015.83     10280955.06
      3616073.42     10280473.15      3615721.33     10279830.44
      3615983.83     10279529.92      3615817.69     10278977.31
       3615395.5     10279023.84      3615351.79     10278752.45
      3614585.77     10278255.51      3614369.35     10277283.33
      3613901.38     10276733.36      3613613.03     10276841.19
      3613580.49     10276474.34       3613279.6     10276589.65
      3613022.49     10276106.33       3613174.9     10275675.29
      3612433.79     10275180.46      3612710.88      10274832.2
      3612313.79     10273727.21      3612224.89     10273067.01
      3612490.19     10273021.62      3612255.72     10272146.81
      3612438.39     10271450.51      3612725.95      10271542.3
      3612839.61      10271305.5      3612756.38     10270867.79

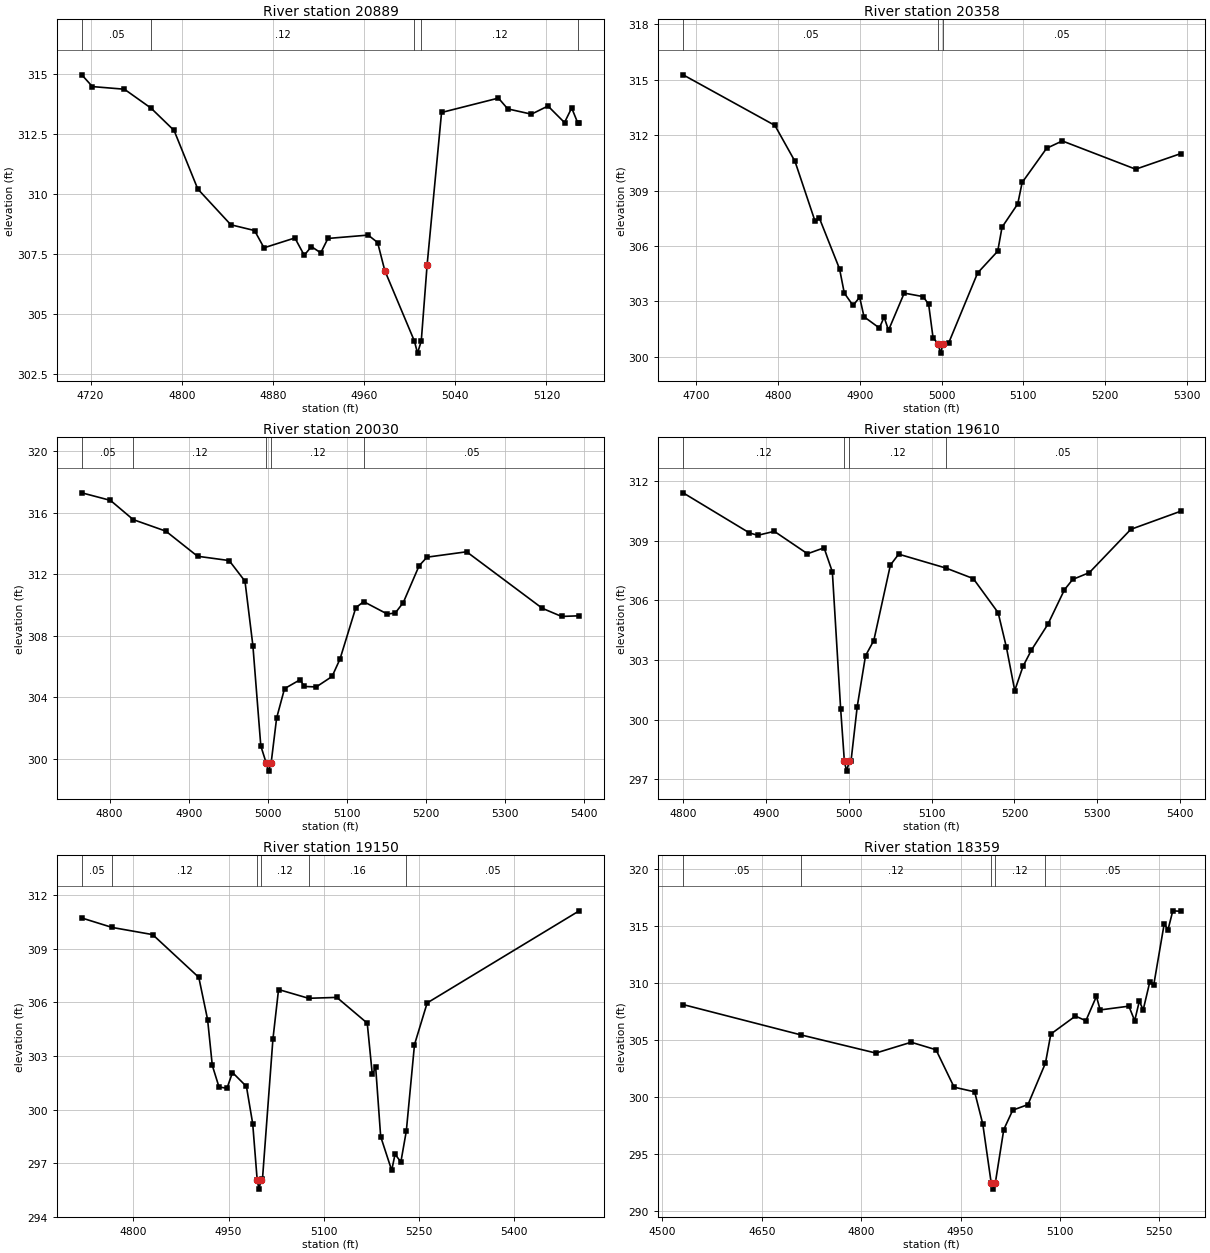
Type RM Length L Ch R = 1 ,20889   ,531,531,531
BEGIN DESCRIPTION:
UNT0468 IN WICK 39.0
END DESCRIPTION:
XS GIS Cut Line= 2
      3619049.47     10281475.92       3618703.1     10281741.56
#Sta/Elev= 30
  4712.3  314.97  4721.6  314.48  4749.7  314.37  4773.1  313.58  4793.3  312.65
  4814.1  310.21  4843.1  308.72  4863.9  308.48  4872.2  307.76  4899.3  308.17
  4907.5  307.45  4913.8  307.81    4922  307.55  4928.3  308.15  4963.6  308.29
  4971.9  307.98  4978.2  306.81  5004.2  303.87  5006.9  303.37  5010.2  303.87
 5015.34  307.05    5028   313.4  5077.9     314  5086.1  313.55  5106.9  313.33
  5121.4  313.67  5135.9  312.98  5142.2  313.59  5147.4  312.98  5148.8  312.98
#Mann= 5 ,-1 , 0
  4712.3     .05       0  4773.1     .12       0  5004.2     .07       0
  5010.2     .12       0  5147.4     .05       0
Bank Sta=4978.2,5015.34
XS Rating Curve= 0 ,0
Exp/Cntr=0.3,0.1

Type RM Length L Ch R = 1 ,20358   ,328,328,328
BEGIN DESCRIPTION:
Mapping XS 6e733511
END DESCRIPTION:
XS GIS Cut Line= 3
      3618776.05     10281147.77      3618557.29      10281712.9
      3618557.29      10281715.5
#Sta/Elev= 30
  4683.7  315.27    4796  312.53  4820.6  310.58  4845.2  307.33  4850.5   307.5
  4875.1  304.76  4880.9  303.45  4891.6  302.78  4899.7  303.23    4905  302.17
  4923.8  301.56  4929.6  302.15    4935  301.44  4954.2  303.45  4977.4  303.26
  4984.1  302.84  4989.5  301.03  4995.8   300.7  4998.6   300.2  5001.8   300.7
  5008.7  300.76    5044  304.54  5068.6  305.72  5073.9  307.02  5093.1  308.28
  5098.5  309.44  5128.4  311.29  5147.6  311.69  5237.4  310.16  5292.3     311
#Mann= 3 ,-1 , 0
  4683.7     .05       0  4995.8     .03       0  5001.8     .05       0
Bank Sta=4995.8,5001.8
XS Rating Curve= 0 ,0
Exp/Cntr=0.3,0.1

Type RM Length L Ch R = 1 ,20030   ,420,420,420
BEGIN DESCRIPTION:
UNT0468 IN WICK 38.0
END DESCRIPTION:
XS GIS Cut Line= 2
      3618406.41     10281065.44      3618385.58     10281693.89
#Sta/Elev= 30
  4764.9  317.29  4801.1   316.8  4829.9  315.55  4871.2   314.8  4911.2  313.17
  4951.2  312.89  4971.2  311.55  4981.2  307.36  4991.2  300.85  4998.2  299.71
    5001  299.21  5004.2  299.71  5011.2  302.66  5021.2  304.57    5041  305.15
    5046  304.71  5061.3  304.68  5081.3  305.36  5091.3  306.49  5111.3  309.83
  5121.3  310.22  5151.3  309.41  5161.3  309.49  5171.3  310.16  5191.3  312.55
  5201.3  313.11  5251.4  313.46    5347  309.79  5371.4  309.26  5393.7   309.3
#Mann= 5 ,-1 , 0
  4764.9     .05       0  4829.9     .12       0  4998.2     .07       0
  5004.2     .12       0  5121.3     .05       0
Bank Sta=4998.2,5004.2
XS Rating Curve= 0 ,0
Exp/Cntr=0.3,0.1

Type RM Length L Ch R = 1 ,19610   ,460,460,460
BEGIN DESCRIPTION:
UNT0468 IN WICK 37.0
END DESCRIPTION:
XS GIS Cut Line= 3
      3618092.11     10281241.66      3618092.11     10281441.64
      3618092.11     10281841.66
#Sta/Elev= 30
  4800.3  311.42  4880.3   309.4  4890.3  309.28  4910.3  309.48  4950.3  308.35
  4970.3  308.65  4980.3  307.44  4990.3  300.54  4994.8   297.9  4997.5   297.4
  5000.8   297.9  5002.8   297.9  5010.3  300.65  5020.3  303.21  5030.3  303.98
  5050.3  307.78  5060.3  308.33  5117.3  307.63  5150.3   307.1  5180.3  305.38
  5190.3  303.63  5200.3  301.46  5210.3  302.68  5220.3  303.49  5240.3   304.8
  5260.3  306.54  5270.3  307.06  5290.3   307.4  5340.3  309.58  5400.3  310.49
#Mann= 4 ,-1 , 0
  4800.3     .12       0  4994.8     .07       0  5000.8     .12       0
  5117.3     .05       0
Bank Sta=4994.8,5000.8
XS Rating Curve= 0 ,0
Exp/Cntr=0.3,0.1

Type RM Length L Ch R = 1 ,19150   ,791,791,791
BEGIN DESCRIPTION:
UNT0468 IN WICK 36.0
END DESCRIPTION:
XS GIS Cut Line= 2
      3617843.91     10281127.91      3617576.97     10281866.35
#Sta/Elev= 30
  4718.4  310.71  4766.4  310.18  4830.3  309.78  4903.1  307.39    4917  305.03
  4924.4  302.47    4935  301.26  4947.6  301.19  4956.3  302.07  4978.3  301.29
  4988.2  299.21  4995.3  296.05  4998.1  295.55  5001.3  296.05  5003.6   296.1
  5020.1  303.93    5029  306.71  5076.4  306.22    5121  306.27    5169  304.83
    5177  301.96  5182.3  302.37  5190.2  298.49  5207.6   296.6  5212.9   297.5
  5222.1  297.07  5230.7   298.8  5243.6  303.63  5263.6  305.96  5503.6  311.11
#Mann= 6 ,-1 , 0
  4718.4     .05       0  4766.4     .12       0  4995.3     .07       0
  5001.3     .12       0  5076.4     .16       0  5230.7     .05       0
Bank Sta=4995.3,5001.3
XS Rating Curve= 0 ,0
Exp/Cntr=0.3,0.1

Type RM Length L Ch R = 1 ,18359   ,546,546,546
BEGIN DESCRIPTION:
UNT0468 IN WICK 35.0
END DESCRIPTION:
XS GIS Cut Line= 2
      3617538.37     10281079.27      3617166.99     10281731.79
#Sta/Elev= 30
  4531.2  308.12  4708.7  305.46  4822.1  303.86  4875.4  304.81  4912.9  304.15
  4940.2  300.86  4971.2  300.45  4983.5  297.62  4996.3   292.4  4999.1   291.9
  5002.3   292.4  5015.2  297.14  5028.7  298.84  5051.7  299.33  5078.1  302.98
  5086.2  305.53  5123.3  307.11  5139.1   306.7    5155  308.84  5160.7  307.65
    5204  307.98  5212.8   306.7  5219.8  308.43  5225.6  307.65  5235.7  310.14
  5241.5  309.83  5257.3  315.21  5263.1   314.7  5270.3  316.36    5282  316.32
#Mann= 5 ,-1 , 0
  4531.2     .05       0  4708.7     .12       0  4996.3     .07       0
  5002.3     .12       0  5078.1     .05       0
Bank Sta=4996.3,5002.3
XS Rating Curve= 0 ,0
Exp/Cntr=0.3,0.1

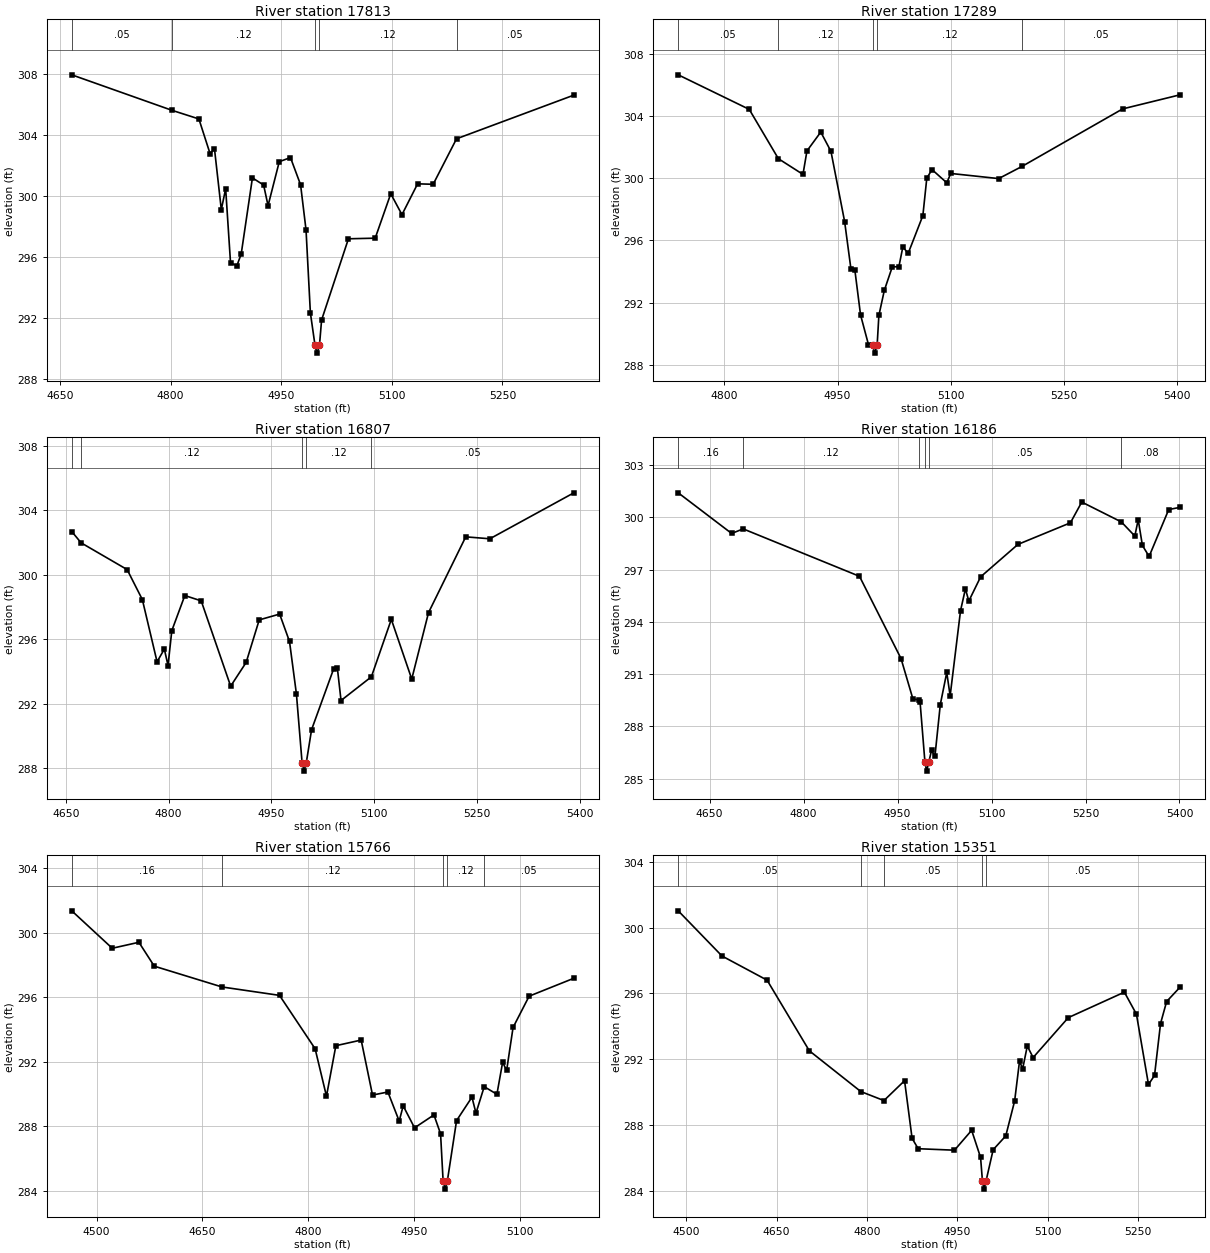
Type RM Length L Ch R = 1 ,17813   ,524,524,524
BEGIN DESCRIPTION:
UNT0468 IN WICK 34.0
END DESCRIPTION:
XS GIS Cut Line= 2
      3617493.21     10281034.16      3616920.33     10281402.19
#Sta/Elev= 30
  4665.9  307.94  4801.5  305.62  4838.3  305.05  4853.5  302.77  4859.4  303.11
  4868.7  299.11  4874.6  300.48  4881.2  295.63  4889.8  295.43  4895.7  296.21
  4910.9  301.19  4926.1  300.72  4932.1  299.37  4947.3  302.25  4962.5  302.52
  4976.2  300.74  4983.6  297.78  4989.5  292.35  4995.8  290.21  4998.5  289.71
  5001.8  290.21  5004.7  291.88  5041.1   297.2  5077.4  297.24  5098.5  300.15
  5113.7  298.78  5134.9   300.8    5156  300.77  5187.7  303.75  5346.8  306.61
#Mann= 5 ,-1 , 0
  4665.9     .05       0  4801.5     .12       0  4995.8     .07       0
  5001.8     .12       0  5187.7     .05       0
Bank Sta=4995.8,5001.8
XS Rating Curve= 0 ,0
Exp/Cntr=0.3,0.1

Type RM Length L Ch R = 1 ,17289   ,482,482,482
BEGIN DESCRIPTION:
UNT0468 IN WICK 33.0
END DESCRIPTION:
XS GIS Cut Line= 2
      3616989.74     10280652.23      3616781.41     10281284.18
#Sta/Elev= 30
  4738.9  306.64    4833  304.42  4871.6  301.25  4904.2  300.24  4909.5  301.75
  4927.8  302.96  4941.3  301.72  4959.4  297.21  4967.8  294.15    4973  294.08
  4980.5  291.21    4991   289.3  4996.5  289.25  4999.3  288.75  5002.5  289.25
  5004.8  291.17    5012  292.78  5022.6   294.3  5031.3   294.3  5036.6  295.58
  5043.6  295.16  5063.1  297.59  5068.3  299.99  5075.2  300.55  5094.8   299.7
  5100.1   300.3  5163.6  299.97  5194.4  300.75  5327.9  304.45  5404.3  305.36
#Mann= 5 ,-1 , 0
  4738.9     .05       0  4871.6     .12       0  4996.5     .07       0
  5002.5     .12       0  5194.4     .05       0
Bank Sta=4996.5,5002.5
XS Rating Curve= 0 ,0
Exp/Cntr=0.3,0.1

Type RM Length L Ch R = 1 ,16807   ,621,621,621
BEGIN DESCRIPTION:
UNT0468 IN WICK 32.0
END DESCRIPTION:
XS GIS Cut Line= 2
      3616618.22     10280405.68      3616351.45     10281088.19
#Sta/Elev= 30
  4658.6  302.69  4672.2  301.99  4739.4  300.33  4761.6  298.47  4783.1  294.61
  4793.7   295.4  4799.1  294.38  4804.6  296.54  4823.6  298.72  4847.5  298.39
  4890.5   293.1  4913.1  294.57  4932.2  297.21    4962  297.57  4976.4  295.87
  4986.5  292.61  4994.8  288.33  4997.6  287.83  5000.8  288.33  5008.6   290.4
  5040.8  294.17  5046.2  294.24  5051.6  292.21  5095.9  293.68    5125  297.24
  5154.8  293.54  5179.3  297.66  5233.6  302.36  5268.8  302.24  5391.4  305.09
#Mann= 5 ,-1 , 0
  4658.6     .16       0  4672.2     .12       0  4994.8     .07       0
  5000.8     .12       0  5095.9     .05       0
Bank Sta=4994.8,5000.8
XS Rating Curve= 0 ,0
Exp/Cntr=0.3,0.1

Type RM Length L Ch R = 1 ,16186   ,420,420,420
BEGIN DESCRIPTION:
UNT0468 IN WICK 30.0
END DESCRIPTION:
XS GIS Cut Line= 2
      3616441.11     10280277.22      3615695.84     10280571.86
#Sta/Elev= 30
  4599.9   301.4  4685.1  299.07  4703.6  299.33  4889.2  296.61  4955.5  291.89
  4974.5  289.57  4983.6  289.52  4985.9   289.4  4993.7  285.93  4996.4  285.43
  4999.7  285.93  5004.2  286.62  5009.6  286.27  5018.2  289.25  5028.5  291.09
  5033.9  289.75  5050.5  294.64  5058.3  295.89  5063.7  295.19  5082.6  296.58
  5142.1  298.44  5225.9  299.68    5244  300.87  5307.2  299.73  5328.7  298.92
  5334.1  299.86  5340.8  298.38  5351.5  297.75  5382.8  300.44  5401.3  300.57
#Mann= 6 ,-1 , 0
  4599.9     .16       0  4703.6     .12       0  4983.6     .05       0
  4993.7     .03       0  4999.7     .05       0  5307.2     .08       0
Bank Sta=4993.7,4999.7
XS Rating Curve= 0 ,0
Exp/Cntr=0.3,0.1

Type RM Length L Ch R = 1 ,15766   ,415,415,415
BEGIN DESCRIPTION:
UNT0468 IN WICK 29.0
END DESCRIPTION:
XS GIS Cut Line= 2
      3616330.05     10279940.39       3615706.6     10280284.27
#Sta/Elev= 30
  4464.9  301.35  4522.3  299.03  4560.1   299.4  4581.9  297.92    4678  296.63
  4759.5  296.11    4810   292.8  4826.1  289.86  4839.4  292.99  4875.3  293.34
  4891.4  289.93  4913.2  290.12  4929.2  288.32  4934.9  289.26    4951   287.9
  4978.5   288.7  4987.9  287.53  4991.5   284.6  4994.3   284.1  4997.5   284.6
  5010.6  288.35  5032.4   289.8  5038.1  288.81  5049.8  290.45  5067.8  289.98
  5075.9  291.96  5081.6  291.46  5090.7  294.12  5113.5  296.06  5176.9  297.17
#Mann= 5 ,-1 , 0
  4464.9     .16       0    4678     .12       0  4991.5     .07       0
  4997.5     .12       0  5049.8     .05       0
Bank Sta=4991.5,4997.5
XS Rating Curve= 0 ,0
Exp/Cntr=0.3,0.1

Type RM Length L Ch R = 1 ,15351   ,67,67,67
BEGIN DESCRIPTION:
Mapping XS 8345dc06
END DESCRIPTION:
XS GIS Cut Line= 6
      3616309.26     10279852.28      3615983.76     10279871.81
      3615844.44     10279884.83       3615758.5     10279946.03
      3615675.17     10280085.35      3615669.96     10280184.36
#Sta/Elev= 30
  4486.7  301.03  4559.3  298.28  4634.1  296.81  4704.2  292.51  4789.6  290.03
    4828  289.48  4862.2  290.69  4874.7  287.18  4884.8  286.55    4945  286.46
  4973.5  287.67  4988.3  286.02  4991.4  284.59  4994.2  284.09  4997.4  284.59
  5009.2  286.49  5030.1  287.33  5044.8  289.45  5052.9  291.87  5058.2  291.42
  5065.8   292.8  5075.5   292.1  5133.9  294.53  5226.9  296.08  5246.9  294.74
  5266.9  290.46  5276.9  291.01  5286.9  294.17    5297  295.51  5319.7   296.4
#Mann= 5 ,-1 , 0
  4486.7     .05       0  4789.6     .12       0    4828     .05       0
  4991.4     .03       0  4997.4     .05       0
Bank Sta=4991.4,4997.4
XS Rating Curve= 0 ,0
Exp/Cntr=0.3,0.1

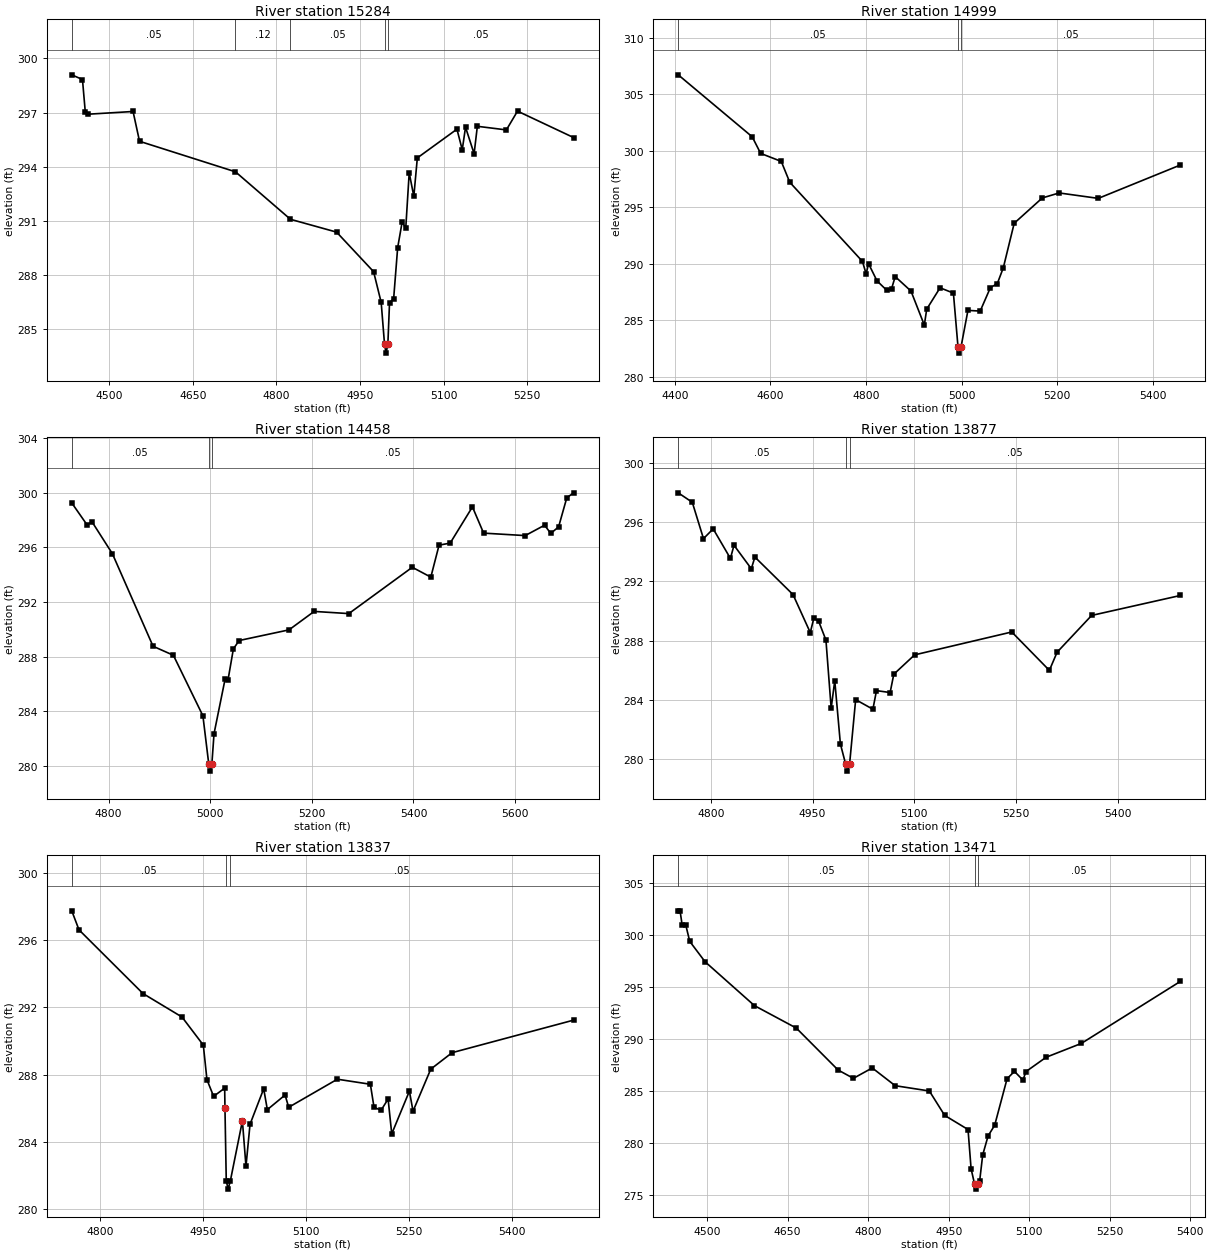
Type RM Length L Ch R = 1 ,15284   ,285,285,285
BEGIN DESCRIPTION:
Mapping XS 097b771d
END DESCRIPTION:
XS GIS Cut Line= 6
      3616301.47      10279804.1      3615827.51     10279824.94
      3615735.06     10279886.13      3615688.19     10279948.63
      3615616.58     10280064.52      3615608.76      10280164.8
#Sta/Elev= 30
  4432.8  299.09    4452  298.83    4457  297.05  4462.3  296.91  4542.8  297.06
  4554.4  295.41  4726.6  293.72  4825.3  291.09  4908.1  290.38  4974.5  288.19
  4988.1  286.49  4994.1  284.18  4996.9  283.68  5000.1  284.18  5003.1  286.47
  5010.5   286.7  5017.7  289.52  5025.8  290.95  5032.2  290.59  5038.4  293.67
  5046.7  292.36    5053  294.49  5124.1  296.08  5133.6  294.94  5139.5  296.19
  5154.9  294.72  5160.7  296.24  5212.8  296.04  5232.8  297.08  5333.9  295.61
#Mann= 5 ,-1 , 0
  4432.8     .05       0  4726.6     .12       0  4825.3     .05       0
  4994.1     .03       0  5000.1     .05       0
Bank Sta=4994.1,5000.1
XS Rating Curve= 0 ,0
Exp/Cntr=0.3,0.1

Type RM Length L Ch R = 1 ,14999   ,541,541,541
BEGIN DESCRIPTION:
UNT0468 IN WICK 28.0
END DESCRIPTION:
XS GIS Cut Line= 3
      3616392.08     10279541.65      3615792.11     10279641.64
      3615416.97     10279874.34
#Sta/Elev= 30
  4407.4   306.7    4562  301.22  4579.7  299.75  4622.8  299.04  4640.5   297.2
  4792.6  290.19  4800.2  289.09  4805.3  289.99    4823  288.47  4843.3  287.64
  4853.4  287.77    4861  288.85    4894  287.57  4921.9  284.56  4926.9  285.97
  4954.8  287.86  4982.7  287.39  4992.4  282.58  4995.1  282.08  4998.4  282.58
  5013.1  285.86  5038.7   285.8    5060  287.87  5074.5  288.23  5087.1  289.64
  5109.8  293.57  5168.6  295.81  5203.9  296.25  5285.6  295.77  5457.1  298.72
#Mann= 3 ,-1 , 0
  4407.4     .05       0  4992.4     .03       0  4998.4     .05       0
Bank Sta=4992.4,4998.4
XS Rating Curve= 0 ,0
Exp/Cntr=0.3,0.1

Type RM Length L Ch R = 1 ,14458   ,581,581,581
BEGIN DESCRIPTION:
UNT0468 IN WICK 27.0
END DESCRIPTION:
XS GIS Cut Line= 3
      3616142.08     10279341.64      3615892.11     10279341.64
      3615242.12     10279691.63
#Sta/Elev= 30
  4727.4  299.25  4757.4  297.65  4767.4  297.86  4807.4  295.53  4887.4  288.76
  4927.4   288.1  4985.5  283.67  4997.1  280.12  4999.8  279.62  5003.1  280.12
  5007.4  282.36  5029.3  286.38    5035  286.31  5045.5  288.57  5056.9  289.18
    5155  289.96  5204.5  291.31  5272.7  291.15  5397.6  294.54  5434.1  293.82
  5450.3  296.16  5472.2  296.31    5516  298.96    5538  297.04  5619.9  296.86
    5658  297.62  5670.2  297.02  5685.6   297.5  5701.8  299.64  5715.6  299.99
#Mann= 3 ,-1 , 0
  4727.4     .05       0  4997.1     .03       0  5003.1     .05       0
Bank Sta=4997.1,5003.1
XS Rating Curve= 0 ,0
Exp/Cntr=0.3,0.1

Type RM Length L Ch R = 1 ,13877   ,40,40,40
BEGIN DESCRIPTION:
UNT0468 IN WICK 26.0
END DESCRIPTION:
XS GIS Cut Line= 2
      3615803.91     10278696.67      3615554.33     10279393.31
#Sta/Elev= 30
  4752.1     298  4772.8  297.36  4789.3   294.9  4803.6  295.56    4829  293.56
  4834.3  294.45  4859.8  292.86  4865.1  293.65  4921.3  291.11  4946.7  288.54
    4952  289.52  4959.2  289.29  4969.8  288.03  4977.5  283.42  4982.8  285.28
  4991.1     281  4998.7  279.66  5001.5  279.16  5004.7  279.66  5013.6     284
    5039  283.35  5044.3  284.61  5064.4  284.48  5069.8  285.72  5100.5  287.03
  5243.7  288.58  5299.1  285.98  5310.5  287.21  5361.4   289.7  5492.1  291.05
#Mann= 3 ,-1 , 0
  4752.1     .05       0  4998.7     .03       0  5004.7     .05       0
Bank Sta=4998.7,5004.7
XS Rating Curve= 0 ,0
Exp/Cntr=0.3,0.1

Type RM Length L Ch R = 1 ,13837   ,366,366,366
BEGIN DESCRIPTION:
Mapping XS adce7bb0
END DESCRIPTION:
XS GIS Cut Line= 2
      3615760.51     10278696.64      3615519.64     10279386.71
#Sta/Elev= 30
  4758.6  297.75  4769.1  296.62  4862.2  292.83  4919.1  291.43  4950.1  289.76
  4955.4   287.7  4965.1  286.71  4981.2   287.2  4981.6  286.04  4983.5  281.69
  4986.2  281.19  4989.5  281.69    5007  285.25  5012.2  282.55  5018.1  285.05
    5038  287.16  5043.3  285.92  5069.1  286.79  5074.4  286.06  5145.2  287.73
  5193.3  287.43  5198.6  286.06  5208.8  285.88  5219.1  286.55  5224.4  284.48
  5250.1  287.02  5255.4  285.83  5281.2  288.33  5312.3  289.31  5489.5  291.25
#Mann= 3 ,-1 , 0
  4758.6     .05       0  4983.5     .03       0  4989.5     .05       0
Bank Sta=4981.6,5007
XS Rating Curve= 0 ,0
Exp/Cntr=0.3,0.1

Type RM Length L Ch R = 1 ,13471   ,516,516,516
BEGIN DESCRIPTION:
UNT0468 IN WICK 25.0
END DESCRIPTION:
XS GIS Cut Line= 3
      3615792.14     10278641.61      3615392.11     10278991.64
      3615042.07     10279191.66
#Sta/Elev= 30
  4446.5  302.36  4449.9  302.36  4453.7  301.02  4460.3  301.04  4467.9  299.42
  4496.4  297.46  4588.4  293.23  4666.3  291.07  4744.1  287.03  4772.6  286.23
  4807.7  287.23  4850.4  285.52    4914  285.01  4942.5  282.66    4986   281.3
  4991.7  277.52  4998.1  276.06  5000.8  275.56  5004.1  276.06  5007.6  276.32
  5013.3  278.85  5023.4  280.69  5035.6  281.71  5058.7  286.19  5072.4   286.9
  5088.2  286.06  5093.9  286.88  5131.4  288.26  5196.9  289.59  5381.2  295.56
#Mann= 3 ,-1 , 0
  4446.5     .05       0  4998.1     .03       0  5004.1     .05       0
Bank Sta=4998.1,5004.1
XS Rating Curve= 0 ,0
Exp/Cntr=0.3,0.1

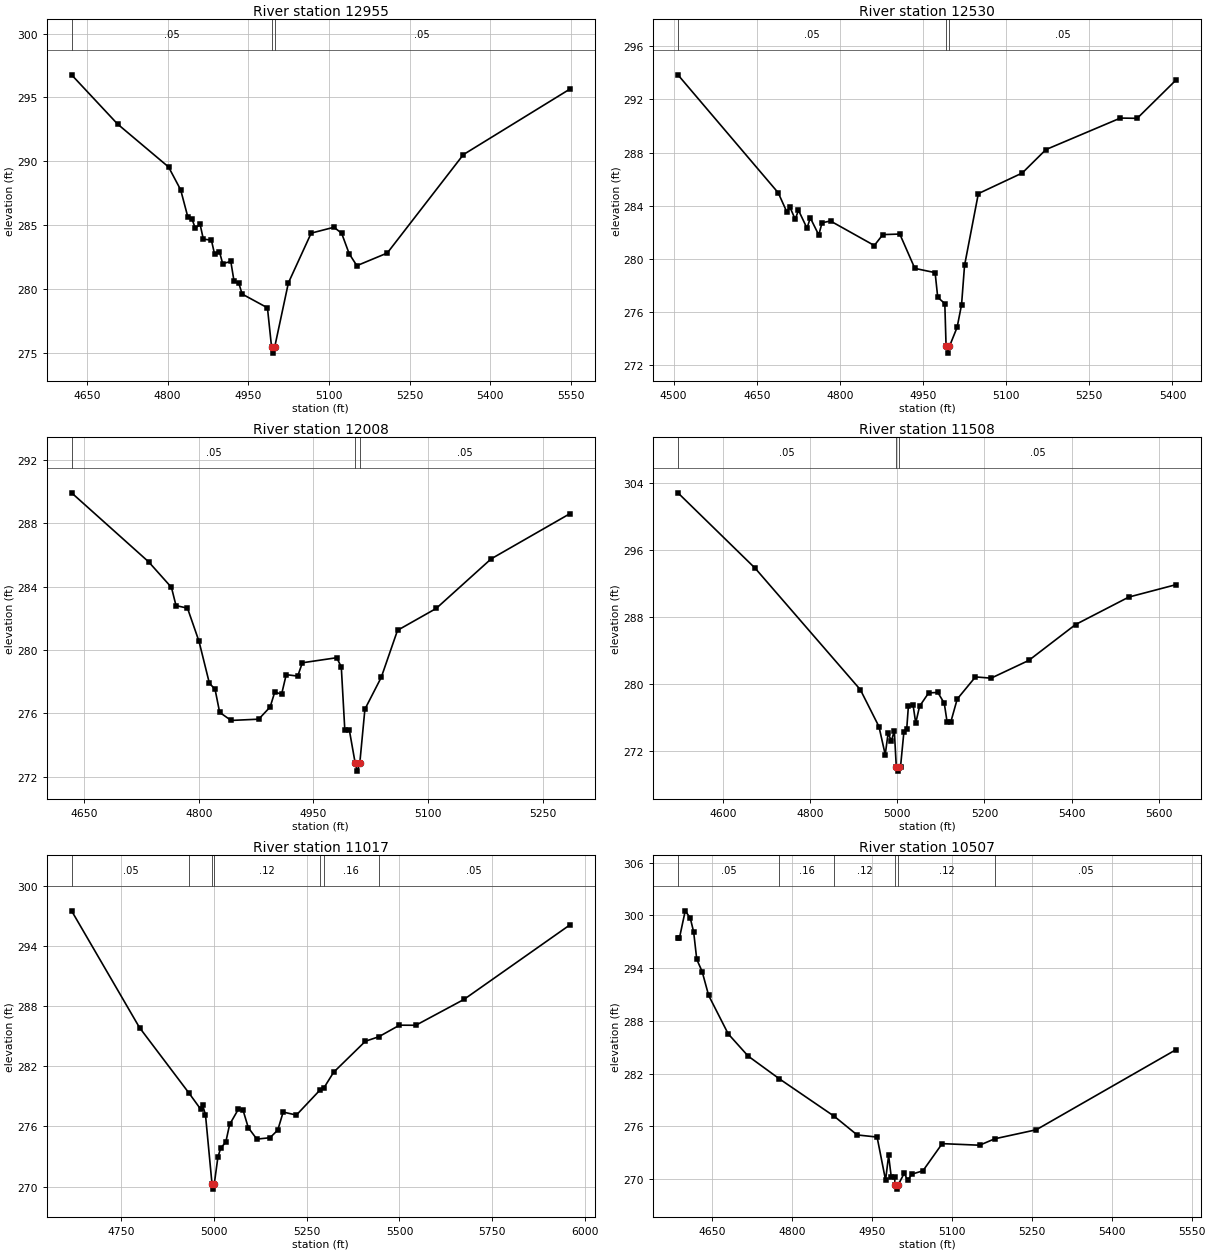
Type RM Length L Ch R = 1 ,12955   ,425,425,425
BEGIN DESCRIPTION:
UNT0468 IN WICK 24.0
END DESCRIPTION:
XS GIS Cut Line= 3
      3615492.11     10278441.64      3615192.11     10278641.64
      3614792.14     10279041.61
#Sta/Elev= 30
  4621.6  296.77  4707.2  292.91  4801.9  289.55  4824.4  287.76  4837.9   285.6
  4845.4  285.48  4851.5  284.76  4860.5  285.06  4866.5   283.9  4881.5  283.82
  4887.5  282.71  4896.5  282.91  4902.5  281.98  4917.6  282.15  4923.6   280.6
  4932.6  280.43  4938.6   279.6  4985.7  278.52  4993.3  275.47  4996.1  274.97
  4999.3  275.47  5024.6  280.47    5067  284.37  5109.4  284.83  5123.6  284.36
  5137.7  282.75  5151.9  281.82  5208.4  282.81  5349.9  290.52  5547.8  295.65
#Mann= 3 ,-1 , 0
  4621.6     .05       0  4993.3     .03       0  4999.3     .05       0
Bank Sta=4993.3,4999.3
XS Rating Curve= 0 ,0
Exp/Cntr=0.3,0.1

Type RM Length L Ch R = 1 ,12530   ,522,522,522
BEGIN DESCRIPTION:
UNT0468 IN WICK 23.0
END DESCRIPTION:
XS GIS Cut Line= 3
      3615242.07     10278241.66      3614842.11     10278491.64
      3614692.09     10278891.68
#Sta/Elev= 30
  4507.8  293.85  4688.8  284.98  4704.1  283.56    4710  283.89  4719.4  282.99
  4725.3  283.67  4740.7  282.32  4746.6   283.1  4761.9  281.81  4767.8  282.73
  4783.1  282.86  4862.1  281.02  4877.5  281.84  4908.1  281.88  4935.2   279.3
  4971.8  278.98  4976.5  277.13  4989.3  276.65  4991.6  273.43  4994.3  272.93
  4997.6  273.43  5011.5  274.87  5019.5  276.57  5024.9  279.52  5049.8  284.92
    5129  286.47  5171.7  288.23  5306.1   290.6  5336.4  290.58  5406.7  293.47
#Mann= 3 ,-1 , 0
  4507.8     .05       0  4991.6     .03       0  4997.6     .05       0
Bank Sta=4991.6,4997.6
XS Rating Curve= 0 ,0
Exp/Cntr=0.3,0.1

Type RM Length L Ch R = 1 ,12008   ,500,500,500
BEGIN DESCRIPTION:
UNT0468 IN WICK 22.0
END DESCRIPTION:
XS GIS Cut Line= 3
      3614892.11     10277941.64      3614592.11     10278141.64
      3614342.11     10278291.64
#Sta/Elev= 30
  4633.4  289.93  4734.1  285.58  4764.1  283.96  4770.1  282.81  4785.1  282.65
  4800.2  280.55  4813.7  277.92  4821.2  277.52  4827.2  276.07  4842.2  275.56
  4878.3  275.64  4893.3  276.41  4899.3  277.35  4908.3  277.22  4914.3  278.45
  4929.4  278.36  4935.4   279.2  4980.4  279.52  4986.4  278.94    4991  274.96
  4996.9  274.96  5004.6  272.86  5007.3  272.36  5010.6  272.86  5017.3  276.27
  5038.7  278.28    5060  281.25  5110.6  282.63  5182.5  285.76  5285.5  288.61
#Mann= 3 ,-1 , 0
  4633.4     .05       0  5004.6     .03       0  5010.6     .05       0
Bank Sta=5004.6,5010.6
XS Rating Curve= 0 ,0
Exp/Cntr=0.3,0.1

Type RM Length L Ch R = 1 ,11508   ,491,491,491
BEGIN DESCRIPTION:
UNT0468 IN WICK 21.0
END DESCRIPTION:
XS GIS Cut Line= 3
      3614892.12     10277341.63      3614492.11     10277691.64
      3613992.07     10278041.67
#Sta/Elev= 30
  4497.4  302.86  4674.4  293.84  4915.5  279.31  4958.2  274.89  4972.5  271.54
  4979.1  274.11  4986.7  273.16  4993.3  274.42  4997.9  270.07  5000.7  269.57
  5003.9  270.07  5007.6  270.11  5015.2  274.21  5021.8  274.63  5025.6  277.34
  5036.3  277.49  5042.4  275.32  5051.2  277.33  5072.1  278.93    5093  278.98
  5107.8   277.7  5114.4  275.42  5122.7  275.43  5137.5  278.19  5179.3  280.84
  5215.1  280.69  5301.4  282.81  5408.6   287.1  5530.7  290.39  5639.3  291.88
#Mann= 3 ,-1 , 0
  4497.4     .05       0  4997.9     .03       0  5003.9     .05       0
Bank Sta=4997.9,5003.9
XS Rating Curve= 0 ,0
Exp/Cntr=0.3,0.1

Type RM Length L Ch R = 1 ,11017   ,510,510,510
BEGIN DESCRIPTION:
UNT0468 IN WICK 20.0
END DESCRIPTION:
XS GIS Cut Line= 3
      3614742.11     10277191.64      3614342.11     10277291.64
      3613592.08     10277841.66
#Sta/Elev= 30
  4616.6  297.52  4799.6  285.87  4933.6   279.3  4964.5  277.72  4969.6  278.14
  4977.4  277.15    4995  270.25  4997.7  269.75    5001  270.25  5010.9  272.96
  5018.6  273.86    5032  274.43  5042.4   276.2  5065.6   277.7  5078.5  277.64
  5092.6  275.89  5115.7  274.74  5151.2  274.88  5172.1  275.64  5186.7  277.44
  5222.3  277.14  5285.2  279.61  5295.9  279.82  5322.6  281.41  5408.3  284.51
  5444.1  284.95  5500.1  286.11  5544.1   286.1  5673.8  288.68    5959  296.11
#Mann= 7 ,-1 , 0
  4616.6     .05       0  4933.6     .12       0    4995     .07       0
    5001     .12       0  5285.2     .05       0  5295.9     .16       0
  5444.1     .05       0
Bank Sta=4995,5001
XS Rating Curve= 0 ,0
Exp/Cntr=0.3,0.1

Type RM Length L Ch R = 1 ,10507   ,448,448,448
BEGIN DESCRIPTION:
UNT0468 IN WICK 19.0
END DESCRIPTION:
XS GIS Cut Line= 3
      3614292.11     10276691.63      3614092.11     10277041.64
      3613742.13     10277441.62
#Sta/Elev= 30
  4586.4  297.45  4589.3  297.45  4600.1  300.53  4609.5  299.71  4615.9  298.13
  4621.7  295.01  4631.8  293.62    4644   290.9  4680.7  286.52  4718.1  283.99
  4776.9  281.39  4879.9  277.12  4922.6  275.01    4960  274.77  4975.9  269.86
  4981.6  272.67  4986.6  270.21  4992.9  270.21  4993.6  269.34  4996.4  268.84
  4999.6  269.34  5010.9  270.64  5017.5  269.85  5025.1  270.54    5046  270.93
  5082.1  274.02  5152.3  273.84  5180.6  274.57  5258.6   275.6    5521  284.73
#Mann= 6 ,-1 , 0
  4586.4     .05       0  4776.9     .16       0  4879.9     .12       0
  4993.6     .07       0  4999.6     .12       0  5180.6     .05       0
Bank Sta=4993.6,4999.6
XS Rating Curve= 0 ,0
Exp/Cntr=0.3,0.1

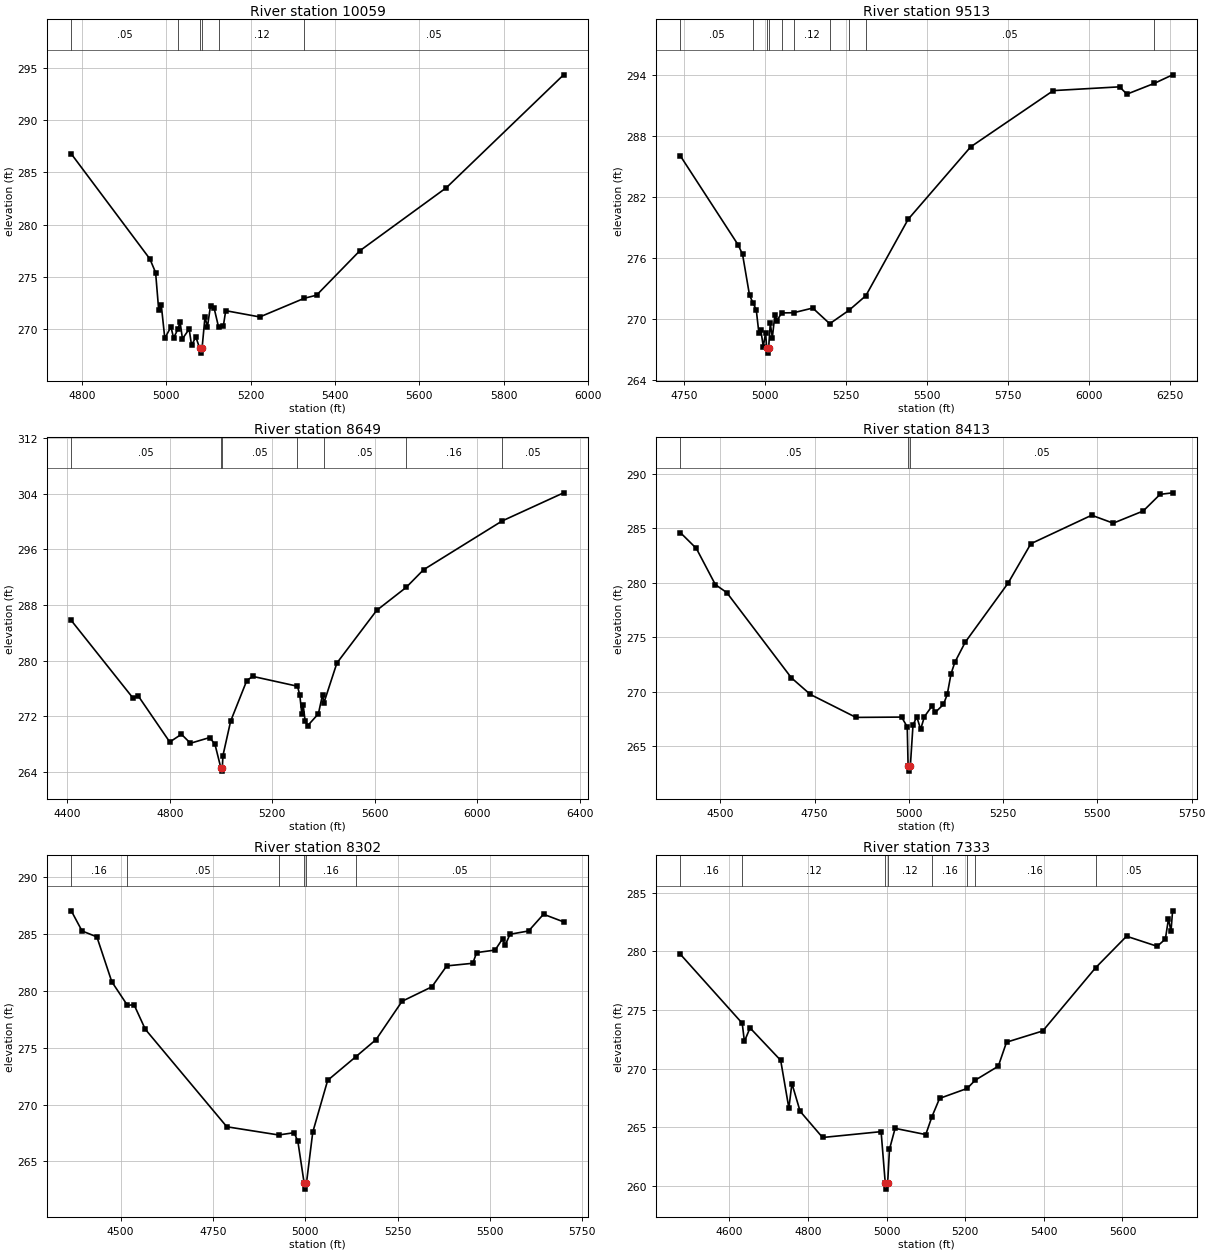
Type RM Length L Ch R = 1 ,10059   ,546,546,546
BEGIN DESCRIPTION:
UNT0468 IN WICK 18.0
END DESCRIPTION:
XS GIS Cut Line= 3
      3613992.08     10276541.67      3613842.11     10276741.64
      3613392.12     10277541.61
#Sta/Elev= 30
  4774.7  286.77  4961.1  276.72  4974.7  275.42    4982  271.86  4988.2   272.3
  4996.5  269.13  5011.1  270.22  5017.4  269.16  5028.3  270.06  5032.6  270.73
  5038.4  269.08  5054.3  270.01    5060  268.46  5070.2  269.25    5079  268.21
  5081.8  267.71    5085  268.21  5091.9  271.19  5097.6   270.2    5105  272.26
  5113.6     272  5124.2  270.18  5135.3  270.27    5141  271.77  5221.9  271.17
  5327.6  272.96  5356.4  273.25  5459.1   277.5  5664.3  283.53  5942.5  294.33
#Mann= 6 ,-1 , 0
  4774.7     .05       0  5028.3     .16       0    5079    .035       0
    5085     .16       0  5124.2     .12       0  5327.6     .05       0
Bank Sta=5079,5085
XS Rating Curve= 0 ,0
Exp/Cntr=0.3,0.1

Type RM Length L Ch R = 1 ,9513    ,864,864,864
BEGIN DESCRIPTION:
UNT0468 IN WICK 17.0
END DESCRIPTION:
XS GIS Cut Line= 3
       3613842.1     10276441.65      3613592.11     10276641.64
      3612509.63     10277157.12
#Sta/Elev= 30
  4737.6  286.08  4916.1  277.32  4929.7   276.4  4951.3  272.37  4961.8  271.64
  4972.1  270.93  4980.1  268.68  4986.5  268.91  4993.7  267.31  5000.9  268.69
  5004.3  267.18  5007.1  266.68  5010.3  267.18  5015.3   269.6  5021.7  268.21
  5029.7  270.47  5036.1  269.87  5050.4  270.63  5087.3  270.65  5146.4  271.11
  5198.8  269.57  5258.6   270.9  5310.2  272.32  5440.7  279.83  5633.7  286.95
  5888.7  292.48  6093.1  292.85  6115.8  292.13  6200.9   293.2  6256.7  294.03
#Mann= 10 ,-1 , 0
  4737.6     .05       0  4961.8     .12       0  5004.3     .07       0
  5010.3     .12       0  5050.4     .05       0  5087.3     .12       0
  5198.8     .05       0  5258.6     .16       0  5310.2     .05       0
  6200.9     .16       0
Bank Sta=5004.3,5010.3
XS Rating Curve= 0 ,0
Exp/Cntr=0.3,0.1

Type RM Length L Ch R = 1 ,8649    ,236,236,236
BEGIN DESCRIPTION:
Mapping XS 5fa02f37
END DESCRIPTION:
XS GIS Cut Line= 2
      3613734.29     10276258.31      3611876.83     10276744.38
#Sta/Elev= 30
  4415.8  285.79  4655.8  274.66  4676.5  274.96  4799.8  268.31  4845.4  269.42
  4880.6  268.13  4955.6  268.95  4976.2  267.97  4998.9  264.62  5001.7  264.12
  5004.9  264.62  5007.2  266.34  5037.2   271.3  5100.3  277.15  5123.2  277.75
  5297.9  276.33    5307  275.06    5315  272.28  5320.1  273.63  5327.7  271.37
    5338  270.67  5379.4  272.36  5395.8  275.12    5401  273.94  5451.7  279.67
  5606.8  287.24  5721.6  290.54  5789.7  293.09    6096   300.1  6335.8  304.15
#Mann= 7 ,-1 , 0
  4415.8     .05       0  4998.9     .03       0  5004.9     .05       0
  5297.9     .16       0    5401     .05       0  5721.6     .16       0
    6096     .05       0
Bank Sta=4998.9,5004.9
XS Rating Curve= 0 ,0
Exp/Cntr=0.3,0.1

Type RM Length L Ch R = 1 ,8413    ,111,111,111
BEGIN DESCRIPTION:
UNT0468 IN WICK 16.0
END DESCRIPTION:
XS GIS Cut Line= 2
       3613654.4     10276129.84      3612359.28     10276296.51
#Sta/Elev= 30
  4393.6  284.62  4436.2  283.16  4486.7  279.83  4516.9   279.1  4688.3  271.26
  4738.7  269.73  4859.7  267.62  4980.7  267.65  4995.6  266.75  4997.9  263.18
  5000.6  262.68  5003.9  263.18  5010.9  266.91    5021  267.68  5031.1  266.52
  5041.2  267.69  5061.4  268.67    5070  268.08  5091.6  268.81  5101.7  269.73
  5111.8  271.63  5121.9  272.69  5149.5  274.54    5263  279.96  5323.5  283.59
  5484.8  286.21    5542  285.48  5621.5   286.6  5666.3  288.13  5699.4  288.27
#Mann= 3 ,-1 , 0
  4393.6     .05       0  4997.9     .04       0  5003.9     .05       0
Bank Sta=4997.9,5003.9
XS Rating Curve= 0 ,0
Exp/Cntr=0.3,0.1

Type RM Length L Ch R = 1 ,8302    ,969,969,969
BEGIN DESCRIPTION:
UNT0468 IN WICK 15.0
END DESCRIPTION:
XS GIS Cut Line= 2
      3613650.96     10276025.67      3612328.06     10276185.39
#Sta/Elev= 30
  4366.6  287.03  4395.7  285.26  4435.9  284.74  4476.2   280.8  4518.5  278.73
  4536.6  278.77  4566.9  276.62  4787.6  268.05  4927.9  267.33  4969.8  267.53
  4979.9  266.76    4997  263.07  4999.8  262.57    5003  263.07  5020.2  267.58
  5060.5  272.13  5137.2  274.22  5191.4  275.71  5261.9  279.08  5342.5  280.35
  5382.8  282.19  5453.3  282.42  5463.8  283.36  5513.7  283.58  5533.9  284.57
  5540.8  283.99    5554  284.97  5604.4  285.26  5644.7  286.73  5699.1  286.06
#Mann= 6 ,-1 , 0
  4366.6     .16       0  4518.5     .05       0  4927.9     .16       0
    4997     .07       0    5003     .16       0  5137.2     .05       0
Bank Sta=4997,5003
XS Rating Curve= 0 ,0
Exp/Cntr=0.3,0.1

Type RM Length L Ch R = 1 ,7333    ,523,523,523
BEGIN DESCRIPTION:
UNT0468 IN WICK 14.0
END DESCRIPTION:
XS GIS Cut Line= 2
      3613292.13     10275241.62      3612336.01     10276050.84
#Sta/Elev= 30
  4474.9  279.77  4632.5  273.87  4638.1  272.32  4652.4  273.47  4730.4   270.7
  4751.2  266.62    4759  268.72  4779.8  266.35    4837  264.11  4985.9  264.61
  4996.5   260.2  4999.3   259.7  5002.5   260.2  5007.2   263.1  5021.5  264.89
  5099.5  264.36  5115.4   265.9  5134.7  267.45  5204.9   268.3  5225.1     269
  5284.1   270.2    5305  272.25  5397.2  273.21  5531.7  278.61  5610.4   281.3
  5688.4  280.44  5709.2  281.06    5717  282.78  5723.5  281.73  5727.5  283.47
#Mann= 8 ,-1 , 0
  4474.9     .16       0  4632.5     .12       0  4996.5     .07       0
  5002.5     .12       0  5115.4     .16       0  5204.9     .12       0
  5225.1     .16       0  5531.7     .05       0
Bank Sta=4996.5,5002.5
XS Rating Curve= 0 ,0
Exp/Cntr=0.3,0.1