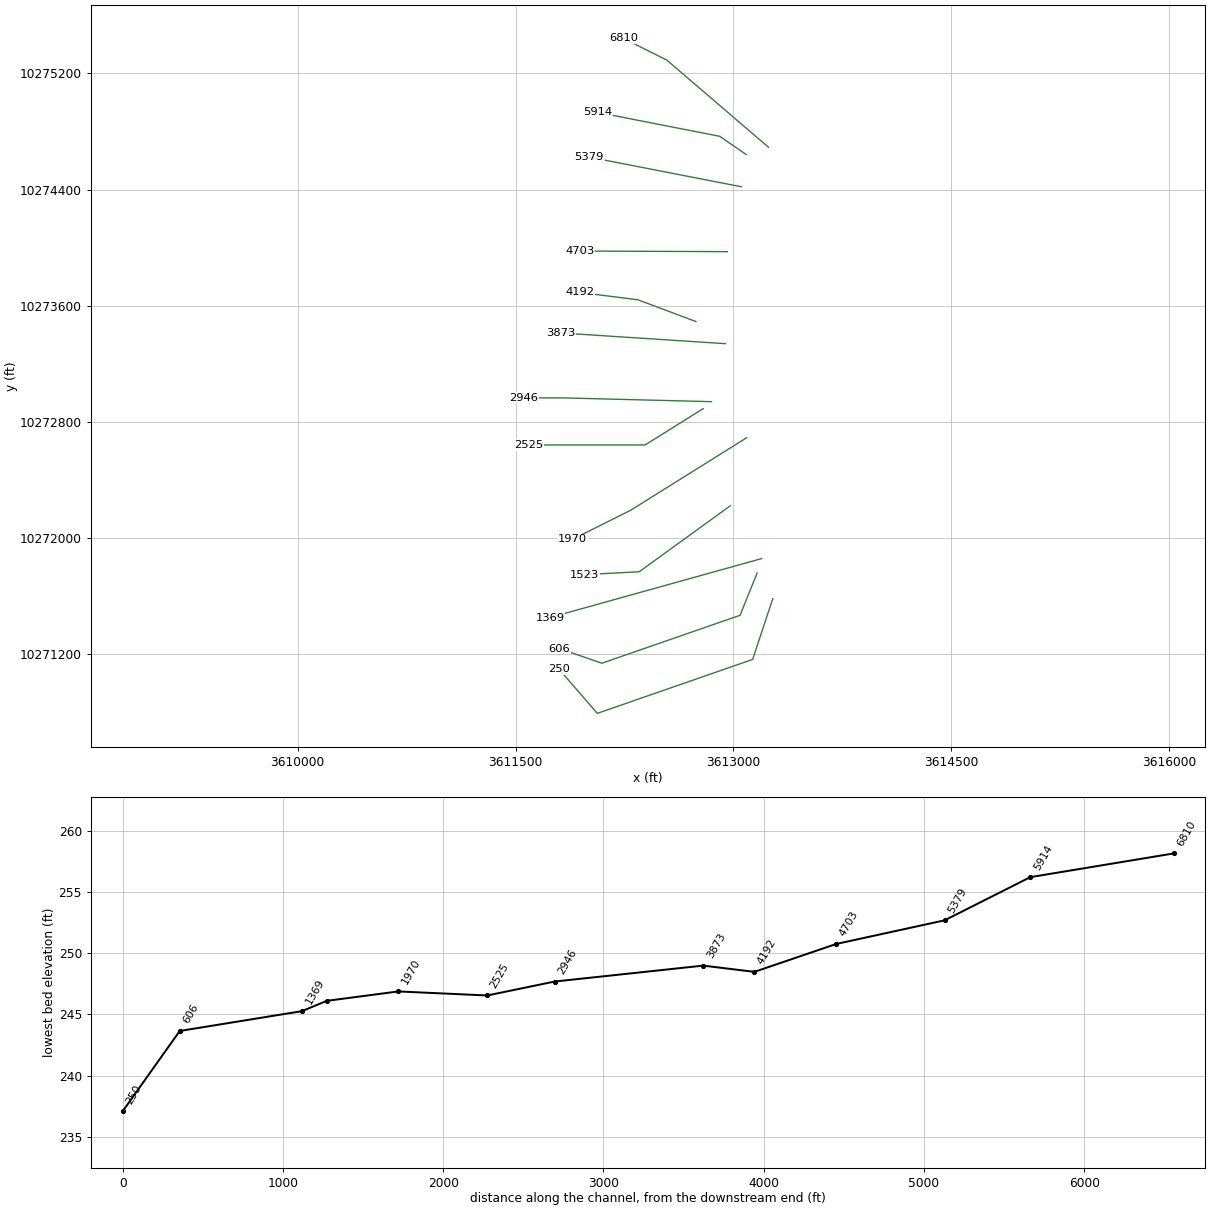
HEC-RAS study UNT0468 IN WICK.prj: UNT0468 IN WICK Base Level Engineering

--- UNT0468 IN WICK.g01 (geometry) --- (continued)

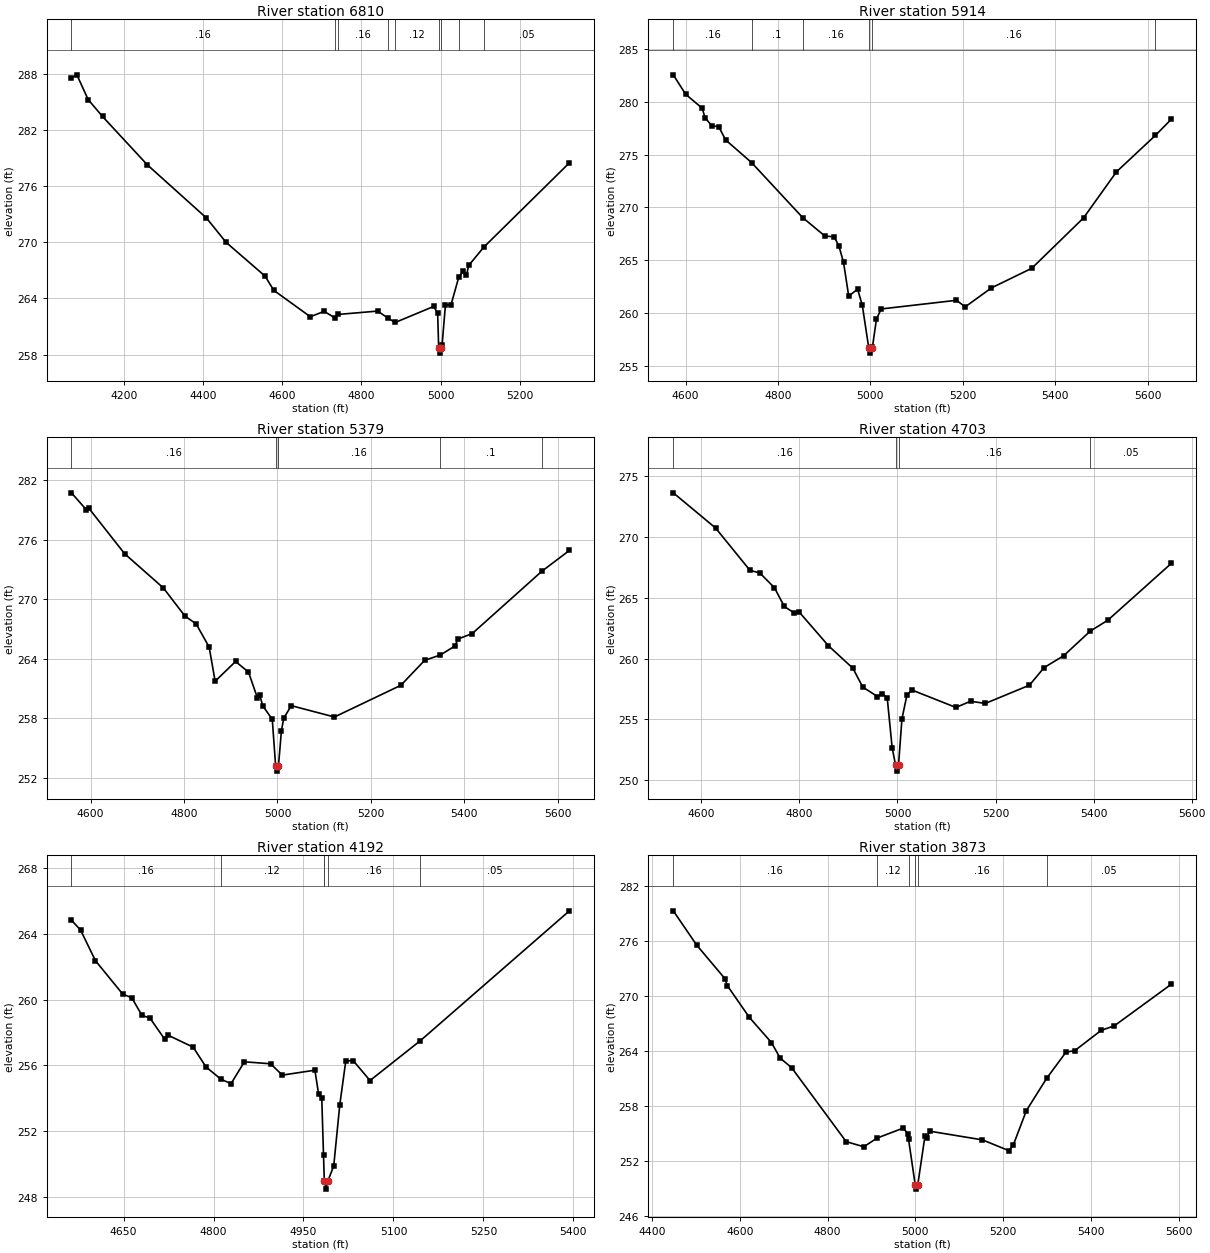
Type RM Length L Ch R = 1 ,6810    ,896,896,896
BEGIN DESCRIPTION:
UNT0468 IN WICK 13.0
END DESCRIPTION:
XS GIS Cut Line= 3
       3613242.1     10274691.65      3612542.11     10275291.64
      3612242.07     10275441.66
#Sta/Elev= 30
  4067.7  287.59  4081.4  287.94  4109.9  285.29  4146.2  283.48  4259.2  278.31
  4408.5  272.62  4457.9  270.02  4556.7  266.39  4578.6  264.87  4670.8  262.05
  4705.9  262.62  4733.5  261.91  4740.8  262.29  4840.9  262.65    4868  261.87
  4885.1  261.43  4982.5  263.15  4992.4  262.41    4995  258.65  4997.8  258.15
    5001  258.65  5003.6  259.02    5012  263.29    5026  263.31  5045.8  266.29
  5056.7  266.93  5065.1  266.47  5070.7  267.53  5108.8  269.49  5325.1  278.52
#Mann= 9 ,-1 , 0
  4067.7     .16       0  4733.5      .1       0  4740.8     .16       0
    4868     .05       0  4885.1     .12       0    4995     .07       0
    5001     .12       0  5045.8     .16       0  5108.8     .05       0
Bank Sta=4995,5001
XS Rating Curve= 0 ,0
Exp/Cntr=0.3,0.1

Type RM Length L Ch R = 1 ,5914    ,535,535,535
BEGIN DESCRIPTION:
UNT0468 IN WICK 12.0
END DESCRIPTION:
XS GIS Cut Line= 3
      3613088.69     10274641.11      3612906.36     10274767.01
      3612065.71     10274931.67
#Sta/Elev= 30
  4573.2  282.55    4600  280.71  4635.8  279.39    4642  278.48  4656.8  277.73
  4671.6  277.64  4686.5  276.39  4742.6  274.25  4853.3  269.04  4901.5  267.29
  4921.4  267.22  4931.6  266.38  4941.8  264.81    4953  261.61  4972.3  262.26
  4982.5  260.73  4996.4  256.71  4999.1  256.21  5002.4  256.71  5004.5  256.81
  5013.1  259.43  5023.3  260.39  5186.3  261.21  5205.3  260.59  5261.9  262.38
  5349.4  264.24  5461.5  269.01  5532.8  273.37  5617.1  276.82  5651.4  278.34
#Mann= 6 ,-1 , 0
  4573.2     .16       0  4742.6      .1       0  4853.3     .16       0
  4996.4     .07       0  5002.4     .16       0  5617.1     .05       0
Bank Sta=4996.4,5002.4
XS Rating Curve= 0 ,0
Exp/Cntr=0.3,0.1

Type RM Length L Ch R = 1 ,5379    ,676,676,676
BEGIN DESCRIPTION:
UNT0468 IN WICK 10.0
END DESCRIPTION:
XS GIS Cut Line= 2
      3613053.96     10274419.78      3612007.97     10274623.77
#Sta/Elev= 30
  4559.1   280.7  4590.7  279.01  4595.8  279.18  4673.1  274.56  4755.7  271.13
  4802.2  268.28  4825.9  267.51  4853.8  265.17  4866.6  261.73  4910.4  263.72
    4938  262.65  4956.9  260.08    4962  260.34  4968.5  259.26  4988.9  257.89
  4996.1  253.18  4998.8  252.68  5002.1  253.18  5008.5  256.77  5013.6  258.03
  5029.7  259.27  5121.9  258.13    5264  261.32  5314.9  263.83  5348.4  264.37
  5379.9  265.28  5386.3  265.98  5416.8  266.53  5566.2  272.82  5624.8   274.9
#Mann= 5 ,-1 , 0
  4559.1     .16       0  4996.1     .07       0  5002.1     .16       0
  5348.4      .1       0  5566.2     .05       0
Bank Sta=4996.1,5002.1
XS Rating Curve= 0 ,0
Exp/Cntr=0.3,0.1

Type RM Length L Ch R = 1 ,4703    ,511,511,511
BEGIN DESCRIPTION:
UNT0468 IN WICK 9.0
END DESCRIPTION:
XS GIS Cut Line= 2
      3612958.47     10273972.74      3611942.78     10273977.08
#Sta/Elev= 30
  4542.7  273.65  4629.1  270.75  4699.1  267.27  4719.1  267.06  4749.1  265.84
  4769.1   264.3  4789.1  263.77  4799.1  263.86  4859.1  261.07  4909.1  259.21
  4929.1  257.67  4959.1  256.89  4969.1  257.13  4979.1  256.76  4989.1  252.68
  4996.1  251.25  4998.8  250.75  5002.1  251.25  5009.1  255.05  5019.1  256.98
  5029.1  257.43  5119.1  255.99  5149.1   256.5  5179.1  256.32  5269.1  257.82
  5299.1  259.27  5339.1  260.25  5393.1  262.27  5429.1  263.17  5558.4  267.84
#Mann= 4 ,-1 , 0
  4542.7     .16       0  4996.1     .07       0  5002.1     .16       0
  5393.1     .05       0
Bank Sta=4996.1,5002.1
XS Rating Curve= 0 ,0
Exp/Cntr=0.3,0.1

Type RM Length L Ch R = 1 ,4192    ,319,319,319
BEGIN DESCRIPTION:
UNT0468 IN WICK 8.0
END DESCRIPTION:
XS GIS Cut Line= 3
      3612742.14     10273491.63      3612342.11     10273641.64
      3611942.15     10273691.64
#Sta/Elev= 30
  4563.1  264.84  4578.3  264.24  4603.2  262.37  4648.6  260.34  4663.7  260.12
  4680.6  259.05    4694  258.88  4718.9  257.58  4724.2  257.84  4766.1  257.11
  4787.4  255.91  4812.3  255.16  4829.2  254.89  4851.5  256.22  4895.1   256.1
  4914.7  255.41    4969  255.71  4975.2  254.26  4980.5  253.99  4983.4  250.52
  4984.7  248.97  4987.4  248.47  4990.7  248.97  5000.4  249.88  5010.5   253.6
  5020.6  256.29  5033.2  256.28  5060.9  255.08    5145  257.51  5393.4  265.41
#Mann= 6 ,-1 , 0
  4563.1     .16       0  4812.3     .12       0  4983.4     .16       0
  4984.7     .07       0  4990.7     .16       0    5145     .05       0
Bank Sta=4984.7,4990.7
XS Rating Curve= 0 ,0
Exp/Cntr=0.3,0.1

Type RM Length L Ch R = 1 ,3873    ,927,927,927
BEGIN DESCRIPTION:
UNT0468 IN WICK 7.0
END DESCRIPTION:
XS GIS Cut Line= 2
      3612945.38     10273339.06      3611812.58     10273412.84
#Sta/Elev= 30
  4448.3  279.33  4501.7  275.59  4565.9  271.94  4571.8  271.15  4621.9   267.7
    4672  264.97  4692.1  263.26    4718  262.23  4842.4  254.16  4882.5   253.6
    4913  254.55  4972.7  255.64  4982.7  255.03  4984.6  254.42  4999.7  249.48
  5002.5  248.98  5005.7  249.48  5022.1  254.78  5027.2  254.61  5032.8   255.3
  5153.1  254.35  5213.2  253.18  5223.2  253.77  5253.3  257.55  5299.3  261.05
  5343.5  263.92  5363.5  264.08  5423.6  266.29  5453.7  266.79  5583.5  271.32
#Mann= 6 ,-1 , 0
  4448.3     .16       0    4913     .12       0  4984.6     .16       0
  4999.7     .07       0  5005.7     .16       0  5299.3     .05       0
Bank Sta=4999.7,5005.7
XS Rating Curve= 0 ,0
Exp/Cntr=0.3,0.1

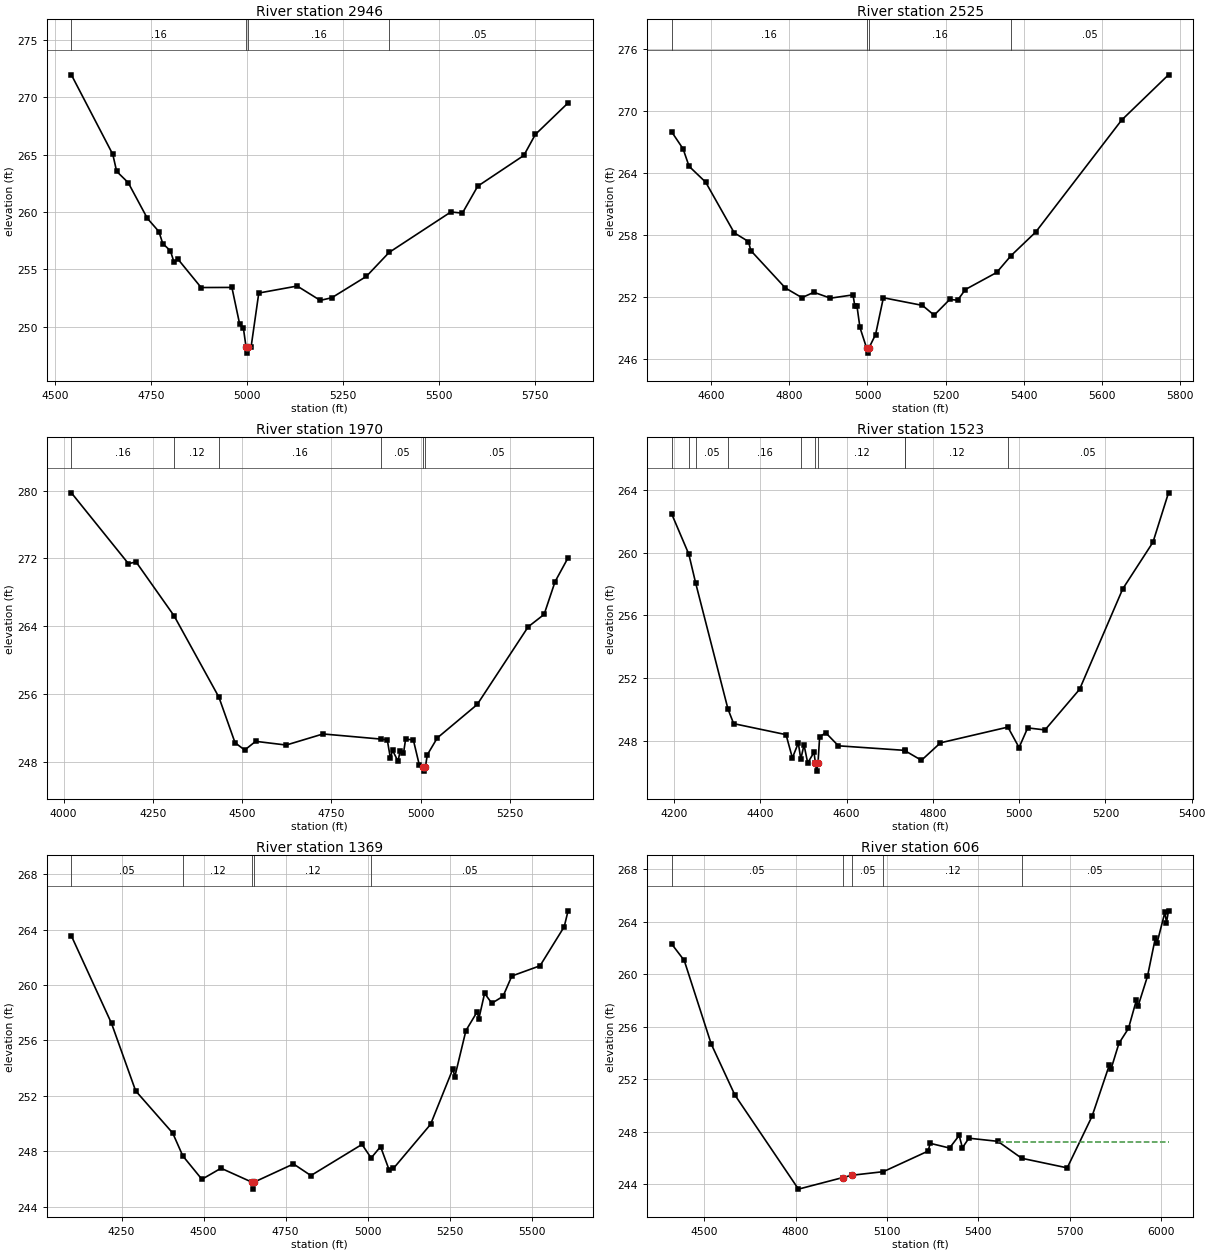
Type RM Length L Ch R = 1 ,2946    ,421,421,421
BEGIN DESCRIPTION:
UNT0468 IN WICK 6.0
END DESCRIPTION:
XS GIS Cut Line= 3
      3612849.94     10272939.75      3611825.63     10272965.79
      3611556.87     10272965.79
#Sta/Elev= 30
  4542.1  271.95    4650  265.01    4660  263.53    4690  262.55    4740  259.43
    4770  258.28    4780  257.24    4800   256.6  4809.1  255.64    4820  255.86
    4880   253.4  4960.1  253.41  4980.1  250.24  4990.1  249.84  4997.1  248.18
  4999.8  247.68  5003.1  248.18  5010.1  248.22  5030.1  252.92  5130.1  253.53
  5190.1  252.28  5220.2  252.51  5310.2  254.37  5369.4  256.46  5530.3  259.99
  5560.3  259.89  5600.3  262.24  5720.3  264.92  5750.3  266.75  5835.5   269.5
#Mann= 4 ,-1 , 0
  4542.1     .16       0  4997.1     .07       0  5003.1     .16       0
  5369.4     .05       0
Bank Sta=4997.1,5003.1
XS Rating Curve= 0 ,0
Exp/Cntr=0.3,0.1

Type RM Length L Ch R = 1 ,2525    ,555,555,555
BEGIN DESCRIPTION:
UNT0468 IN WICK 5.0
END DESCRIPTION:
XS GIS Cut Line= 3
      3612792.09     10272891.63      3612392.11     10272641.64
      3611592.08     10272641.64
#Sta/Elev= 30
    4499  267.98  4527.9  266.35  4543.2  264.66  4585.7  263.12  4658.8  258.21
  4695.3  257.36  4701.2  256.49  4789.7  252.86  4832.1  251.92  4862.8  252.44
  4905.2  251.87    4963  252.19  4967.7  251.07  4973.2  251.07  4980.7  249.03
  4997.7  247.04  5000.4  246.54  5003.7  247.04  5020.7  248.34  5040.7  251.91
  5140.7  251.17  5170.7  250.22  5210.7  251.75  5230.7  251.67  5250.7  252.71
  5330.7  254.36  5367.7     256  5430.7  258.28  5650.7  269.14  5770.7  273.53
#Mann= 4 ,-1 , 0
    4499     .16       0  4997.7     .07       0  5003.7     .16       0
  5367.7     .05       0
Bank Sta=4997.7,5003.7
XS Rating Curve= 0 ,0
Exp/Cntr=0.3,0.1

Type RM Length L Ch R = 1 ,1970    ,447,447,447
BEGIN DESCRIPTION:
UNT0468 IN WICK 4.0
END DESCRIPTION:
XS GIS Cut Line= 3
      3613092.15     10272691.67      3612292.11     10272191.64
      3611892.07     10271991.62
#Sta/Elev= 30
  4021.8  279.74  4181.6  271.37  4202.9  271.58  4309.4  265.21  4434.9   255.6
    4480  250.23  4507.1  249.36  4537.8  250.39  4623.3  249.95  4726.4  251.26
  4889.6  250.65  4906.3  250.56  4915.1  248.38    4921  249.34  4936.4  248.02
  4942.3  249.27  4951.7  248.99  4957.6  250.63  4979.2  250.57    4996  247.59
    5007  247.37  5009.7  246.87    5013  247.37  5018.4   248.8  5046.3  250.79
  5158.1  254.74  5300.7  263.91  5345.4  265.38  5376.1  269.25  5412.5  272.07
#Mann= 6 ,-1 , 0
  4021.8     .16       0  4309.4     .12       0  4434.9     .16       0
  4889.6     .05       0    5007     .03       0    5013     .05       0
Bank Sta=5007,5013
XS Rating Curve= 0 ,0
Exp/Cntr=0.3,0.1

Type RM Length L Ch R = 1 ,1523    ,154,154,154
BEGIN DESCRIPTION:
UNT0468 IN WICK 3.0
END DESCRIPTION:
XS GIS Cut Line= 3
      3612979.62     10272223.34      3612351.89     10271768.59
      3611976.14      10271749.1
#Sta/Elev= 30
  4194.9  262.44  4234.3   259.9  4250.4  258.04  4325.2  250.04  4338.3  249.12
  4459.7  248.42  4474.4  246.94  4488.2  247.89  4493.9  246.86  4501.4  247.77
  4509.9  246.62  4524.6   247.3  4527.8   246.6  4530.5   246.1  4533.8   246.6
  4537.6  248.28  4551.7  248.54  4581.1  247.71  4735.1  247.42  4736.6  247.38
  4773.6  246.79  4817.7   247.9    4974   248.9  4999.9   247.6  5019.9  248.85
    5060  248.72  5140.1   251.3  5240.2  257.69  5310.3  260.66  5346.3   263.8
#Mann= 10 ,-1 , 0
  4194.9     .16       0  4234.3     .12       0  4250.4     .05       0
  4325.2     .16       0  4493.9     .12       0  4527.8     .03       0
  4533.8     .12       0  4735.1     .16       0  4736.6     .12       0
    4974     .05       0
Bank Sta=4527.8,4533.8
XS Rating Curve= 0 ,0
Exp/Cntr=0.3,0.1

Type RM Length L Ch R = 1 ,1369    ,763,763,763
BEGIN DESCRIPTION:
Mapping XS 743b9822
END DESCRIPTION:
XS GIS Cut Line= 2
      3613195.31     10271859.37      3611737.03     10271453.14
#Sta/Elev= 30
  4097.2  263.56  4219.5  257.24  4293.1  252.36  4406.1  249.31  4436.8  247.66
    4495  245.97  4553.3  246.77  4647.7  245.76  4650.5  245.26  4653.7  245.76
  4774.1  247.08  4827.2  246.24  4982.9  248.49  5010.8  247.51  5039.5  248.33
  5065.9  246.63  5078.9  246.76  5191.9  249.94  5260.3  253.97  5265.5  253.35
  5299.7  256.72  5333.9  258.07  5339.1  257.57  5356.6  259.41  5378.5  258.69
  5412.7  259.19  5439.6  260.66  5525.6   261.4  5599.2  264.22    5611  265.37
#Mann= 5 ,-1 , 0
  4097.2     .05       0  4436.8     .12       0  4647.7     .07       0
  4653.7     .12       0  5010.8     .05       0
Bank Sta=4647.7,4653.7
XS Rating Curve= 0 ,0
Exp/Cntr=0.3,0.1

Type RM Length L Ch R = 1 ,606     ,356,356,356
BEGIN DESCRIPTION:
Mapping XS f60c8830
END DESCRIPTION:
XS GIS Cut Line= 4
      3613164.06     10271760.36        3613046.     10271468.69
      3612094.61     10271138.82      3611802.92     10271239.53
#Sta/Elev= 30
  4393.8   262.3  4434.6  261.06  4523.1   254.7  4600.8  250.81  4809.5  243.64
  4954.8  244.52    4986   244.7  5088.1  244.97  5235.1  246.54  5241.8  247.13
  5305.3  246.77    5337  247.73  5347.6  246.79  5368.8  247.52    5464  247.28
  5542.3  245.99  5691.6  245.26  5773.1  249.19  5830.2  253.12  5835.5   252.8
  5861.4  254.75  5892.6  255.88  5918.5  258.03  5923.8  257.56    5955  259.85
  5980.9  262.78  5986.2  262.37  6012.1  264.73  6017.4  263.95    6024  264.84
#Mann= 5 ,-1 , 0
  4393.8     .05       0  4954.8     .03       0    4986     .05       0
  5088.1     .12       0  5542.3     .05       0
#XS Ineff= 2 , 0
                         5465.91          247.26
Permanent Ineff=
       F       F
Bank Sta=4954.8,4986
XS Rating Curve= 0 ,0
Exp/Cntr=0.3,0.1

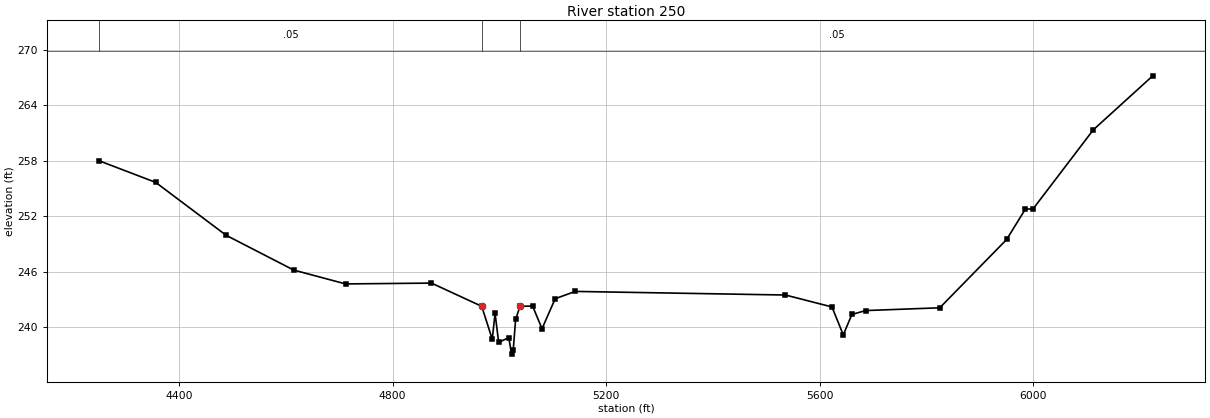
Type RM Length L Ch R = 1 ,250     ,0,0,0
BEGIN DESCRIPTION:
UNT0468 IN WICK 1.0
END DESCRIPTION:
XS GIS Cut Line= 4
      3613271.69     10271583.26       3613132.8     10271164.93
      3612063.36      10270793.4      3611800.42     10271096.51
#Sta/Elev= 30
  4250.2  257.98    4356  255.65    4488  249.93  4614.6  246.17  4711.9  244.67
  4872.8  244.76    4967  242.25  4986.7  238.69    4992  241.49  4998.7  238.35
  5017.8  238.87  5022.8  237.08  5026.1  237.58  5030.5  240.83 5038.69  242.24
  5062.2  242.29    5080  239.83  5104.6  243.07  5142.2  243.86  5536.2  243.47
  5623.3  242.18  5644.5  239.16  5660.6  241.37  5686.5  241.79  5825.3  242.09
  5950.7  249.48  5985.8  252.77    6000  252.77    6113  261.33  6224.4  267.17
#Mann= 3 , 0 , 0
  4250.2     .05       0    4967     .03       0 5038.69     .05       0
Bank Sta=4967,5038.69
XS Rating Curve= 0 ,0
Exp/Cntr=0.3,0.1

Chan Stop Cuts=-1
Use User Specified Reach Order=0
Composite Channel Slope=5