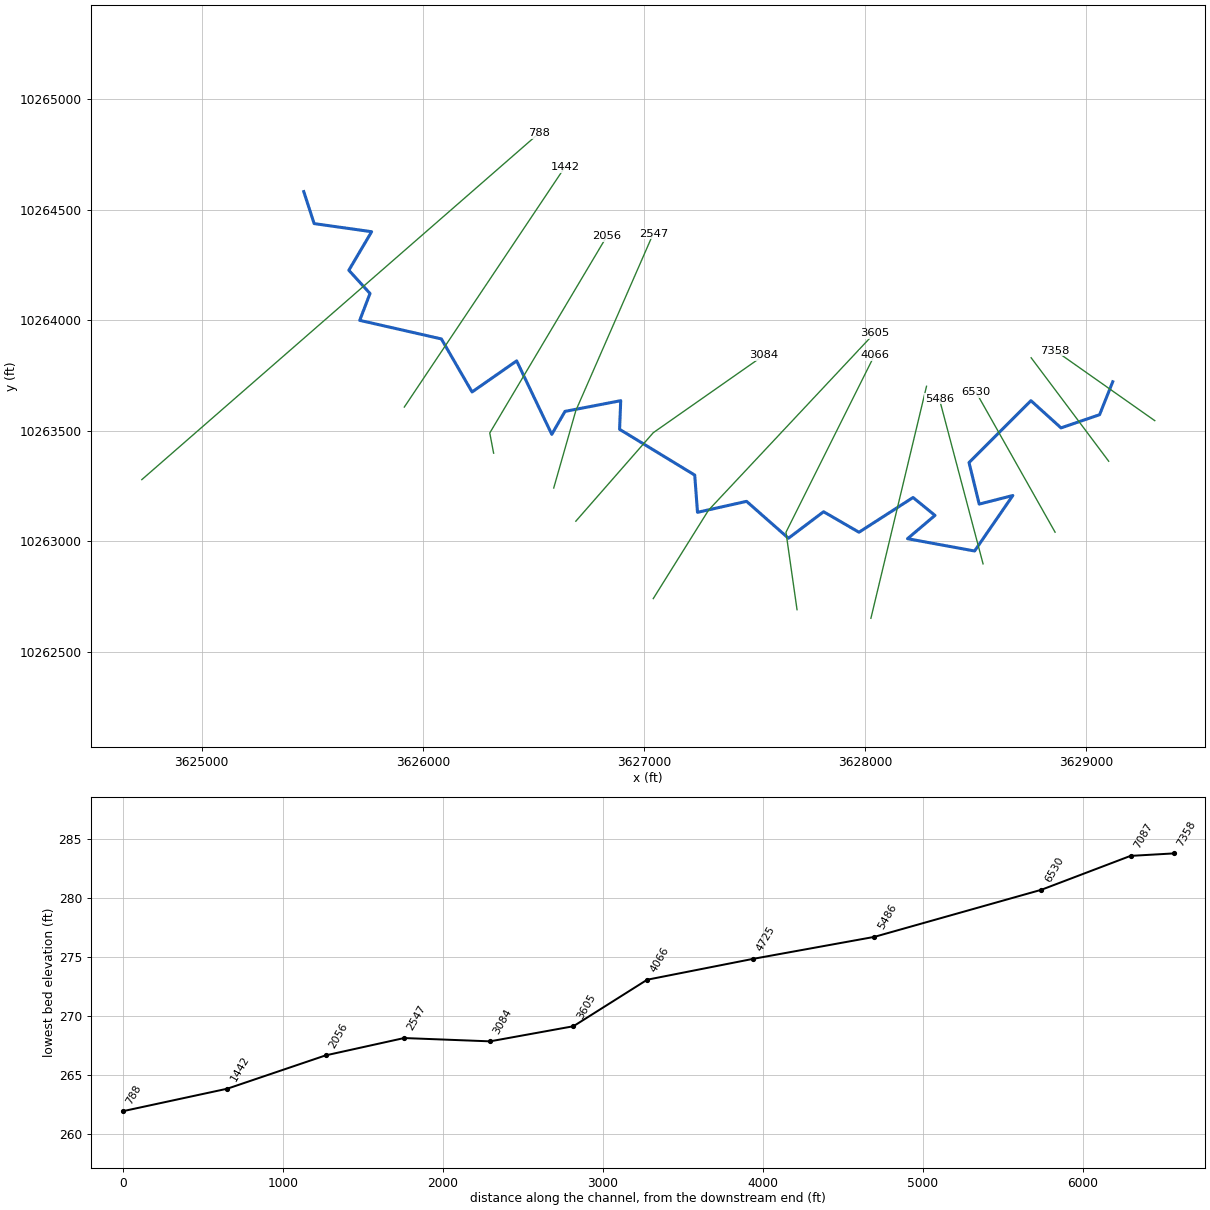
--- UNT0470 IN WICK.prj (project) ---

Proj Title=UNT0470 IN WICK Base Level Engineering
Current Plan=p01
Default Exp/Contr=0.3,0.1
English Units
Geom File=g01
Flow File=f01
Plan File=p01
Y Axis Title=Elevation
X Axis Title(PF)=Main Channel Distance
X Axis Title(XS)=Station
BEGIN DESCRIPTION:
UNT0470 IN WICK
END DESCRIPTION:
DSS Export Rating Curves= 0
DSS Export Rating Curve Sorted= 0
DSS Export Volume Flow Curves= 0
DXF OffsetX= 0
DXF OffsetY= 0
DXF ScaleX= 1
DXF ScaleY= 10

--- UNT0470 IN WICK.p01 (plan) ---

Plan Title=Multiple Run
Short Identifier=Multiple
Geom File=g01
Flow File=f01
Subcritical Flow
K Sum by GR= 0
Std Step Tol= 0.01
Critical Tol= 0.01
Num of Std Step Trials= 20
Max Error Tol= 0.3
Flow Tol Ratio= 0.001
Split Flow NTrial= 30
Split Flow Tol= 0.02
Split Flow Ratio= 0.02
Log Output Level= 0
Friction Slope Method= 1
Unsteady Friction Slope Method= 2
Unsteady Bridges Friction Slope Method= 1
Parabolic Critical Depth
Global Vel Dist=  1 , 1 , 1
Global Log Level= 0
CheckData=True
Encroach Param= -1, 0, 0, 0
BEGIN DESCRIPTION:
Multiple Run
END DESCRIPTION:

--- UNT0470 IN WICK.f01 (steady flow) ---

Flow Title=Multiple
Number of Profiles=7
Profile Names=10-year,25-year,50-year,1pct_min,100-year,1pct_plu,500-year
River Rch & RM= UNT0470 IN WICK,Reach-1,7358
     374     484     571     494     668     903     914
River Rch & RM= UNT0470 IN WICK,Reach-1,4066
     610     813     977     860    1163    1572    1649
River Rch & RM= UNT0470 IN WICK,Reach-1,788
     685     921    1112     983    1329    1797    1903
Boundary for River Rch & Prof#=UNT0470 IN WICK,Reach-1,1
Up Type=0
Dn Type=3
Dn Slope=0.005
Boundary for River Rch & Prof#=UNT0470 IN WICK,Reach-1,2
Up Type=0
Dn Type=3
Dn Slope=0.005
Boundary for River Rch & Prof#=UNT0470 IN WICK,Reach-1,3
Up Type=0
Dn Type=3
Dn Slope=0.005
Boundary for River Rch & Prof#=UNT0470 IN WICK,Reach-1,4
Up Type=0
Dn Type=3
Dn Slope=0.005
Boundary for River Rch & Prof#=UNT0470 IN WICK,Reach-1,5
Up Type=0
Dn Type=3
Dn Slope=0.005
Boundary for River Rch & Prof#=UNT0470 IN WICK,Reach-1,6
Up Type=0
Dn Type=3
Dn Slope=0.005
Boundary for River Rch & Prof#=UNT0470 IN WICK,Reach-1,7
Up Type=0
Dn Type=3
Dn Slope=0.005

--- UNT0470 IN WICK.g01 (geometry) ---

Geom Title=Existing Conditions
Program Version=4.10

River Reach=UNT0470 IN WICK ,Reach-1
Reach XY= 30
      3629119.41       10263722.       3629059.9     10263573.03
      3628885.51     10263513.43      3628749.54     10263636.49
      3628469.57     10263356.86      3628515.69      10263168.9
      3628667.52     10263207.68      3628494.83     10262956.84
      3628191.46     10263012.52      3628315.79     10263117.84
      3628216.53      10263198.7      3627972.11     10263041.64
      3627812.05     10263134.43      3627653.27      10263014.5
      3627463.92     10263181.32      3627242.13     10263131.74
      3627229.56       10263300.      3626889.88     10263506.99
      3626894.99     10263636.39      3626643.13       10263588.
      3626583.27     10263484.16      3626424.54      10263816.4
      3626222.99     10263675.81      3626084.28     10263915.61
      3625715.07      10263999.6      3625761.65     10264120.91
       3625665.9     10264226.05      3625768.93     10264400.25
      3625509.05     10264436.97      3625462.11     10264581.64

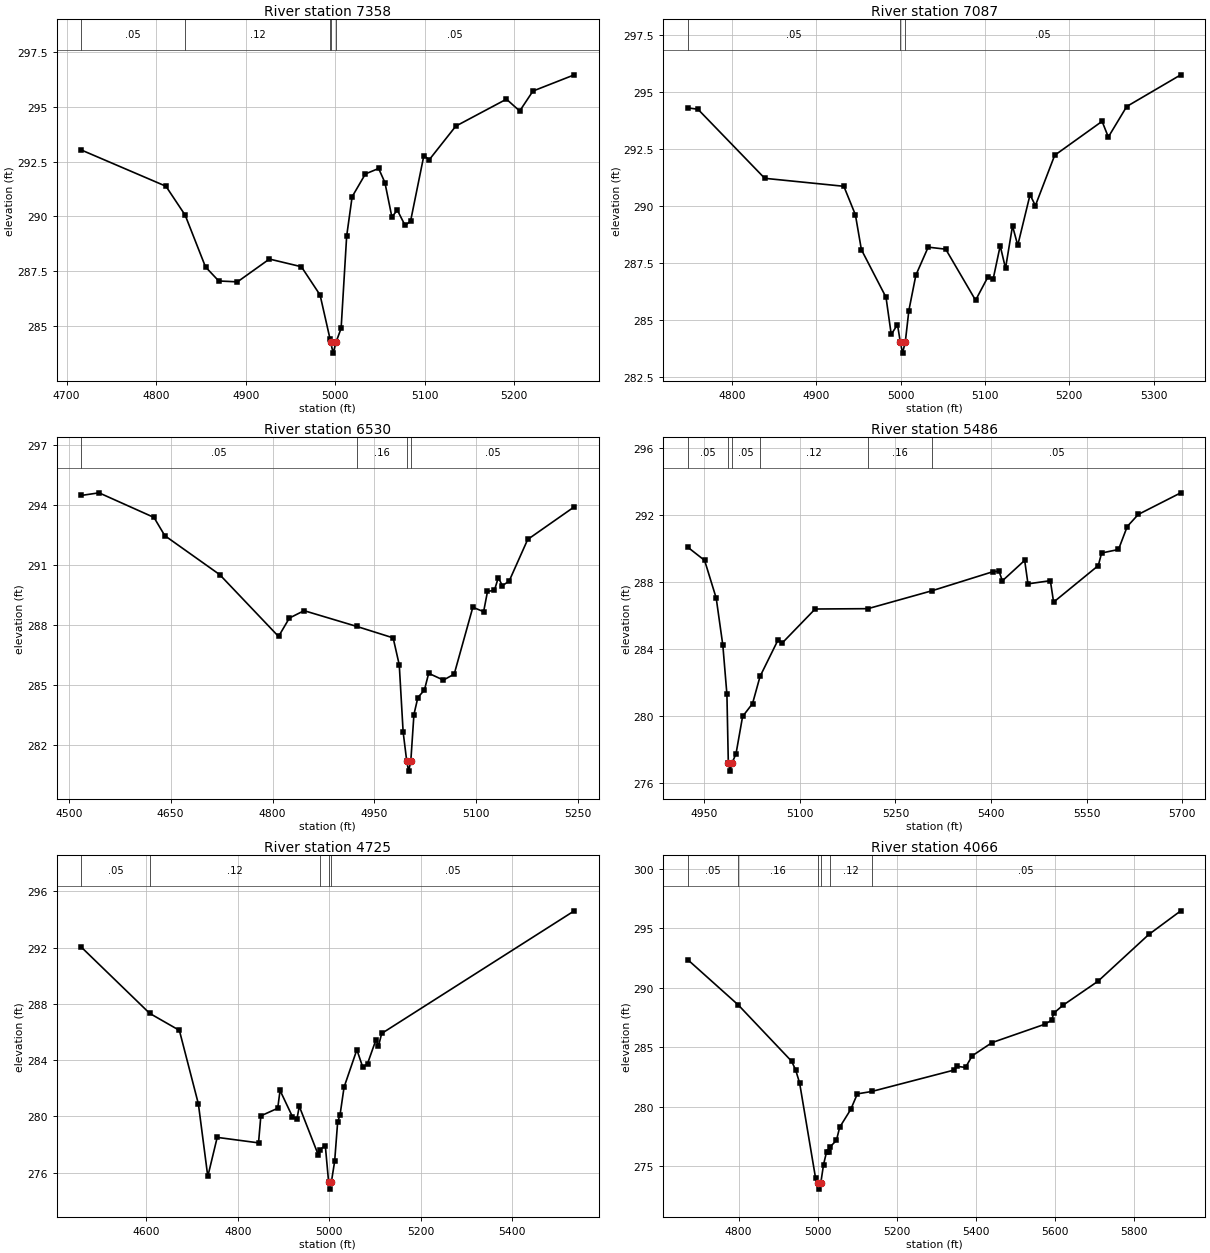
Type RM Length L Ch R = 1 ,7358    ,271,271,271
BEGIN DESCRIPTION:
UNT0470 IN WICK 10.0
END DESCRIPTION:
XS GIS Cut Line= 2
      3629309.33     10263546.12      3628859.03     10263862.96
#Sta/Elev= 30
  4716.5  293.03  4810.9  291.38  4832.4  290.06  4855.1   287.7  4869.9  287.06
  4890.8  287.02  4926.5  288.06  4962.2  287.71  4983.1  286.42  4994.3   284.4
  4994.9  284.27  4997.7  283.77  5000.9  284.27  5006.6   284.9  5012.8  289.11
  5018.9   290.9  5033.7  291.94  5048.5  292.19  5055.5  291.55  5063.3  289.98
  5069.4  290.29  5078.1  289.59  5084.2  289.79    5099  292.77  5105.1  292.59
  5134.7  294.12  5191.3  295.35  5206.1  294.81  5220.9  295.72  5267.1  296.46
#Mann= 5 ,-1 , 0
  4716.5     .05       0  4832.4     .12       0  4994.3     .05       0
  4994.9    .035       0  5000.9     .05       0
Bank Sta=4994.9,5000.9
XS Rating Curve= 0 ,0
Exp/Cntr=0.3,0.1

Type RM Length L Ch R = 1 ,7087    ,557,557,557
BEGIN DESCRIPTION:
Mapping XS 4a30b206
END DESCRIPTION:
XS GIS Cut Line= 2
        3629101.     10263362.75      3628750.53      10263830.4
#Sta/Elev= 30
  4747.8  294.32  4759.7  294.26  4838.9  291.23  4932.7  290.88  4946.4  289.63
  4953.5   288.1  4982.7  286.01  4988.9  284.38  4996.3  284.81  4999.6  284.06
  5002.3  283.56  5005.6  284.06  5009.8  285.43  5018.1  286.98  5032.7  288.21
  5053.5  288.12  5088.9  285.88  5103.5   286.9  5109.8  286.82  5118.1  288.27
  5124.4  287.28  5132.7  289.14  5138.9  288.29  5153.5  290.51  5159.8  290.03
  5182.7  292.24  5238.9  293.73  5246.3  293.04  5268.1  294.38  5332.2  295.77
#Mann= 3 ,-1 , 0
  4747.8     .05       0  4999.6     .03       0  5005.6     .05       0
Bank Sta=4999.6,5005.6
XS Rating Curve= 0 ,0
Exp/Cntr=0.3,0.1

Type RM Length L Ch R = 1 ,6530    ,1044,1044,1044
BEGIN DESCRIPTION:
Mapping XS c174744c
END DESCRIPTION:
XS GIS Cut Line= 2
      3628858.61     10263041.94      3628502.02     10263673.88
#Sta/Elev= 30
  4518.7  294.47  4544.6   294.6  4625.5  293.37  4641.4  292.46  4722.3  290.51
  4808.9  287.42  4824.8  288.34  4846.5  288.71  4924.3  287.92  4977.6  287.35
  4986.6     286  4992.3  282.65  4997.6  281.19  5000.4  280.69  5003.6  281.19
  5008.2  283.52    5014  284.37  5023.6  284.74  5029.9  285.58  5051.6  285.24
  5067.5  285.54  5094.9  288.88  5110.8  288.66  5116.5  289.67  5126.7  289.73
  5132.4  290.36  5138.4  289.96  5148.4  290.19  5175.7  292.27  5244.3   293.9
#Mann= 4 ,-1 , 0
  4518.7     .05       0  4924.3     .16       0  4997.6     .07       0
  5003.6     .05       0
Bank Sta=4997.6,5003.6
XS Rating Curve= 0 ,0
Exp/Cntr=0.3,0.1

Type RM Length L Ch R = 1 ,5486    ,761,761,761
BEGIN DESCRIPTION:
Mapping XS 0bfd6349
END DESCRIPTION:
XS GIS Cut Line= 2
      3628533.09     10262898.69      3628335.16     10263646.13
#Sta/Elev= 30
  4924.4  290.05  4950.6  289.27  4968.8  287.02  4979.2  284.21  4985.6  281.28
  4987.8   277.2  4990.5   276.7  4993.8   277.2  4999.9  277.74  5010.2  279.96
  5025.8  280.73  5037.6  282.35    5066  284.54  5072.3  284.34    5124  286.37
  5206.8  286.39  5307.4  287.46  5403.3   288.6  5412.5  288.62  5417.7  288.05
  5452.7  289.27  5457.9  287.87    5493  288.06  5498.1  286.78  5568.2  288.96
  5573.4  289.71  5599.9  289.92  5613.6  291.29  5630.9  292.01  5697.6   293.3
#Mann= 6 ,-1 , 0
  4924.4     .05       0  4987.8     .03       0  4993.8     .05       0
  5037.6     .12       0  5206.8     .16       0  5307.4     .05       0
Bank Sta=4987.8,4993.8
XS Rating Curve= 0 ,0
Exp/Cntr=0.3,0.1

Type RM Length L Ch R = 1 ,4725    ,659,659,659
BEGIN DESCRIPTION:
UNT0470 IN WICK 9.0
END DESCRIPTION:
XS GIS Cut Line= 2
       3628026.1     10262652.76      3628277.46     10263701.56
#Sta/Elev= 30
  4457.7  292.03    4607  287.33    4672  286.12  4713.6  280.89  4734.2  275.73
  4754.8  278.51  4845.2  278.12  4850.3  280.04  4887.2  280.58  4892.3  281.85
  4919.3  279.99  4929.2  279.81  4934.4  280.72  4976.4  277.23  4978.7  277.61
  4991.3  277.93  4998.6  275.33  5001.3  274.83  5004.6  275.33  5011.8  276.81
  5018.4  279.62  5023.5  280.09  5032.4  282.08  5060.4  284.74  5073.5  283.48
  5083.8  283.76  5102.4  285.47  5107.6  284.99  5114.7   285.9  5536.2  294.62
#Mann= 5 ,-1 , 0
  4457.7     .05       0    4607     .12       0  4978.7     .05       0
  4998.6     .03       0  5004.6     .05       0
Bank Sta=4998.6,5004.6
XS Rating Curve= 0 ,0
Exp/Cntr=0.3,0.1

Type RM Length L Ch R = 1 ,4066    ,461,461,461
BEGIN DESCRIPTION:
UNT0470 IN WICK 8.0
END DESCRIPTION:
XS GIS Cut Line= 3
      3627692.11      10262691.6      3627642.11     10263041.64
       3628042.1     10263841.62
#Sta/Elev= 30
  4671.6  292.35    4799  288.56  4934.3  283.82  4944.4  283.09  4954.5  281.99
  4994.9  273.99    5002  273.57  5004.7  273.07    5008  273.57  5015.1  275.14
  5022.7   276.2    5028   276.2  5032.3  276.65  5047.6  277.16  5055.9  278.27
  5083.9  279.77  5100.7  281.08    5137  281.28  5346.6  283.09  5352.2   283.4
  5374.6   283.3  5391.4  284.28  5441.7  285.39  5575.8  286.94  5592.6  287.28
  5598.2  287.87  5620.5  288.51    5710  290.55  5838.6  294.48  5919.6  296.47
#Mann= 6 ,-1 , 0
  4671.6     .05       0    4799     .16       0    5002     .07       0
    5008     .16       0  5032.3     .12       0    5137     .05       0
Bank Sta=5002,5008
XS Rating Curve= 0 ,0
Exp/Cntr=0.3,0.1

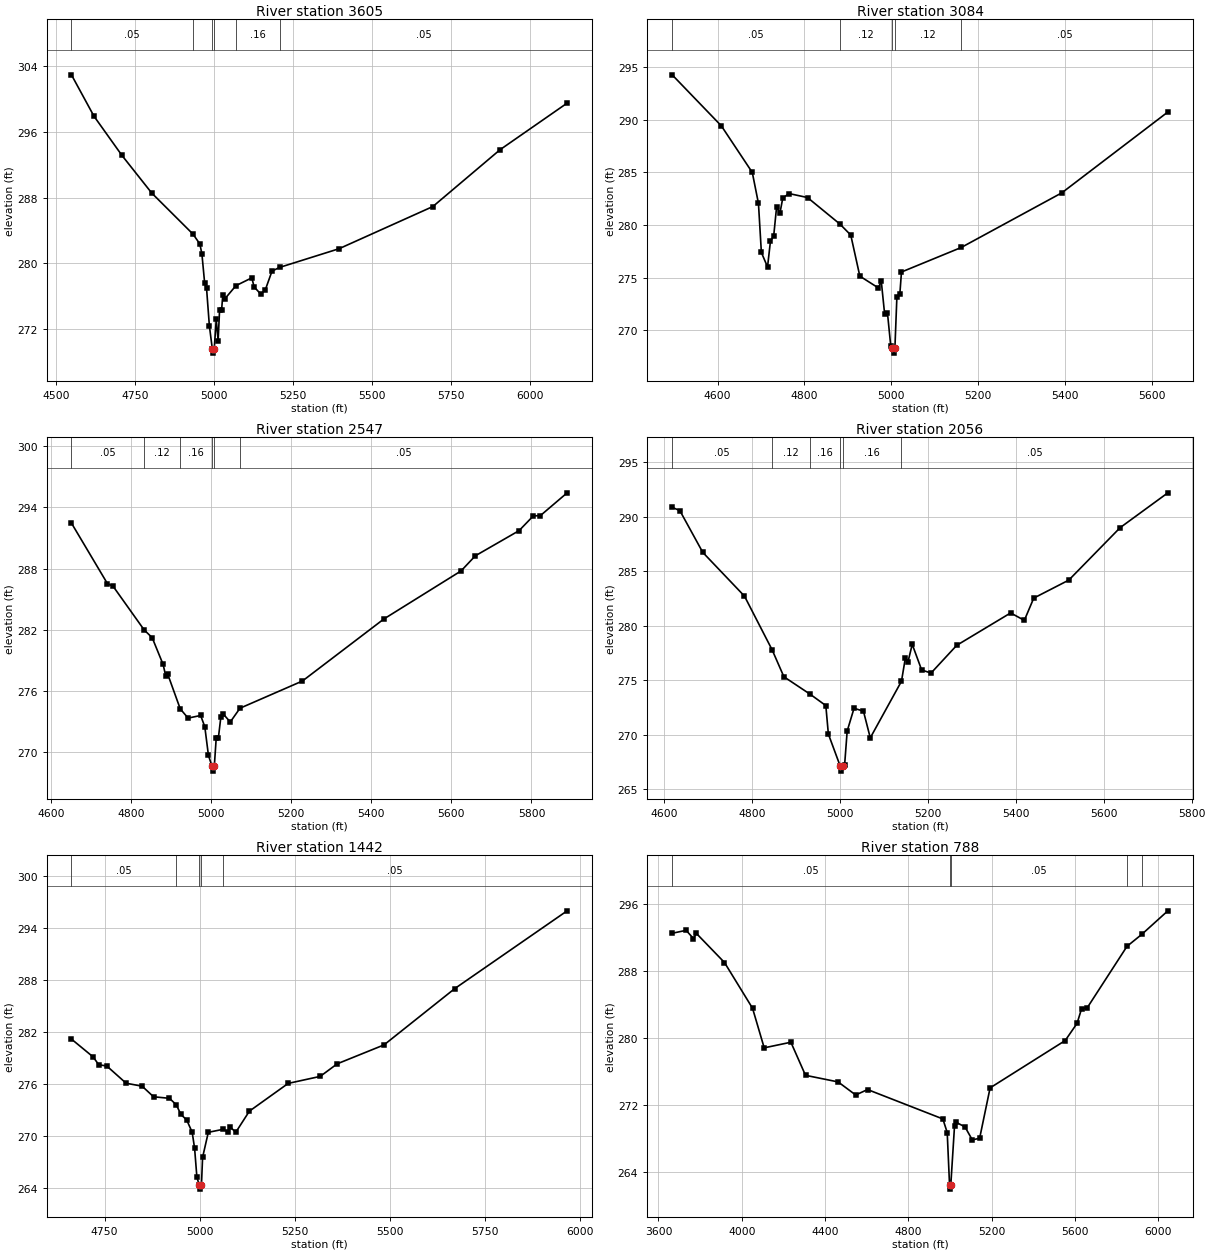
Type RM Length L Ch R = 1 ,3605    ,521,521,521
BEGIN DESCRIPTION:
UNT0470 IN WICK 7.0
END DESCRIPTION:
XS GIS Cut Line= 3
      3627042.13     10262741.68      3627292.11     10263141.64
      3628042.08     10263941.62
#Sta/Elev= 30
  4548.5  302.88  4619.8  297.86  4708.2  293.11  4802.6  288.54  4933.3  283.55
  4954.7  282.37  4961.2  281.17    4970  277.58  4975.9     277  4984.8  272.46
  4994.2  269.63  4996.9  269.13  5000.2  269.63  5006.6  273.24  5012.5  270.64
  5017.2   274.4  5023.6   274.4  5027.2  276.13  5034.1  275.73  5068.8  277.31
  5119.1  278.26  5126.4  277.16  5147.4  276.29  5161.6  276.78    5183  279.08
  5207.4  279.53    5395  281.79    5692  286.91  5904.5   293.8  6116.7  299.45
#Mann= 6 ,-1 , 0
  4548.5     .05       0  4933.3     .12       0  4994.2     .07       0
  5000.2     .12       0  5068.8     .16       0  5207.4     .05       0
Bank Sta=4994.2,5000.2
XS Rating Curve= 0 ,0
Exp/Cntr=0.3,0.1

Type RM Length L Ch R = 1 ,3084    ,537,537,537
BEGIN DESCRIPTION:
UNT0470 IN WICK 6.0
END DESCRIPTION:
XS GIS Cut Line= 3
      3626692.11     10263091.65      3627042.11     10263491.64
      3627542.09     10263841.63
#Sta/Elev= 30
  4495.4  294.27  4608.8  289.42    4680     285  4694.2  282.06  4700.9  277.41
  4715.1  276.03  4721.8  278.47  4729.3  278.98    4736  281.74  4743.6  281.13
  4750.2  282.57  4764.5     283  4807.2  282.62  4881.9   280.1  4906.8  279.06
  4927.7  275.16  4970.4  274.04  4977.1  274.68  4984.7  271.61  4991.3  271.69
  4998.9  268.54  5002.5  268.35  5005.3  267.85  5008.5  268.35  5013.1  273.22
  5019.8  273.42  5023.6  275.55  5161.3  277.88  5393.1  283.07  5637.2  290.74
#Mann= 5 ,-1 , 0
  4495.4     .05       0  4881.9     .12       0  5002.5     .07       0
  5008.5     .12       0  5161.3     .05       0
Bank Sta=5002.5,5008.5
XS Rating Curve= 0 ,0
Exp/Cntr=0.3,0.1

Type RM Length L Ch R = 1 ,2547    ,491,491,491
BEGIN DESCRIPTION:
UNT0470 IN WICK 5.0
END DESCRIPTION:
XS GIS Cut Line= 3
       3626592.1     10263241.62      3626692.11     10263591.64
      3627042.09      10264391.6
#Sta/Elev= 30
  4651.8  292.46  4741.5  286.53  4755.8  286.26  4833.3  281.98  4853.3  281.22
  4880.6  278.59  4887.1  277.47  4892.3  277.62  4923.3  274.24    4943  273.33
  4974.2  273.59  4984.6  272.49  4993.7  269.68  5002.4  268.63  5005.2  268.13
  5008.4  268.63  5013.2  271.42  5018.6  271.42  5024.8  273.47  5030.3  273.75
  5048.2  272.95  5072.4   274.3  5228.3  276.97  5431.8  283.06  5624.3  287.77
  5659.8  289.25    5769  291.72  5804.4  293.16  5822.4   293.2    5889  295.43
#Mann= 6 ,-1 , 0
  4651.8     .05       0  4833.3     .12       0  4923.3     .16       0
  5002.4     .07       0  5008.4     .16       0  5072.4     .05       0
Bank Sta=5002.4,5008.4
XS Rating Curve= 0 ,0
Exp/Cntr=0.3,0.1

Type RM Length L Ch R = 1 ,2056    ,614,614,614
BEGIN DESCRIPTION:
UNT0470 IN WICK 4.0
END DESCRIPTION:
XS GIS Cut Line= 3
      3626320.35     10263399.29        3626303.     10263490.39
      3626832.49     10264380.11
#Sta/Elev= 30
  4617.7  290.84  4635.2  290.54  4687.4  286.71  4782.3   282.7  4845.3  277.77
    4872  275.31  4932.4  273.69  4967.4  272.67  4973.2  270.06  4999.8  267.16
  5002.6  266.66  5005.8  267.16  5010.2  267.24    5016  270.33  5031.6  272.42
    5053  272.16  5068.6  269.71  5139.6   274.9  5148.5  277.04  5154.3  276.66
  5164.1  278.28  5185.5  275.93  5206.9  275.65  5265.3  278.19    5388  281.16
  5419.2  280.48  5440.6  282.52  5520.4  284.17  5637.3  288.98  5745.8  292.17
#Mann= 6 ,-1 , 0
  4617.7     .05       0  4845.3     .12       0  4932.4     .16       0
  4999.8     .07       0  5005.8     .16       0  5139.6     .05       0
Bank Sta=4999.8,5005.8
XS Rating Curve= 0 ,0
Exp/Cntr=0.3,0.1

Type RM Length L Ch R = 1 ,1442    ,654,654,654
BEGIN DESCRIPTION:
UNT0470 IN WICK 2.0
END DESCRIPTION:
XS GIS Cut Line= 2
       3625916.7     10263607.56      3626642.11     10264691.65
#Sta/Elev= 30
    4663  281.14  4719.9  279.09  4734.9  278.18  4755.9  278.04  4806.9  276.05
    4849  275.71    4879  274.49    4921  274.31  4939.1  273.55    4951  272.45
  4966.1  271.83  4980.7   270.4  4987.1  268.54  4993.1  265.21  4999.1  264.34
  5001.8  263.84  5005.1  264.34  5008.1   267.5  5023.1  270.39  5062.4  270.74
  5074.1  270.46  5080.2  271.05  5095.2  270.38  5131.2  272.83  5233.3  276.03
  5317.6  276.84  5362.4  278.29  5485.5  280.47  5671.6  286.96  5967.4  295.93
#Mann= 5 ,-1 , 0
    4663     .05       0  4939.1     .16       0  4999.1     .07       0
  5005.1     .16       0  5062.4     .05       0
Bank Sta=4999.1,5005.1
XS Rating Curve= 0 ,0
Exp/Cntr=0.3,0.1

Type RM Length L Ch R = 1 ,788     ,0,0,0
BEGIN DESCRIPTION:
UNT0470 IN WICK 1.0
END DESCRIPTION:
XS GIS Cut Line= 2
      3624729.96      10263279.5      3626524.34     10264844.55
#Sta/Elev= 30
  3665.7  292.48  3732.8  292.83    3768  291.85  3782.2  292.46    3917  288.99
  4051.8  283.53  4107.8   278.8    4236  279.47  4306.2  275.52  4462.9  274.73
  4547.3  273.17  4604.3  273.82    4966  270.31  4986.9  268.69  4998.1  262.43
  5000.9  261.93  5004.1  262.43    5022  269.46  5029.6  269.91  5072.3  269.36
  5107.4  267.81  5142.6     268  5192.9  274.02  5553.6  279.67  5610.6  281.72
  5632.4  283.48  5659.9   283.6  5850.5  290.92  5921.5  292.35  6046.7  295.16
#Mann= 5 ,-1 , 0
  3665.7     .05       0  4998.1     .04       0  5004.1     .05       0
  5850.5     .08       0  5921.5     .05       0
Bank Sta=4998.1,5004.1
XS Rating Curve= 0 ,0
Exp/Cntr=0.3,0.1

Chan Stop Cuts=-1
Use User Specified Reach Order=0
Composite Channel Slope=5