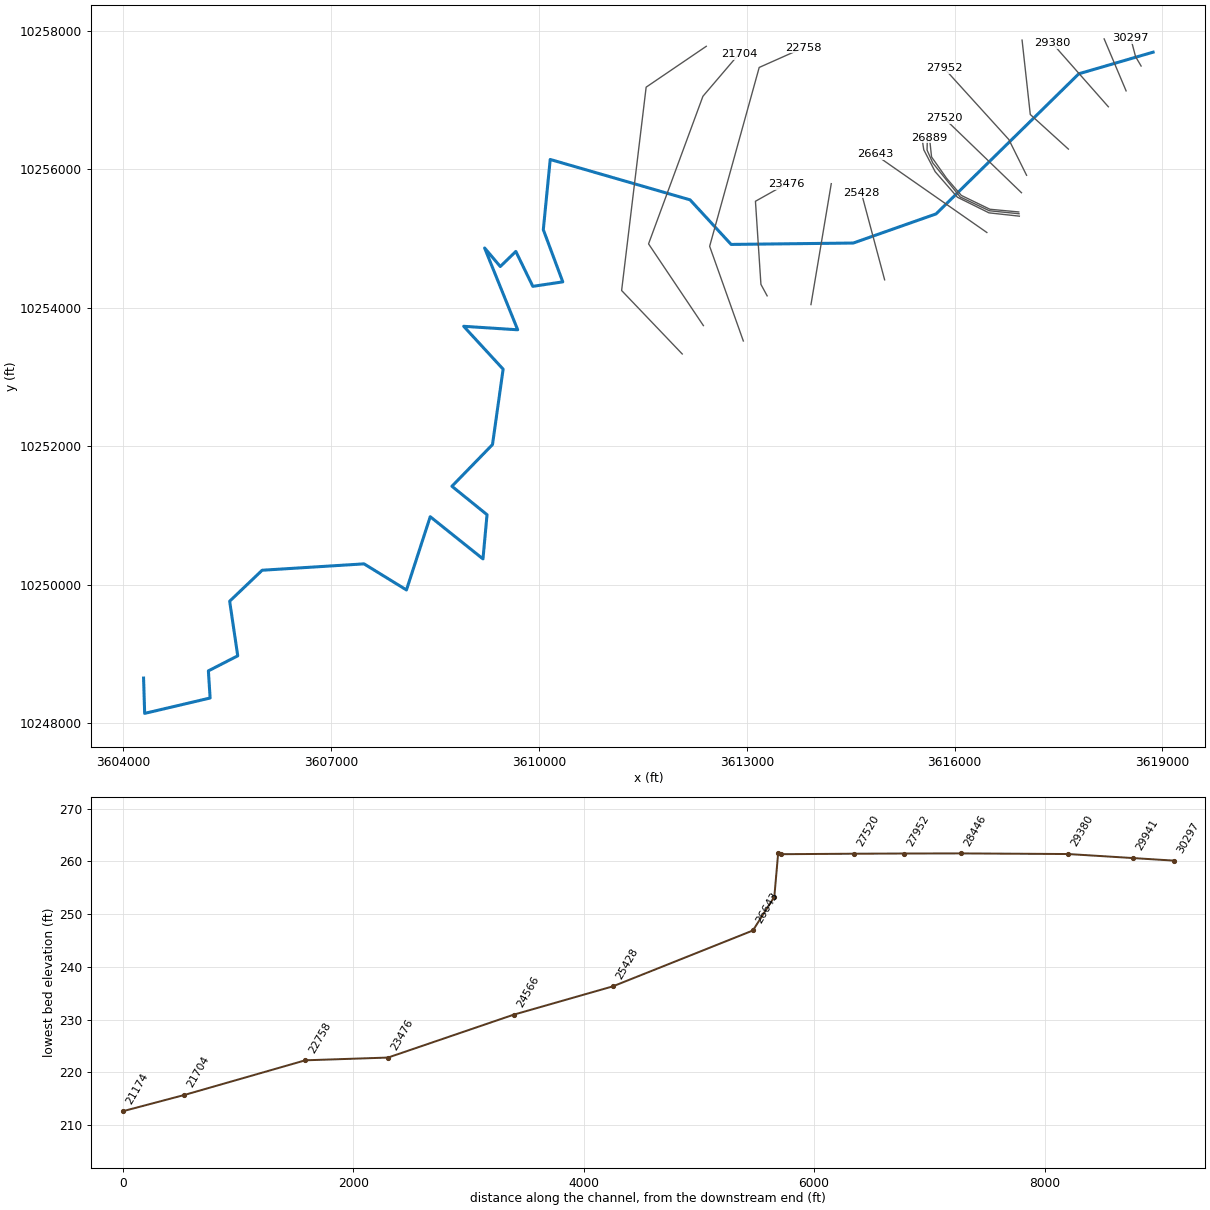
--- UNT0475 IN WICK.prj (project) ---

Proj Title=UNT0475 IN WICK Base Level Engineering
Current Plan=p01
Default Exp/Contr=0.3,0.1
English Units
Geom File=g01
Flow File=f01
Plan File=p01
Y Axis Title=Elevation
X Axis Title(PF)=Main Channel Distance
X Axis Title(XS)=Station
BEGIN DESCRIPTION:
UNT0475 IN WICK
END DESCRIPTION:
DSS Export Rating Curves= 0
DSS Export Rating Curve Sorted= 0
DSS Export Volume Flow Curves= 0
DXF OffsetX= 0
DXF OffsetY= 0
DXF ScaleX= 1
DXF ScaleY= 10

--- UNT0475 IN WICK.p01 (plan) ---

Plan Title=Multiple Run
Short Identifier=Multiple
Geom File=g01
Flow File=f01
Subcritical Flow
K Sum by GR= 0
Std Step Tol= 0.01
Critical Tol= 0.01
Num of Std Step Trials= 20
Max Error Tol= 0.3
Flow Tol Ratio= 0.001
Split Flow NTrial= 30
Split Flow Tol= 0.02
Split Flow Ratio= 0.02
Log Output Level= 0
Friction Slope Method= 1
Unsteady Friction Slope Method= 2
Unsteady Bridges Friction Slope Method= 1
Parabolic Critical Depth
Global Vel Dist=  1 , 1 , 1
Global Log Level= 0
CheckData=True
Encroach Param= -1, 0, 0, 0
BEGIN DESCRIPTION:
Multiple Run
END DESCRIPTION:

--- UNT0475 IN WICK.f01 (steady flow) ---

Flow Title=Multiple
Number of Profiles=7
Profile Names=10-year,25-year,50-year,1pct_min,100-year,1pct_plu,500-year
River Rch & RM= UNT0475 IN WICK,Reach-1,30297
     510     679     816     719     972    1315    1382
River Rch & RM= UNT0475 IN WICK,Reach-1,26889
     835    1146    1404    1259    1703    2303    2511
Boundary for River Rch & Prof#=UNT0475 IN WICK,Reach-1,1
Up Type=0
Dn Type=3
Dn Slope=0.005
Boundary for River Rch & Prof#=UNT0475 IN WICK,Reach-1,2
Up Type=0
Dn Type=3
Dn Slope=0.005
Boundary for River Rch & Prof#=UNT0475 IN WICK,Reach-1,3
Up Type=0
Dn Type=3
Dn Slope=0.005
Boundary for River Rch & Prof#=UNT0475 IN WICK,Reach-1,4
Up Type=0
Dn Type=3
Dn Slope=0.005
Boundary for River Rch & Prof#=UNT0475 IN WICK,Reach-1,5
Up Type=0
Dn Type=3
Dn Slope=0.005
Boundary for River Rch & Prof#=UNT0475 IN WICK,Reach-1,6
Up Type=0
Dn Type=3
Dn Slope=0.005
Boundary for River Rch & Prof#=UNT0475 IN WICK,Reach-1,7
Up Type=0
Dn Type=3
Dn Slope=0.005

--- UNT0475 IN WICK.g01 (geometry) ---

Geom Title=Existing Conditions
Program Version=4.10

River Reach=UNT0475 IN WICK ,Reach-1
Reach XY= 30
       3618865.7     10257691.95      3617792.85     10257379.56
      3615732.36     10255355.65      3614536.83     10254934.58
      3612773.47      10254914.6      3612180.62     10255558.56
        3610162.     10256141.76      3610062.27     10255127.26
      3610343.42     10254373.76      3609910.78     10254309.18
      3609665.64     10254813.34      3609441.33     10254595.29
      3609214.95     10254863.34      3609692.48     10253681.53
       3608912.8     10253731.86      3609482.24     10253112.55
      3609328.53     10252023.11      3608743.08     10251421.23
      3609249.77     10251010.72       3609191.4     10250371.55
      3608429.96     10250981.62      3608086.61     10249923.64
      3607474.17     10250300.37      3606003.56     10250208.12
      3605534.51     10249760.65      3605651.06     10248972.08
      3605227.37     10248754.38      3605252.45     10248362.46
      3604307.48     10248140.62       3604291.7     10248650.61

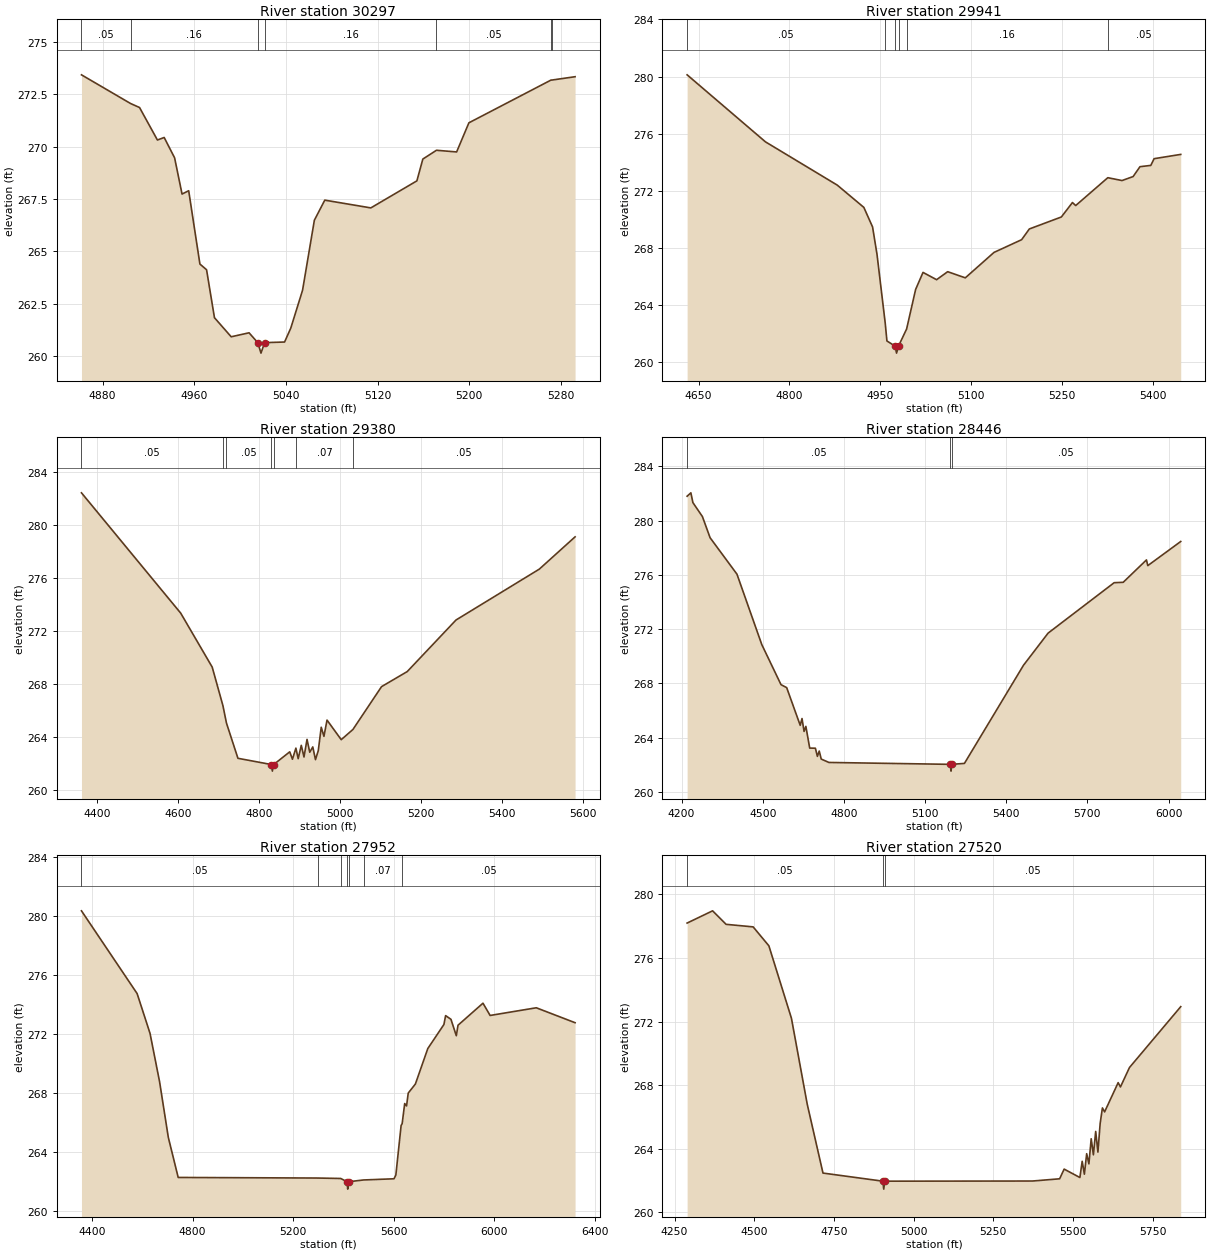
Type RM Length L Ch R = 1 ,30297   ,356,356,356
BEGIN DESCRIPTION:
UNT0475 IN WICK 35.0
END DESCRIPTION:
XS GIS Cut Line= 3
       3618692.1     10257491.65      3618612.24     10257626.93
      3618542.11     10257891.61
#Sta/Elev= 30
  4861.5  273.43  4904.4  272.06  4912.2  271.87  4927.8  270.32  4933.7  270.44
  4942.8  269.47  4949.3  267.74  4955.1   267.9  4964.9   264.4  4970.7  264.13
  4977.6  261.84  4992.2  260.93  5007.8  261.12  5015.4  260.65  5018.2  260.15
  5021.4  260.65  5038.8  260.68  5044.2  261.34  5054.5  263.15  5064.8  266.49
  5073.9  267.45  5114.1  267.08  5154.3  268.37  5159.5  269.41  5171.4  269.83
    5189  269.75  5199.7  271.14  5271.4  273.18  5272.1  273.18  5292.4  273.34
#Mann= 7 ,-1 , 0
  4861.5     .05       0  4904.4     .16       0  5015.4     .07       0
  5021.4     .16       0  5171.4     .05       0  5271.4     .16       0
  5272.1     .05       0
Bank Sta=5015.4,5021.4
XS Rating Curve= 0 ,0
Exp/Cntr=0.3,0.1

Type RM Length L Ch R = 1 ,29941   ,561,561,561
BEGIN DESCRIPTION:
UNT0475 IN WICK 34.0
END DESCRIPTION:
XS GIS Cut Line= 2
      3618475.37     10257132.77      3618158.52     10257883.66
#Sta/Elev= 30
    4631  280.12  4760.3  275.43  4878.9   272.4  4922.8  270.84  4937.2  269.47
  4944.5  267.56    4958  262.77  4960.9  261.49  4974.1  261.14  4976.8  260.64
  4980.1  261.14  4993.4  262.33  5008.3   265.1  5020.5  266.29  5042.9  265.78
  5061.2  266.34  5090.3  265.91  5137.7  267.69  5183.3  268.58    5196  269.33
  5248.9  270.17  5267.2  271.18  5272.6  270.97  5325.6  272.92  5349.1  272.72
  5367.4     273  5378.7  273.69  5396.6  273.78    5402  274.25    5446  274.55
#Mann= 6 ,-1 , 0
    4631     .05       0    4958     .07       0  4974.1     .07       0
  4980.1     .07       0  4993.4     .16       0  5325.6     .05       0
Bank Sta=4974.1,4980.1
XS Rating Curve= 0 ,0
Exp/Cntr=0.3,0.1

Type RM Length L Ch R = 1 ,29380   ,934,934,934
BEGIN DESCRIPTION:
UNT0475 IN WICK 33.0
END DESCRIPTION:
XS GIS Cut Line= 2
      3618219.31     10256902.73      3617412.82     10257817.61
#Sta/Elev= 30
  4361.4  282.45  4606.6  273.35  4684.4  269.27    4711  266.34  4719.6  265.04
    4748  262.37  4830.4   261.9  4833.1   261.4  4836.4   261.9    4876  262.86
  4882.7   262.3  4891.2  263.14  4896.9  262.34  4904.5  263.35  4911.2  262.47
  4918.7   263.8  4925.4  262.83  4932.9  263.23  4939.6  262.27  4946.5  262.95
  4953.8  264.72  4960.5  264.03  4968.1  265.26  5003.2  263.78  5032.1  264.55
  5102.8  267.79  5166.3  268.93  5286.8  272.83  5492.7  276.68    5581  279.12
#Mann= 7 ,-1 , 0
  4361.4     .05       0    4711     .07       0  4719.6     .05       0
  4830.4     .07       0  4836.4     .05       0  4891.2     .07       0
  5032.1     .05       0
Bank Sta=4830.4,4836.4
XS Rating Curve= 0 ,0
Exp/Cntr=0.3,0.1

Type RM Length L Ch R = 1 ,28446   ,494,494,494
BEGIN DESCRIPTION:
UNT0475 IN WICK 31.0
END DESCRIPTION:
XS GIS Cut Line= 3
      3617642.14     10256291.61      3617092.11     10256791.64
      3616973.62     10257866.28
#Sta/Elev= 30
  4220.4   281.8  4234.3  282.05  4241.7  281.33  4276.9   280.3  4305.2  278.74
  4404.6  276.05  4496.5  270.85  4567.4   267.9  4588.4  267.68  4638.4   264.9
  4645.1   265.4  4652.6  264.45  4659.3  264.82  4673.5  263.22  4694.5  263.21
  4701.9  262.61  4708.7     263  4716.1  262.41  4744.5  262.16    5193  262.02
  5195.8  261.52    5199  262.02  5245.4  262.09  5463.7  269.33  5554.6   271.7
  5798.8  275.42  5832.3  275.45  5918.2   277.1  5923.2  276.68  6044.9  278.46
#Mann= 3 ,-1 , 0
  4220.4     .05       0    5193    .033       0    5199     .05       0
Bank Sta=5193,5199
XS Rating Curve= 0 ,0
Exp/Cntr=0.3,0.1

Type RM Length L Ch R = 1 ,27952   ,432,432,432
BEGIN DESCRIPTION:
UNT0475 IN WICK 30.0
END DESCRIPTION:
XS GIS Cut Line= 3
      3617038.74     10255913.15      3616782.65     10256429.67
      3615850.28     10257457.45
#Sta/Elev= 30
    4358  280.33  4579.5  274.73  4630.8  272.04  4668.8  268.77  4703.6     265
  4742.9  262.29  5297.3  262.25  5389.7  262.22  5414.8     262  5417.5   261.5
  5420.8     262  5480.5  262.12  5601.6   262.2    5609  262.45    5630  265.81
  5634.1  265.93  5644.2  267.29  5651.6  267.13  5658.3     268  5686.7  268.61
  5736.1  271.01  5800.3  272.64    5807  273.24  5828.3  272.99  5849.6  271.88
  5856.4  272.59  5955.7  274.08  5984.1  273.25  6167.9  273.77  6322.2  272.76
#Mann= 7 ,-1 , 0
    4358     .05       0  5297.3     .07       0  5389.7     .05       0
  5414.8    .033       0  5420.8     .05       0  5480.5     .07       0
  5634.1     .05       0
Bank Sta=5414.8,5420.8
XS Rating Curve= 0 ,0
Exp/Cntr=0.3,0.1

Type RM Length L Ch R = 1 ,27520   ,631,631,631
BEGIN DESCRIPTION:
UNT0475 IN WICK 29.0
END DESCRIPTION:
XS GIS Cut Line= 2
      3616964.92     10255661.47      3615850.12     10256737.22
#Sta/Elev= 30
  4289.3   278.2  4369.2  278.97  4411.6  278.12  4496.5  277.96  4545.9  276.77
  4616.7  272.21  4666.3   266.8  4715.7  262.47  4903.6  261.96  4906.4  261.46
  4909.6  261.96  5373.5  261.97  5458.4  262.11  5472.6  262.72    5522  262.19
  5529.2  263.21  5536.1   262.4  5543.3  263.69  5550.3  263.05  5557.5  264.63
  5564.4  263.62  5571.6  265.09  5578.6  263.79  5585.6  265.59  5592.7  266.57
  5599.6  266.32  5642.1  268.16  5649.3  267.89  5677.6  269.11  5838.5  272.94
#Mann= 3 ,-1 , 0
  4289.3     .05       0  4903.6    .033       0  4909.6     .05       0
Bank Sta=4903.6,4909.6
XS Rating Curve= 0 ,0
Exp/Cntr=0.3,0.1

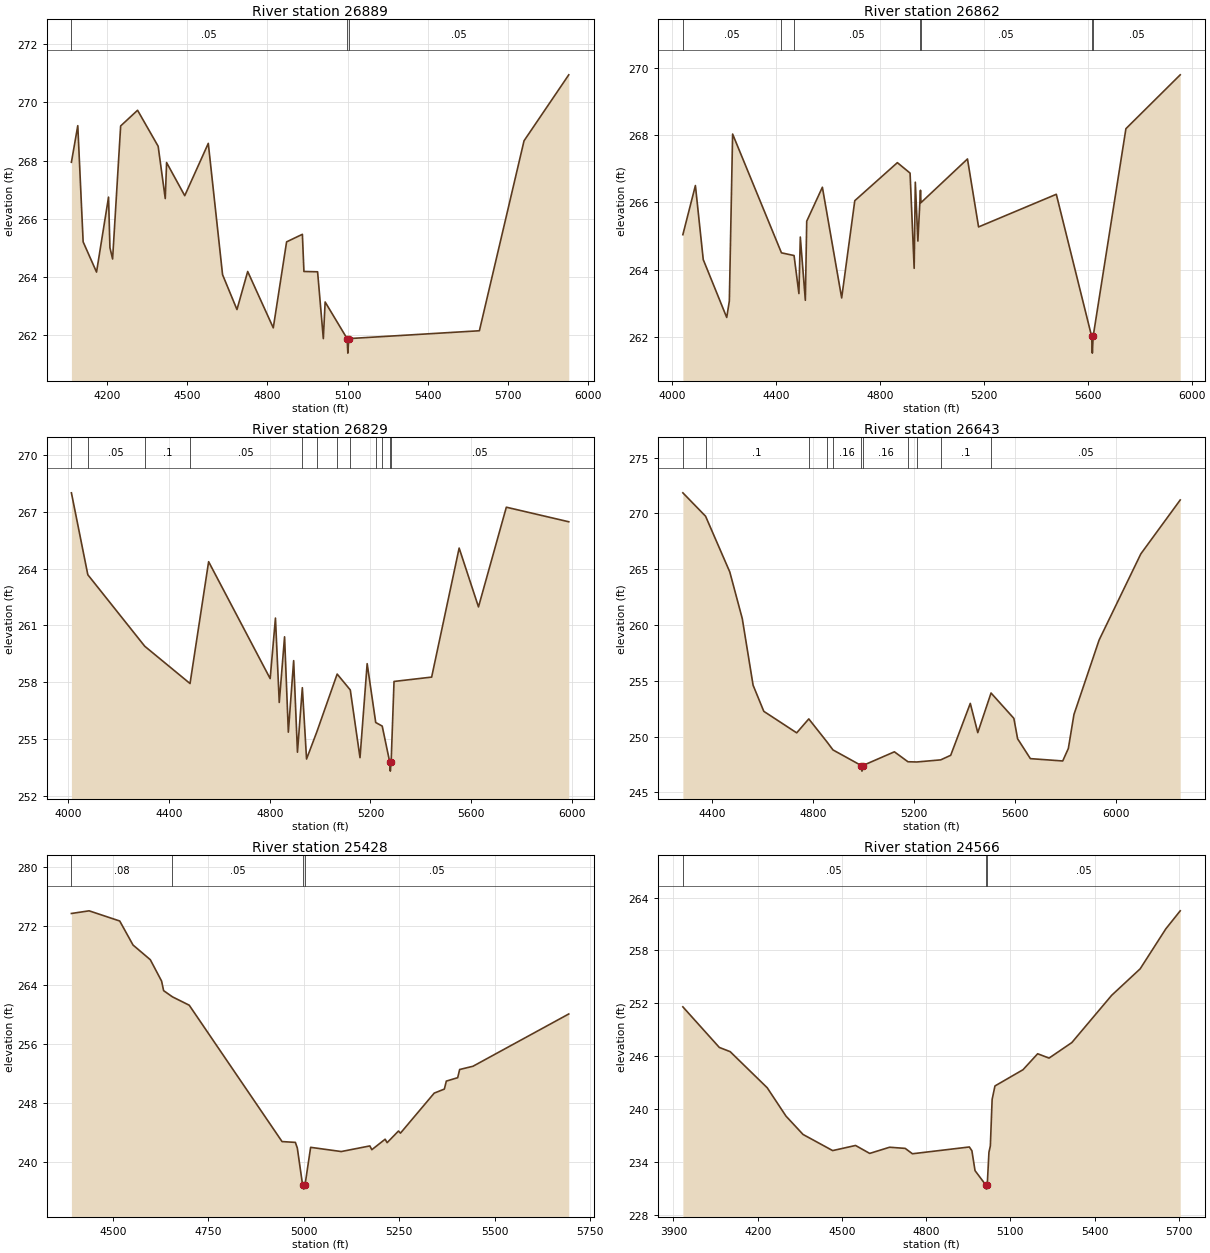
Type RM Length L Ch R = 1 ,26889   ,27,27,27
BEGIN DESCRIPTION:
Mapping XS 293b00b3
END DESCRIPTION:
XS GIS Cut Line= 6
      3616925.87     10255383.67      3616509.21     10255422.73
      3616096.89     10255622.38      3615884.21     10255869.78
       3615667.2     10256177.94      3615636.86     10256458.37
#Sta/Elev= 30
    4065  267.94  4088.9   269.2    4109   265.2  4159.2  264.16  4204.2  266.74
  4209.4     265  4219.4  264.61  4249.6  269.19    4313  269.73  4390.2  268.49
  4416.8  266.69  4421.8  267.93  4489.8  266.79  4578.1  268.59  4631.6  264.07
  4685.6  262.87  4725.8  264.18  4821.7  262.24  4871.6   265.2  4930.8  265.46
  4936.6  264.18  4987.8  264.17  5009.3  261.87  5016.1  263.13  5098.5  261.87
  5101.2  261.37  5104.5  261.87  5594.3  262.14  5761.7  268.68  5929.3  270.95
#Mann= 3 ,-1 , 0
    4065     .05       0  5098.5     .03       0  5104.5     .05       0
Bank Sta=5098.5,5104.5
XS Rating Curve= 0 ,0
Exp/Cntr=0.3,0.1

Type RM Length L Ch R = 1 ,26862   ,33,33,33
BEGIN DESCRIPTION:
Mapping XS 2c4d9d35
END DESCRIPTION:
XS GIS Cut Line= 6
      3616930.18     10255357.63      3616500.53     10255401.03
      3616079.52     10255600.68      3615684.56     10256091.13
      3615602.09     10256277.76      3615606.39      10256458.3
#Sta/Elev= 30
  4040.7  265.04    4089   266.5  4119.2   264.3  4209.6  262.58  4219.7  263.07
  4232.3  268.03  4420.4   264.5  4468.9  264.42  4487.6  263.29    4493  264.97
  4512.4  263.09  4517.7  265.44    4578  266.45  4652.3  263.16  4702.8  266.05
  4866.8  267.18  4915.7  266.87  4931.5  264.04  4935.9   266.6  4945.8  264.85
  4955.8  266.36  4957.5  265.99  5136.8  267.29  5179.5  265.27  5478.9  266.24
  5614.9  262.02  5617.7  261.52  5620.9  262.02    5747  268.19  5956.1  269.79
#Mann= 7 ,-1 , 0
  4040.7     .05       0  4420.4      .1       0  4468.9     .05       0
  4955.8      .1       0  4957.5     .05       0  5614.9     .03       0
  5620.9     .05       0
Bank Sta=5614.9,5620.9
XS Rating Curve= 0 ,0
Exp/Cntr=0.3,0.1

Type RM Length L Ch R = 1 ,26829   ,186,186,186
BEGIN DESCRIPTION:
Mapping XS 1a0cc8de
END DESCRIPTION:
XS GIS Cut Line= 6
      3616934.52     10255322.91      3616496.19     10255370.64
      3616040.46     10255596.34      3615719.28     10255965.26
      3615554.35      10256282.1      3615528.31     10256455.68
#Sta/Elev= 30
  4012.5  268.01  4077.7  263.68  4303.8   259.9  4483.6  257.93  4557.4  264.37
  4801.8  258.19  4822.8  261.39  4837.9  256.93    4859   260.4    4874  255.36
  4895.1  259.14  4910.2   254.3  4929.6  257.71  4946.3  253.94    4987  255.37
  5067.9  258.43    5120  257.59  5158.6  254.01    5187  258.98    5221  255.87
  5246.8  255.68  5276.3   253.8    5279   253.3  5282.3   253.8  5293.7  258.04
  5443.1  258.27  5552.3  265.09  5629.1  261.98  5739.7  267.25  5987.6  266.48
#Mann= 12 ,-1 , 0
  4012.5      .1       0  4077.7     .05       0  4303.8      .1       0
  4483.6     .05       0  4929.6      .1       0    4987     .05       0
  5067.9      .1       0    5120     .05       0    5221      .1       0
  5246.8     .05       0  5276.3     .03       0  5282.3     .05       0
Bank Sta=5276.3,5282.3
XS Rating Curve= 0 ,0
Exp/Cntr=0.3,0.1

Type RM Length L Ch R = 1 ,26643   ,1215,1215,1215
BEGIN DESCRIPTION:
UNT0475 IN WICK 27.0
END DESCRIPTION:
XS GIS Cut Line= 2
      3616465.19     10255087.11      3614848.47     10256215.56
#Sta/Elev= 30
  4283.1  271.84  4373.2  269.74  4469.1  264.75  4518.6  260.57  4561.5   254.6
  4603.9  252.26  4734.3  250.33  4782.3  251.58  4854.7  249.51  4878.2   248.8
  4990.4   247.4  4993.1   246.9  4996.4   247.4  5121.6  248.63  5175.4  247.74
  5210.4  247.72  5305.5  247.91  5344.9  248.32  5422.5  252.97  5452.2  250.35
  5504.8   253.9  5595.2  251.63  5610.1   249.8  5660.7  248.02  5788.9  247.81
  5811.2  248.93  5833.4  251.97  5933.2  258.65  6098.6  266.37  6254.7   271.2
#Mann= 11 ,-1 , 0
  4283.1     .05       0  4373.2      .1       0  4782.3     .16       0
  4854.7      .1       0  4878.2     .16       0  4990.4     .07       0
  4996.4     .16       0  5175.4      .1       0  5210.4     .16       0
  5305.5      .1       0  5504.8     .05       0
Bank Sta=4990.4,4996.4
XS Rating Curve= 0 ,0
Exp/Cntr=0.3,0.1

Type RM Length L Ch R = 1 ,25428   ,862,862,862
BEGIN DESCRIPTION:
UNT0475 IN WICK 25.0
END DESCRIPTION:
XS GIS Cut Line= 2
      3614989.54     10254403.48      3614653.15     10255662.21
#Sta/Elev= 30
    4391  273.64  4437.4     274  4517.6  272.62  4552.4  269.37  4597.7  267.38
  4627.2  264.49  4632.6  263.19  4655.7  262.35  4699.6  261.22  4942.8  242.75
  4977.7  242.64  4982.8  241.88  4996.8  236.81  4999.6  236.31  5002.8  236.81
  5017.7  241.97  5097.9   241.4  5172.8  242.16    5178  241.65  5212.9  243.07
  5218.1   242.6  5247.8  244.18    5253  243.89  5341.4  249.31    5368  249.86
  5373.2  250.94  5402.9   251.4  5408.1  252.51    5443  252.95  5693.9  260.03
#Mann= 4 ,-1 , 0
    4391     .08       0  4655.7     .05       0  4996.8     .04       0
  5002.8     .05       0
Bank Sta=4996.8,5002.8
XS Rating Curve= 0 ,0
Exp/Cntr=0.3,0.1

Type RM Length L Ch R = 1 ,24566   ,1090,1090,1090
BEGIN DESCRIPTION:
UNT0475 IN WICK 22.0
END DESCRIPTION:
XS GIS Cut Line= 2
      3613926.17     10254045.44      3614219.13     10255792.35
#Sta/Elev= 30
  3933.7   251.6  4063.5     247  4102.2  246.52    4234  242.43    4301  239.21
  4361.7  237.13  4467.2   235.3  4548.7  235.88  4599.1  234.98    4670  235.68
  4725.6  235.55  4751.2  234.94    4954  235.71  4963.1  235.28  4974.2  233.03
  5011.8  231.43  5014.5  230.93  5017.8  231.43  5023.8  235.11  5028.8  235.83
  5035.1  241.09  5045.2  242.63  5145.1  244.47  5197.3  246.28  5237.9  245.79
    5319  247.55  5460.9  252.91  5562.3  255.91  5653.6  260.44    5705  262.49
#Mann= 3 ,-1 , 0
  3933.7     .05       0  5011.8     .03       0  5017.8     .05       0
Bank Sta=5011.8,5017.8
XS Rating Curve= 0 ,0
Exp/Cntr=0.3,0.1

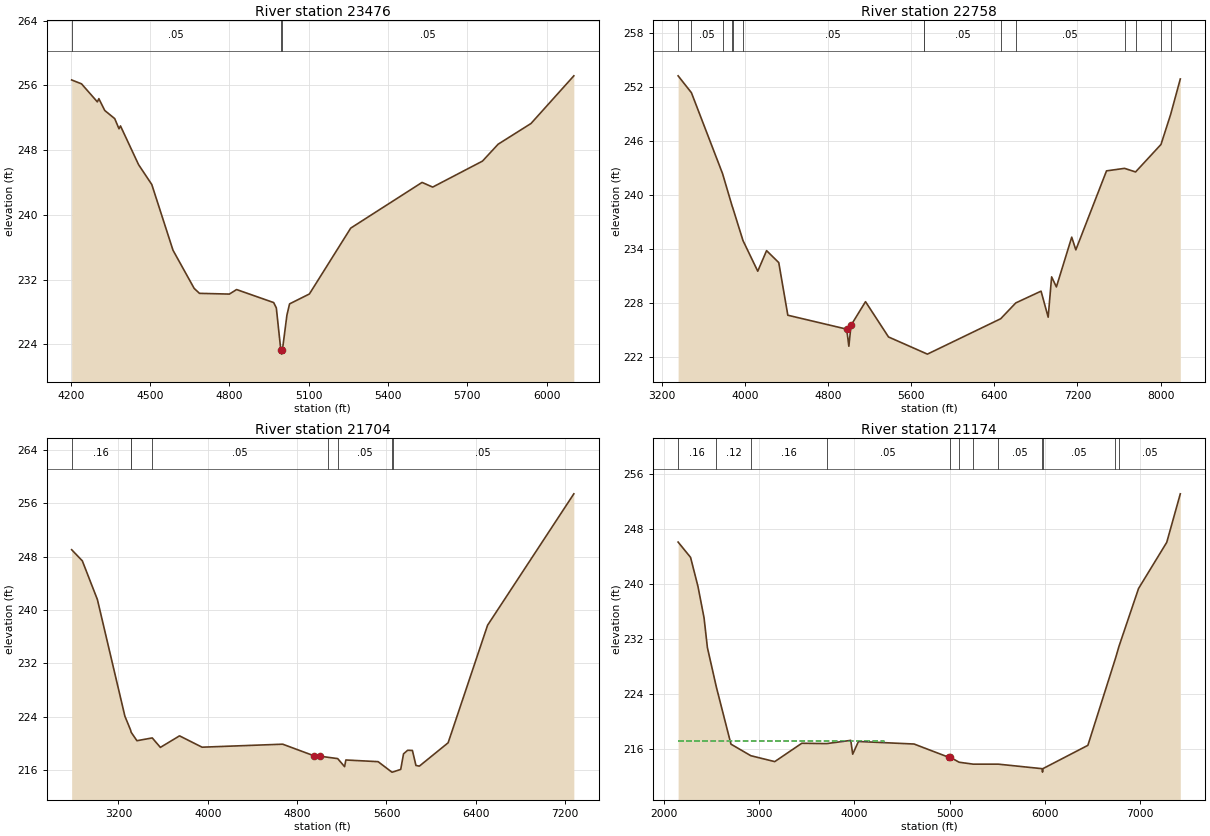
Type RM Length L Ch R = 1 ,23476   ,718,718,718
BEGIN DESCRIPTION:
UNT0475 IN WICK 18.0
END DESCRIPTION:
XS GIS Cut Line= 4
      3613293.69      10254171.6      3613203.78     10254337.58
       3613124.7     10255538.05      3613567.08     10255786.67
#Sta/Elev= 30
  4203.3  256.68  4240.6   256.2  4300.6  253.97  4306.2  254.37  4328.5  252.91
  4366.2   251.9  4382.4  250.65    4388     251  4456.3  246.22  4506.4  243.76
  4586.6  235.64  4666.7  230.92  4686.8  230.31  4799.9  230.22  4827.1  230.78
  4967.4  229.17  4977.4  228.51  4994.4   223.3  4997.2   222.8  5000.4   223.3
  5017.5  227.63  5027.5  229.01  5102.4  230.23  5258.7  238.37  5528.6  244.02
  5568.7  243.44    5757  246.65  5816.3  248.74  5940.6   251.3  6102.6  257.19
#Mann= 3 ,-1 , 0
  4203.3     .05       0  4994.4     .03       0  5000.4     .05       0
Bank Sta=4994.4,5000.4
XS Rating Curve= 0 ,0
Exp/Cntr=0.3,0.1

Type RM Length L Ch R = 1 ,22758   ,1054,1054,1054
BEGIN DESCRIPTION:
Mapping XS b0ee0873
END DESCRIPTION:
XS GIS Cut Line= 4
       3612949.7     10253519.68      3612463.59     10254887.74
      3613178.87     10257471.08      3613817.43     10257755.65
#Sta/Elev= 30
  3358.1  253.26  3486.1  251.38  3785.5  242.38  3879.4   238.7  3882.2  238.63
  3982.3  234.92  4124.3  231.51  4209.2   233.8  4326.4  232.47  4413.7  226.61
    4980  225.06  5000.8  223.16  5021.5  225.49    5161  228.12  5382.4  224.19
  5756.5  222.28  6461.6  226.22  6606.7  227.98  6849.9  229.29  6918.5  226.39
  6951.5  230.88  6997.5  229.76    7145   235.3  7184.5  233.89  7479.7  242.68
    7653  242.96  7759.2  242.56  8003.7  245.62  8096.6  248.96  8189.6  252.91
#Mann= 14 ,-1 , 0
  3358.1      .1       0  3486.1     .05       0  3785.5     .16       0
  3879.4     .05       0  3882.2     .16       0  3982.3     .05       0
  5719.2     .03       0  5725.2     .05       0  6461.6     .08       0
  6606.7     .05       0    7653     .16       0  7759.2     .05       0
  8003.7     .16       0  8096.6     .05       0
#XS Ineff= 2 , 0
                         5166.67          227.96
Permanent Ineff=
       F       F
Bank Sta=4980,5021.5
XS Rating Curve= 0 ,0
Exp/Cntr=0.3,0.1

Type RM Length L Ch R = 1 ,21704   ,530,530,530
BEGIN DESCRIPTION:
Mapping XS 43f3caa0
END DESCRIPTION:
XS GIS Cut Line= 4
      3612373.34     10253741.87      3611581.64     10254922.46
      3612366.37     10257054.41      3612887.14     10257665.45
#Sta/Elev= 30
  2781.5  249.04    2877  247.37  3012.1  241.56  3258.2  224.07  3309.2  221.99
  3314.8  221.64  3366.2  220.39  3503.1  220.81  3575.9  219.39  3747.4  221.12
  3949.1  219.42    4671  219.87    4948  218.15  5003.5  218.07  5078.8   217.9
  5163.2  217.71  5225.1   216.5  5236.5   217.5  5525.1  217.25  5648.3  215.68
  5654.3  215.68  5727.7  216.09  5752.8  218.42  5789.8  218.96  5832.4  218.93
    5864  216.68  5894.5  216.58  6152.1  220.08  6505.3  237.71  7277.6  257.42
#Mann= 8 ,-1 , 0
  2781.5     .16       0  3309.2     .05       0  3314.8     .16       0
  3503.1     .05       0  5078.8     .08       0  5163.2     .05       0
  5648.3     .03       0  5654.3     .05       0
#XS Ineff= 2 , 0
       0                 5009.12       0  218.01
Permanent Ineff=
       F       T
Bank Sta=4948,5003.5
XS Rating Curve= 0 ,0
Exp/Cntr=0.3,0.1

Type RM Length L Ch R = 1 ,21174   ,0,0,0
BEGIN DESCRIPTION:
UNT0475 IN WICK 1.0
END DESCRIPTION:
XS GIS Cut Line= 4
      3612067.76     10253332.18      3611192.76     10254248.85
      3611546.92     10257186.35      3612415.01     10257776.65
#Sta/Elev= 30
  2148.5   246.1  2279.4  243.87  2357.1  239.64    2421  235.07  2456.2  230.74
  2550.6  224.98  2703.7  216.69  2912.3  215.01  3163.6  214.15  3447.9  216.82
  3708.7  216.77  3962.5  217.24  3982.6  215.23  4043.1  217.08  4627.3  216.71
  4989.9  214.79  5001.2  214.75    5010  214.76  5100.6  214.06  5248.7  213.78
  5511.9  213.78    5974  213.12  5976.7  212.62    5980  213.12  6453.4  216.52
  6743.2  229.18  6779.9  230.92  6985.6  239.34  7281.9  246.06  7424.3  253.12
#Mann= 12 ,-1 , 0
  2148.5     .16       0  2550.6     .12       0  2912.3     .16       0
  3708.7     .05       0  5001.2     .08       0  5100.6     .05       0
  5248.7     .07       0  5511.9     .05       0    5974     .03       0
    5980     .05       0  6743.2     .08       0  6779.9     .05       0
#XS Ineff= 2 , 0
       0 4306.26  217.08  5010.6       0  214.73
Permanent Ineff=
       F       T
Bank Sta=4989.9,5010
XS Rating Curve= 0 ,0
Exp/Cntr=0.3,0.1

Chan Stop Cuts=-1
Use User Specified Reach Order=0
Composite Channel Slope=5