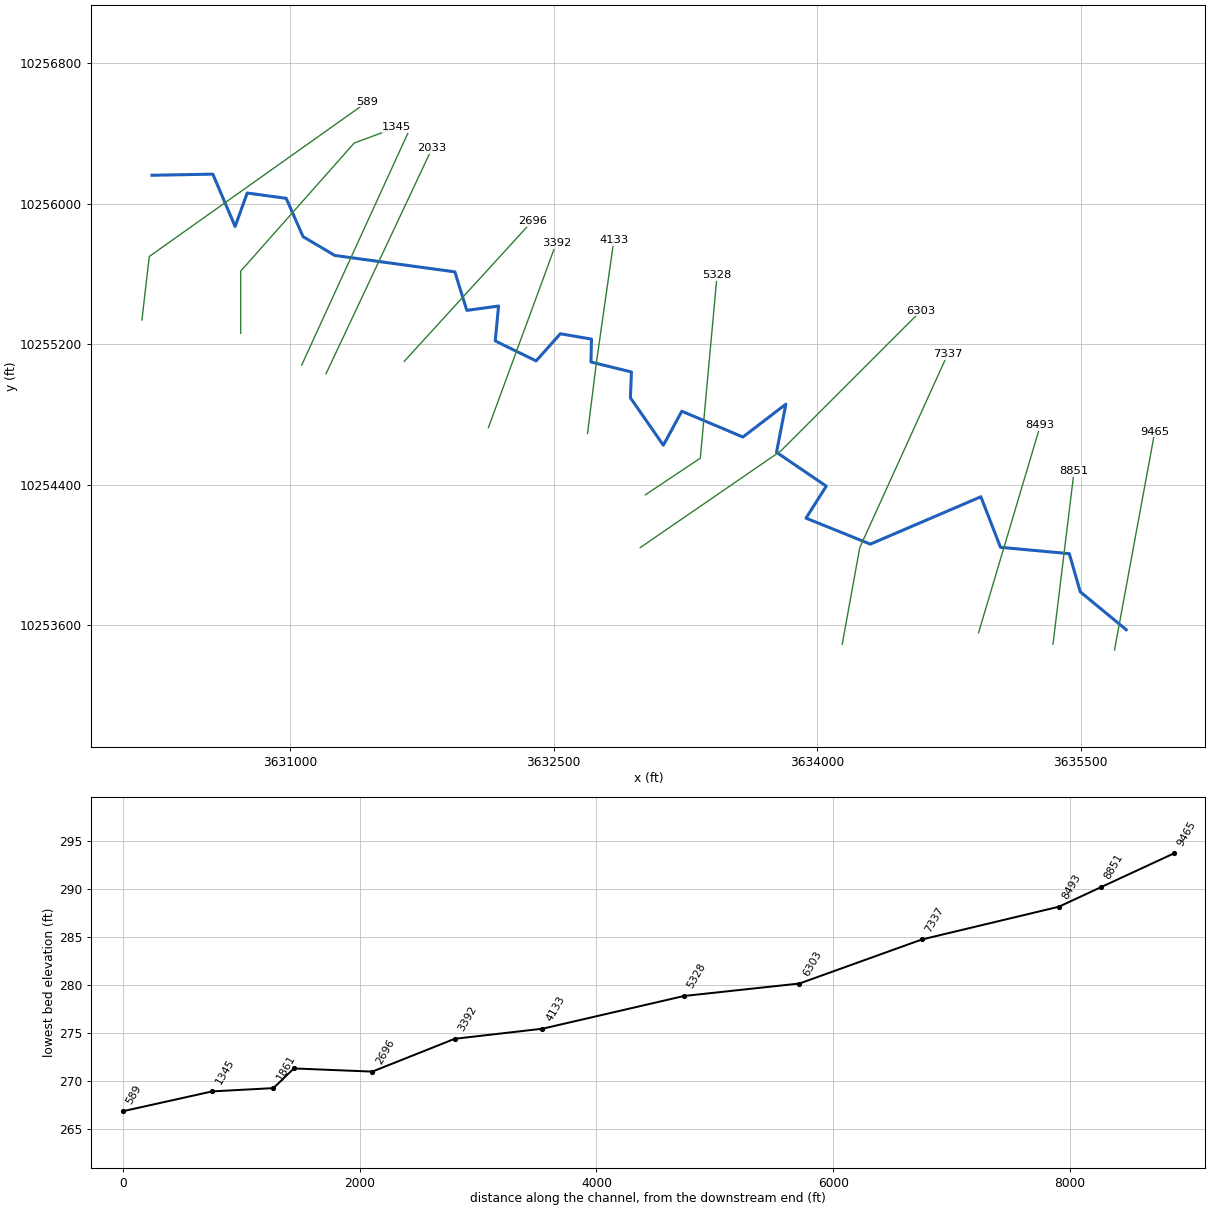
--- UNT0481 IN WICK.prj (project) ---

Proj Title=UNT0481 IN WICK Base Level Engineering
Current Plan=p01
Default Exp/Contr=0.3,0.1
English Units
Geom File=g01
Flow File=f01
Plan File=p01
BEGIN DESCRIPTION:
UNT0481 IN WICK
END DESCRIPTION:

--- UNT0481 IN WICK.p01 (plan) ---

Plan Title=Multiple Run
Short Identifier=Multiple
Geom File=g01
Flow File=f01
Subcritical Flow
K Sum by GR= 0
Std Step Tol= 0.01
Critical Tol= 0.01
Num of Std Step Trials= 20
Max Error Tol= 0.3
Flow Tol Ratio= 0.001
Split Flow NTrial= 30
Split Flow Tol= 0.02
Split Flow Ratio= 0.02
Log Output Level= 0
Friction Slope Method= 1
Unsteady Friction Slope Method= 2
Unsteady Bridges Friction Slope Method= 1
Parabolic Critical Depth
Global Vel Dist=  1 , 1 , 1
Global Log Level= 0
CheckData=True
Encroach Param= -1, 0, 0, 0
BEGIN DESCRIPTION:
Multiple Run
END DESCRIPTION:

--- UNT0481 IN WICK.f01 (steady flow) ---

Flow Title=Multiple
Number of Profiles=7
Profile Names=10-year,25-year,50-year,1pct_min,100-year,1pct_plu,500-year
River Rch & RM= UNT0481 IN WICK,Reach-1,9465
     623     835    1008     891    1206    1630    1727
River Rch & RM= UNT0481 IN WICK,Reach-1,6303
     747    1008    1221    1083    1464    1980    2109
Boundary for River Rch & Prof#=UNT0481 IN WICK,Reach-1,1
Up Type=0
Dn Type=3
Dn Slope=0.005
Boundary for River Rch & Prof#=UNT0481 IN WICK,Reach-1,2
Up Type=0
Dn Type=3
Dn Slope=0.005
Boundary for River Rch & Prof#=UNT0481 IN WICK,Reach-1,3
Up Type=0
Dn Type=3
Dn Slope=0.005
Boundary for River Rch & Prof#=UNT0481 IN WICK,Reach-1,4
Up Type=0
Dn Type=3
Dn Slope=0.005
Boundary for River Rch & Prof#=UNT0481 IN WICK,Reach-1,5
Up Type=0
Dn Type=3
Dn Slope=0.005
Boundary for River Rch & Prof#=UNT0481 IN WICK,Reach-1,6
Up Type=0
Dn Type=3
Dn Slope=0.005
Boundary for River Rch & Prof#=UNT0481 IN WICK,Reach-1,7
Up Type=0
Dn Type=3
Dn Slope=0.005

--- UNT0481 IN WICK.g01 (geometry) ---

Geom Title=Existing Conditions

River Reach=UNT0481 IN WICK,Reach-1
Reach XY= 30
      3635759.20     10253574.25      3635497.67     10253789.92
      3635434.99     10254007.24      3635043.40     10254043.40
      3634931.58     10254331.24      3634302.11     10254061.64
      3633935.96     10254209.56      3634051.31     10254391.67
      3633768.12     10254584.33      3633821.29     10254858.42
      3633576.87     10254671.38      3633228.92     10254818.33
      3633123.72     10254624.67      3632936.24     10254894.80
      3632942.11     10255041.64      3632711.74     10255098.37
      3632714.54     10255229.00      3632537.46     10255259.21
      3632399.32     10255104.75      3632166.70     10255218.48
      3632185.65     10255417.03      3632004.69     10255392.56
      3631936.76     10255611.64      3631253.29     10255705.11
      3631072.70     10255812.10      3630976.49     10256030.32
      3630754.47     10256060.60      3630685.72     10255869.97
      3630558.90     10256168.07      3630212.11     10256161.64

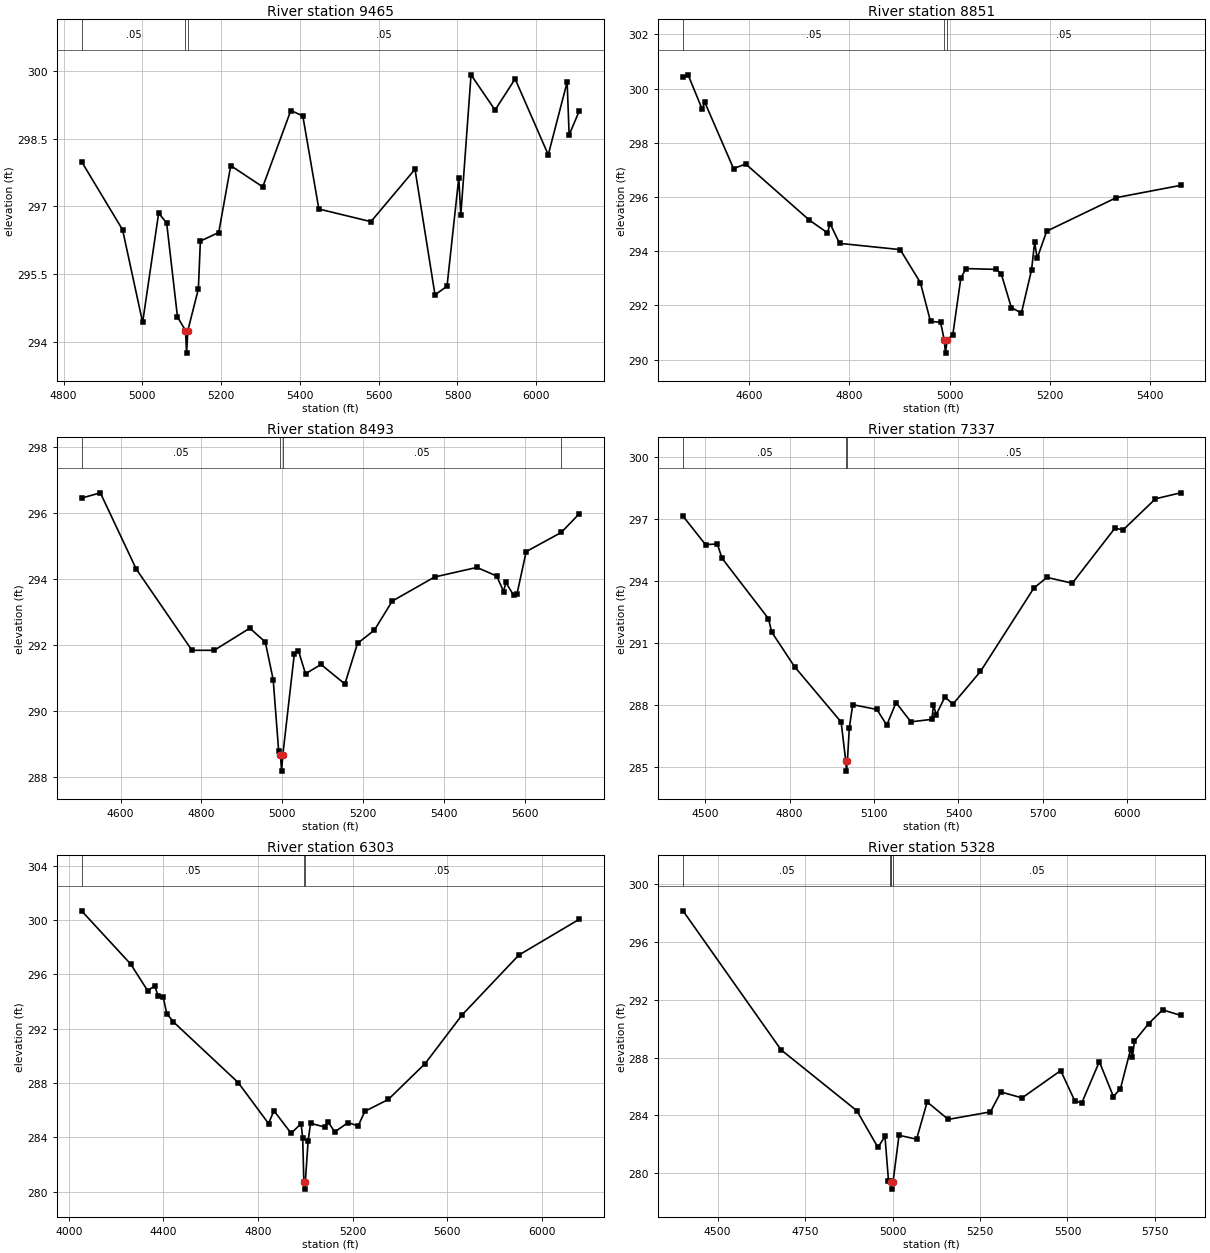
Type RM Length L Ch R = 1,9465,614,614,614
BEGIN DESCRIPTION:
UNT0481 IN WICK 18.0
END DESCRIPTION:
XS GIS Cut Line= 2
      3635692.53     10253459.14      3635921.70     10254701.38
#Sta/Elev= 30
  4845.5  297.99  4949.7  296.48  5000.6  294.43  5041.3  296.85  5061.6  296.63
  5089.1  294.55  5109.4  294.25  5112.2  293.75  5115.4  294.25  5142.1  295.17
  5147.2  296.23  5193.8  296.42  5224.3  297.90  5305.6  297.43  5376.8  299.12
  5407.3  299.00  5448.0  296.94  5580.2  296.66  5692.1  297.82  5742.9  295.04
  5773.4  295.23  5803.3  297.63  5808.4  296.80  5834.4  299.91  5895.4  299.13
  5946.3  299.82  6030.5  298.14  6078.4  299.75  6083.5  298.58  6108.7  299.10
#Mann=3,-1,0
  4845.5    0.05       0  5109.4    0.03       0  5115.4    0.05       0
Bank Sta=5109.4,5115.4
Exp/Cntr=0.3,0.1

Type RM Length L Ch R = 1,8851,358,358,358
BEGIN DESCRIPTION:
UNT0481 IN WICK 16.0
END DESCRIPTION:
XS GIS Cut Line= 2
      3635342.10     10253491.60      3635462.17     10254476.71
#Sta/Elev= 30
  4468.4  300.43  4478.5  300.51  4506.7  299.24  4511.8  299.50  4569.2  297.05
  4593.4  297.22  4720.3  295.15  4756.6  294.68  4761.7  295.02  4780.7  294.29
  4901.6  294.06  4941.9  292.84  4962.1  291.41  4982.2  291.38  4989.3  290.74
  4992.0  290.24  4995.3  290.74  5006.5  290.91  5022.5  293.00  5032.6  293.36
  5093.2  293.33  5103.1  293.17  5123.3  291.92  5143.4  291.72  5163.6  293.31
  5169.8  294.33  5174.8  293.74  5193.8  294.74  5333.0  295.98  5460.8  296.43
#Mann=3,-1,0
  4468.4    0.05       0  4989.3    0.03       0  4995.3    0.05       0
Bank Sta=4989.3,4995.3
Exp/Cntr=0.3,0.1

Type RM Length L Ch R = 1,8493,1156,1156,1156
BEGIN DESCRIPTION:
UNT0481 IN WICK 15.0
END DESCRIPTION:
XS GIS Cut Line= 2
      3634918.44     10253557.04      3635269.86     10254737.12
#Sta/Elev= 30
  4503.3  296.46  4549.8  296.62  4638.7  294.31  4776.6  291.85  4831.6  291.85
  4919.7  292.52  4958.1  292.10  4977.6  290.96  4991.2  288.79  4995.5  288.69
  4998.3  288.19  5001.5  288.69  5029.8  291.73  5040.2  291.83  5057.6  291.14
  5096.0  291.42  5155.0  290.83  5186.3  292.06  5228.0  292.46  5272.2  293.34
  5377.0  294.07  5481.7  294.36  5530.6  294.10  5548.0  293.63  5553.2  293.91
  5572.4  293.52  5581.2  293.57  5603.7  294.84  5690.6  295.42  5734.6  295.98
#Mann=4,-1,0
  4503.3    0.05       0  4995.5    0.03       0  5001.5    0.05       0
  5690.6    0.16       0
Bank Sta=4995.5,5001.5
Exp/Cntr=0.3,0.1

Type RM Length L Ch R = 1,7337,1034,1034,1034
BEGIN DESCRIPTION:
UNT0481 IN WICK 14.0
END DESCRIPTION:
XS GIS Cut Line= 3
      3634142.11     10253491.67      3634242.11     10254041.64
      3634742.11     10255141.64
#Sta/Elev= 30
  4421.6  297.14  4501.6  295.76  4543.5  295.79  4560.1  295.10  4725.2  292.17
  4736.7  291.52  4818.0  289.84  4983.3  287.16  4999.6  285.28  5002.3  284.78
  5005.6  285.28  5012.4  286.89  5024.5  288.00  5110.2  287.77  5145.4  287.01
  5178.3  288.10  5231.0  287.17  5305.7  287.29  5311.2  287.98  5321.1  287.52
  5351.9  288.37  5380.4  288.03  5478.2  289.61  5668.2  293.66  5714.4  294.17
  5804.4  293.89  5956.0  296.56  5984.6  296.47  6099.9  297.98  6188.9  298.27
#Mann=3,-1,0
  4421.6    0.05       0  4999.6    0.03       0  5005.6    0.05       0
Bank Sta=4999.6,5005.6
Exp/Cntr=0.3,0.1

Type RM Length L Ch R = 1,6303,975,975,975
BEGIN DESCRIPTION:
UNT0481 IN WICK 12.0
END DESCRIPTION:
XS GIS Cut Line= 3
      3632992.14     10254041.67      3633792.11     10254591.64
      3634592.14     10255391.68
#Sta/Elev= 30
  4054.0  300.68  4261.6  296.76  4333.3  294.80  4363.1  295.15  4378.0  294.41
  4399.0  294.33  4413.9  293.12  4442.3  292.50  4715.6  288.04  4844.1  285.02
  4867.0  285.96  4939.6  284.30  4981.5  285.01  4988.4  283.96  4993.4  280.69
  4996.1  280.19  4999.4  280.69  5011.3  283.74  5021.7  285.04  5081.3  284.76
  5095.5  285.15  5123.8  284.40  5180.3  285.09  5222.8  284.84  5251.1  285.92
  5350.0  286.79  5505.6  289.43  5661.2  293.00  5901.6  297.42  6156.2  300.05
#Mann=3,-1,0
  4054.0    0.05       0  4993.4    0.03       0  4999.4    0.05       0
Bank Sta=4993.4,4999.4
Exp/Cntr=0.3,0.1

Type RM Length L Ch R = 1,5328,1195,1195,1195
BEGIN DESCRIPTION:
UNT0481 IN WICK 10.0
END DESCRIPTION:
XS GIS Cut Line= 3
      3633021.74     10254342.67      3633334.25     10254551.00
      3633429.73     10255592.65
#Sta/Elev= 30
  4401.4  298.17  4681.6  288.54  4898.1  284.32  4958.4  281.78  4978.5  282.54
  4988.5  279.48  4992.2  279.43  4995.2  279.39  4995.5  279.39  4998.3  278.89
  5001.5  279.39  5018.6  282.62  5068.8  282.35  5099.0  284.93  5159.2  283.72
  5279.7  284.24  5309.8  285.62  5370.1  285.21  5480.6  287.10  5520.7  285.01
  5540.8  284.86  5591.0  287.72  5631.2  285.30  5651.3  285.85  5680.5  288.59
  5685.6  288.05  5691.4  289.14  5731.6  290.35  5771.8  291.31  5823.0  290.93
#Mann=5,-1,0
  4401.4    0.05       0  4992.2    0.16       0  4995.2    0.05       0
  4995.5    0.03       0  5001.5    0.05       0
Bank Sta=4995.5,5001.5
Exp/Cntr=0.3,0.1

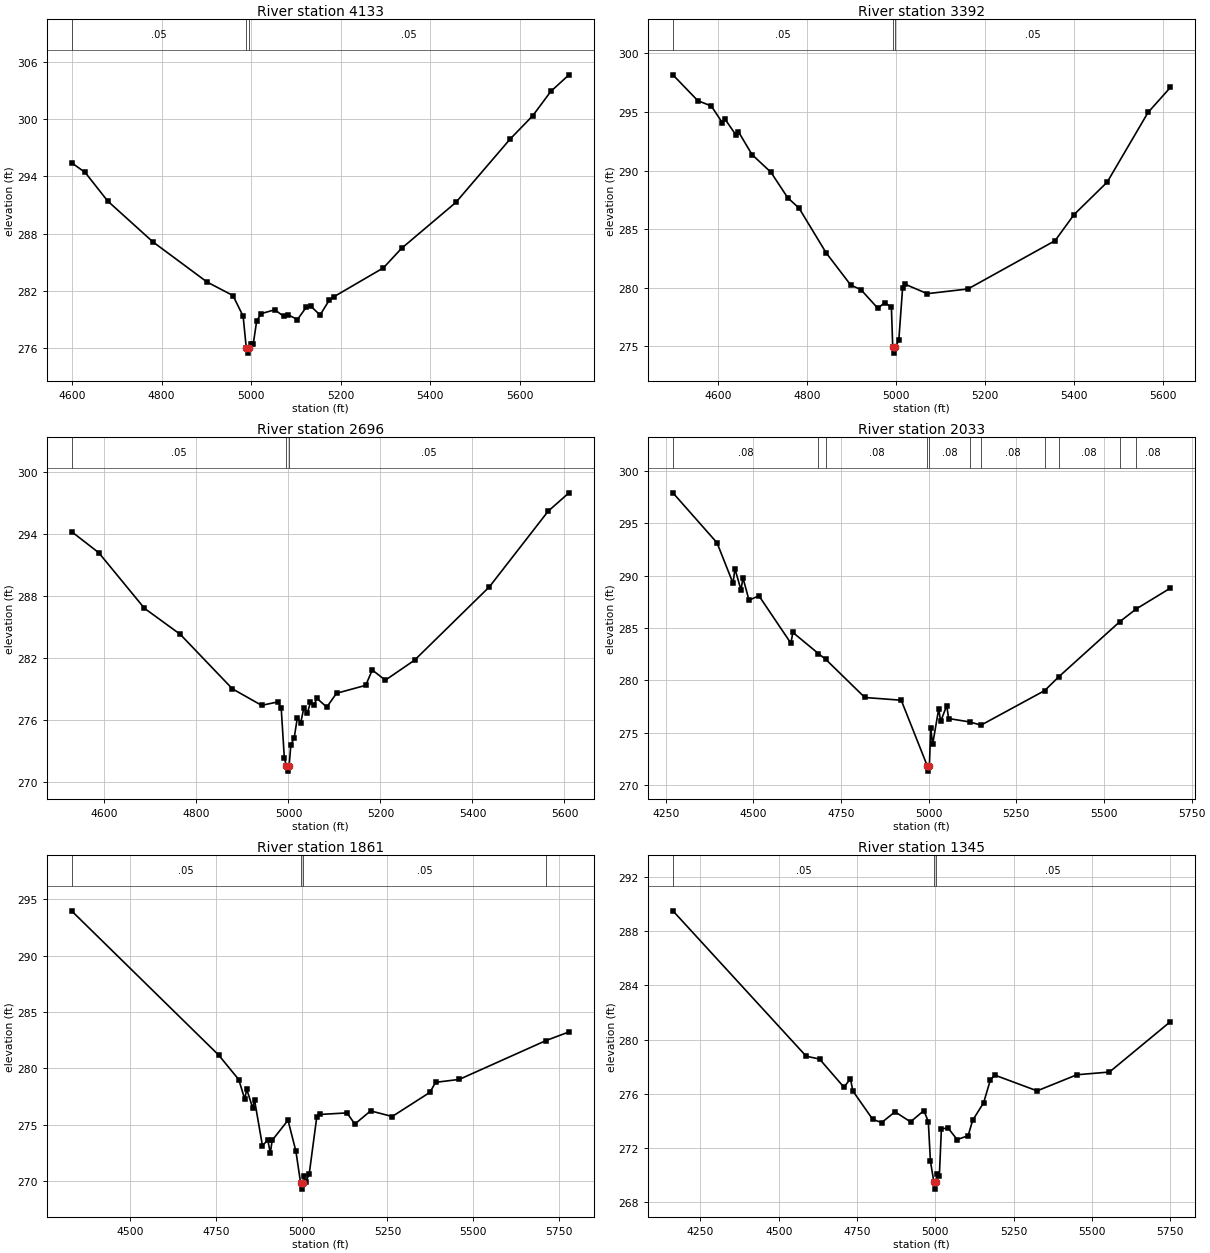
Type RM Length L Ch R = 1,4133,741,741,741
BEGIN DESCRIPTION:
UNT0481 IN WICK 8.0
END DESCRIPTION:
XS GIS Cut Line= 3
      3632692.10     10254691.60      3632742.11     10255091.64
      3632842.11     10255791.68
#Sta/Elev= 30
  4599.0  295.42  4629.3  294.41  4679.7  291.41  4780.4  287.14  4901.4  282.93
  4959.3  281.51  4982.0  279.35  4989.1  275.98  4991.8  275.48  4995.1  275.98
  4999.6  276.47  5004.7  276.47  5012.3  278.86  5022.4  279.62  5052.7  280.02
  5072.9  279.32  5083.0  279.48  5103.2  279.00  5123.4  280.32  5133.5  280.38
  5153.7  279.47  5173.9  281.00  5184.0  281.37  5295.1  284.41  5335.5  286.45
  5456.7  291.26  5577.9  297.90  5628.5  300.35  5668.9  302.90  5709.3  304.63
#Mann=3,-1,0
  4599.0    0.05       0  4989.1    0.03       0  4995.1    0.05       0
Bank Sta=4989.1,4995.1
Exp/Cntr=0.3,0.1

Type RM Length L Ch R = 1,3392,696,696,696
BEGIN DESCRIPTION:
UNT0481 IN WICK 6.0
END DESCRIPTION:
XS GIS Cut Line= 2
      3632127.64     10254724.59      3632513.95     10255775.00
#Sta/Elev= 30
  4497.6  298.16  4553.5  295.96  4584.0  295.50  4609.1  294.06  4614.5  294.40
  4639.6  293.02  4644.9  293.32  4675.6  291.36  4718.2  289.85  4756.1  287.67
  4781.3  286.80  4842.2  282.99  4897.8  280.23  4920.7  279.84  4958.8  278.25
  4973.9  278.73  4989.2  278.35  4992.2  274.93  4995.0  274.43  4998.2  274.93
  5005.9  275.55  5014.4  279.99  5019.7  280.31  5069.8  279.50  5161.4  279.90
  5357.5  284.02  5400.1  286.24  5474.7  289.01  5566.6  294.95  5616.8  297.08
#Mann=3,-1,0
  4497.6    0.05       0  4992.2    0.03       0  4998.2    0.05       0
Bank Sta=4992.2,4998.2
Exp/Cntr=0.3,0.1

Type RM Length L Ch R = 1,2696,663,663,663
BEGIN DESCRIPTION:
UNT0481 IN WICK 5.0
END DESCRIPTION:
XS GIS Cut Line= 2
      3631648.17     10255101.90      3632377.25     10255900.42
#Sta/Elev= 30
  4528.5  294.24  4587.7  292.19  4687.0  286.80  4764.7  284.28  4878.2  278.99
  4941.7  277.39  4976.8  277.72  4984.2  277.17  4991.0  272.33  4995.4  271.51
  4998.2  271.01  5001.4  271.51  5005.2  273.54  5012.6  274.26  5019.4  276.20
  5026.8  275.72  5033.6  277.16  5041.0  276.62  5047.8  277.68  5055.2  277.38
  5061.9  278.07  5083.3  277.22  5104.5  278.56  5168.0  279.33  5182.2  280.82
  5210.6  279.83  5274.1  281.77  5436.9  288.89  5564.6  296.22  5609.8  298.00
#Mann=3,-1,0
  4528.5    0.05       0  4995.4    0.03       0  5001.4    0.05       0
Bank Sta=4995.4,5001.4
Exp/Cntr=0.3,0.1

Type RM Length L Ch R = 1,2033,172,172,172
BEGIN DESCRIPTION:
UNT0481 IN WICK 4.0
END DESCRIPTION:
XS GIS Cut Line= 2
      3631203.73     10255032.45      3631807.39     10256316.09
#Sta/Elev= 30
  4270.7  297.91  4396.5  293.14  4442.1  289.28  4447.6  290.66  4464.9  288.63
  4470.4  289.80  4487.7  287.66  4516.0  288.08  4607.2  283.55  4612.8  284.58
  4685.4  282.57  4706.9  282.00  4818.0  278.37  4921.8  278.11  4996.1  271.84
  4998.9  271.34  5002.1  271.84  5005.9  275.46  5011.4  273.90  5028.7  277.29
  5034.2  276.08  5051.5  277.60  5057.0  276.36  5116.6  276.04  5149.3  275.73
  5330.9  279.03  5370.5  280.33  5545.1  285.61  5591.7  286.82  5689.2  288.81
#Mann=11,-1,0
  4270.7    0.08       0  4685.4    0.05       0  4706.9    0.08       0
  4996.1    0.07       0  5002.1    0.08       0  5116.6    0.05       0
  5149.3    0.08       0  5330.9    0.05       0  5370.5    0.08       0
  5545.1    0.05       0  5591.7    0.08       0
Bank Sta=4996.1,5002.1
Exp/Cntr=0.3,0.1

Type RM Length L Ch R = 1,1861,516,516,516
BEGIN DESCRIPTION:
UNT0481 IN WICK 3.0
END DESCRIPTION:
XS GIS Cut Line= 2
      3631064.86     10255081.10      3631669.04     10256400.56
#Sta/Elev= 30
  4328.5  293.97  4758.0  281.17  4816.4  279.00  4833.9  277.26  4839.4  278.17
  4856.9  276.49  4862.4  277.19  4885.4  273.14  4901.0  273.65  4908.4  272.49
  4913.9  273.62  4960.0  275.40  4983.0  272.66  4997.0  269.79  4999.7  269.29
  5003.0  269.79  5006.0  270.49  5011.5  269.89  5022.0  270.66  5044.0  275.71
  5052.0  275.91  5132.0  276.05  5155.0  275.06  5201.0  276.23  5264.0  275.73
  5373.9  277.87  5390.6  278.76  5459.6  279.02  5713.0  282.47  5779.7  283.23
#Mann=4,-1,0
  4328.5    0.05       0  4997.0    0.04       0  5003.0    0.05       0
  5713.0    0.08       0
Bank Sta=4997,5003
Exp/Cntr=0.3,0.1

Type RM Length L Ch R = 1,1345,756,756,756
BEGIN DESCRIPTION:
UNT0481 IN WICK 2.0
END DESCRIPTION:
XS GIS Cut Line= 4
      3630717.64     10255261.69      3630717.64     10255615.81
      3631363.47     10256344.98      3631606.56     10256435.27
#Sta/Elev= 30
  4162.4  289.51  4587.8  278.77  4630.4  278.56  4708.2  276.48  4729.1  277.10
  4736.7  276.20  4800.2  274.10  4828.7  273.87  4871.3  274.66  4920.7  273.92
  4963.3  274.75  4977.5  273.94  4984.2  271.02  4995.4  269.45  4998.2  268.95
  5001.4  269.45  5005.2  270.04  5012.7  269.92  5019.3  273.42  5041.1  273.45
  5069.5  272.61  5104.7  272.90  5118.9  274.03  5154.0  275.33  5175.8  277.04
  5190.0  277.37  5324.7  276.21  5451.8  277.40  5555.6  277.60  5749.9  281.32
#Mann=3,-1,0
  4162.4    0.05       0  4995.4    0.03       0  5001.4    0.05       0
Bank Sta=4995.4,5001.4
Exp/Cntr=0.3,0.1

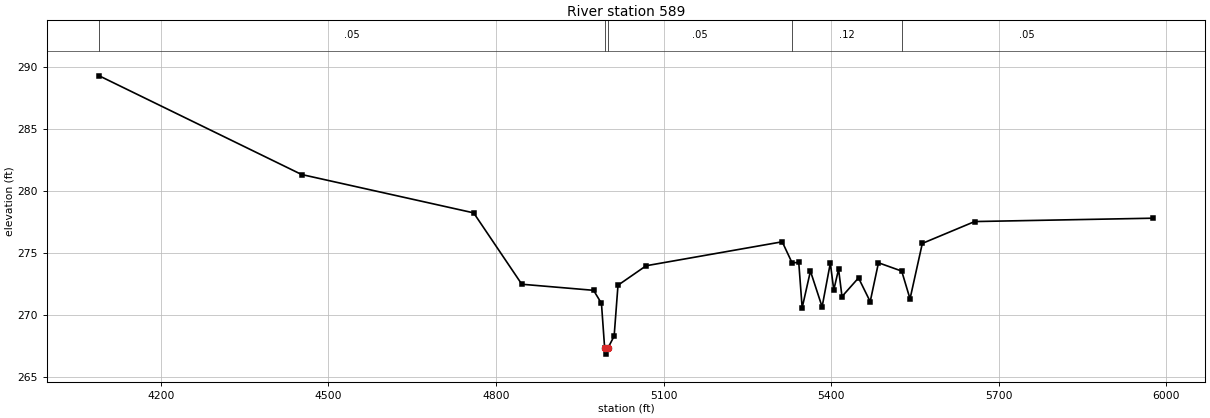
Type RM Length L Ch R = 1,589,0,0,0
BEGIN DESCRIPTION:
UNT0481 IN WICK 1.0
END DESCRIPTION:
XS GIS Cut Line= 3
      3630155.14     10255338.03      3630196.80     10255699.15
      3631438.51     10256580.13
#Sta/Elev= 30
  4089.6  289.30  4451.9  281.35  4759.9  278.26  4846.1  272.51  4974.6  272.02
  4988.7  270.97  4994.4  267.38  4997.1  266.88  5000.4  267.38  5011.4  268.33
  5018.3  272.43  5068.7  274.00  5312.3  275.93  5330.0  274.23  5341.9  274.27
  5348.0  270.61  5362.8  273.57  5383.7  270.69  5398.4  274.21  5404.6  272.05
  5413.2  273.72  5419.3  271.52  5448.9  273.02  5469.8  271.11  5484.6  274.24
  5526.2  273.57  5541.1  271.33  5563.1  275.80  5656.8  277.56  5975.6  277.83
#Mann=5,-1,0
  4089.6    0.05       0  4994.4    0.03       0  5000.4    0.05       0
  5330.0    0.12       0  5526.2    0.05       0
Bank Sta=4994.4,5000.4
Exp/Cntr=0.3,0.1

Chan Stop Cuts=-1