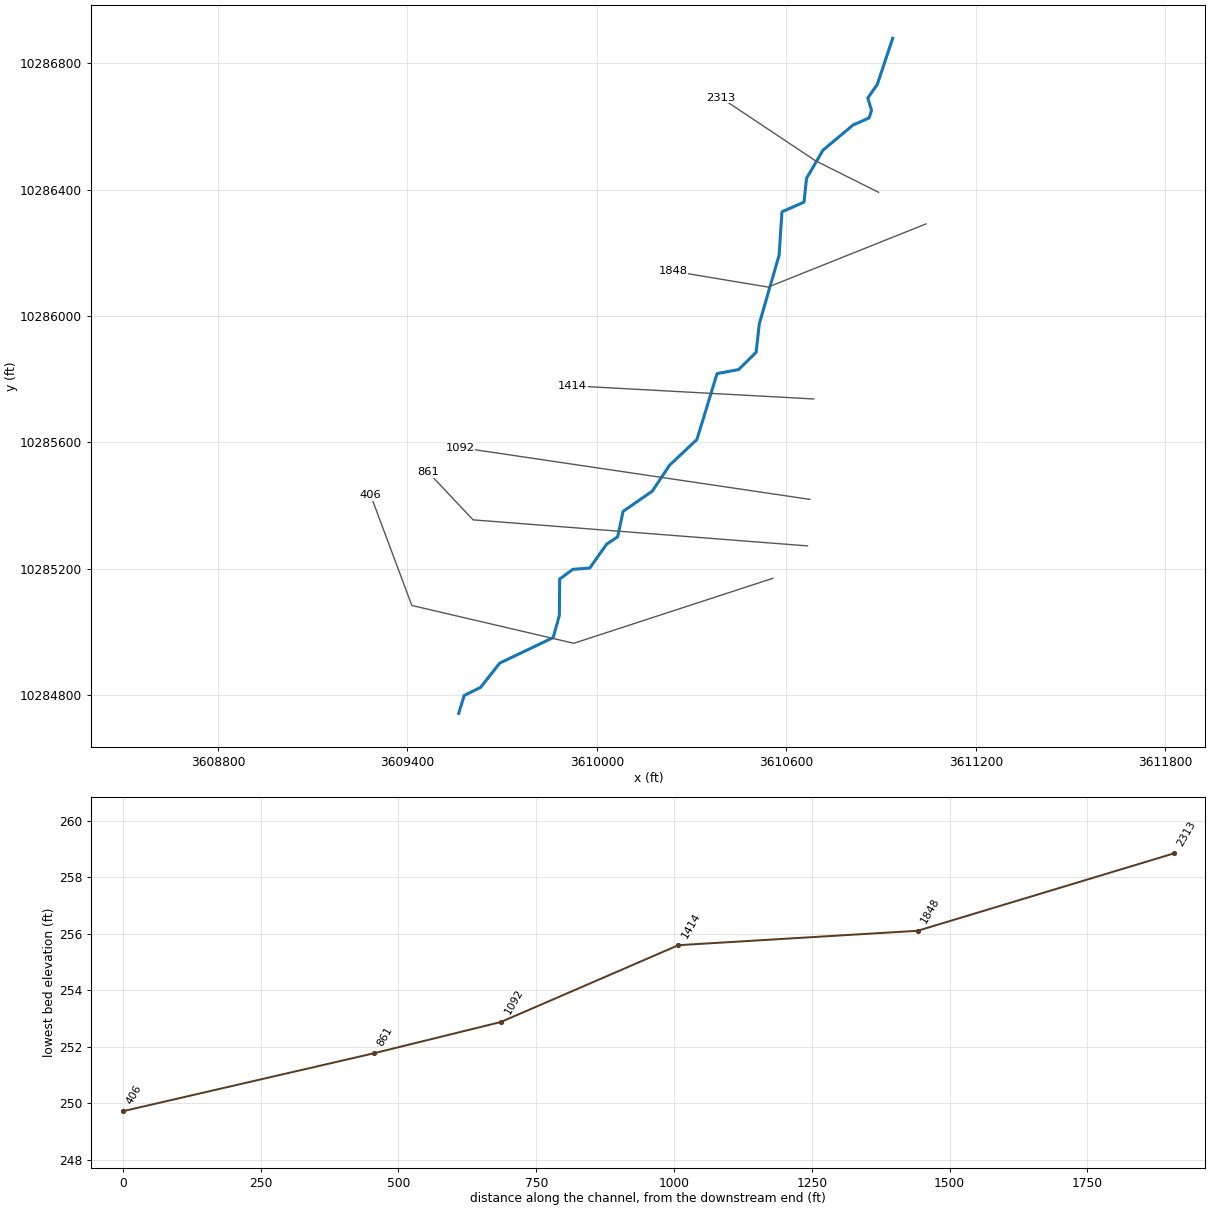
--- UNT04824 IN WICK.prj (project) ---

Proj Title=UNT04824 IN WICK Base Level Engineering
Current Plan=p01
Default Exp/Contr=0.3,0.1
English Units
Geom File=g01
Flow File=f01
Plan File=p01
BEGIN DESCRIPTION:
UNT04824 IN WICK
END DESCRIPTION:

--- UNT04824 IN WICK.p01 (plan) ---

Plan Title=Multiple Run
Short Identifier=Multiple
Geom File=g01
Flow File=f01
Subcritical Flow
K Sum by GR= 0
Std Step Tol= 0.01
Critical Tol= 0.01
Num of Std Step Trials= 20
Max Error Tol= 0.3
Flow Tol Ratio= 0.001
Split Flow NTrial= 30
Split Flow Tol= 0.02
Split Flow Ratio= 0.02
Log Output Level= 0
Friction Slope Method= 1
Unsteady Friction Slope Method= 2
Unsteady Bridges Friction Slope Method= 1
Parabolic Critical Depth
Global Vel Dist=  1 , 1 , 1
Global Log Level= 0
CheckData=True
Encroach Param= -1, 0, 0, 0
BEGIN DESCRIPTION:
Multiple Run
END DESCRIPTION:

--- UNT04824 IN WICK.f01 (steady flow) ---

Flow Title=Multiple
Number of Profiles=7
Profile Names=10-year,25-year,50-year,1pct_min,100-year,1pct_plu,500-year
River Rch & RM= UNT04824 IN WICK,Reach-1,2313
     295     378     442     380     513     694     693
Boundary for River Rch & Prof#=UNT04824 IN WICK,Reach-1,1
Up Type=0
Dn Type=3
Dn Slope=0.005
Boundary for River Rch & Prof#=UNT04824 IN WICK,Reach-1,2
Up Type=0
Dn Type=3
Dn Slope=0.005
Boundary for River Rch & Prof#=UNT04824 IN WICK,Reach-1,3
Up Type=0
Dn Type=3
Dn Slope=0.005
Boundary for River Rch & Prof#=UNT04824 IN WICK,Reach-1,4
Up Type=0
Dn Type=3
Dn Slope=0.005
Boundary for River Rch & Prof#=UNT04824 IN WICK,Reach-1,5
Up Type=0
Dn Type=3
Dn Slope=0.005
Boundary for River Rch & Prof#=UNT04824 IN WICK,Reach-1,6
Up Type=0
Dn Type=3
Dn Slope=0.005
Boundary for River Rch & Prof#=UNT04824 IN WICK,Reach-1,7
Up Type=0
Dn Type=3
Dn Slope=0.005

--- UNT04824 IN WICK.g01 (geometry) ---

Geom Title=Existing Conditions

River Reach=UNT04824 IN WICK,Reach-1
Reach XY= 30
      3610936.58     10286879.33      3610887.72     10286733.30
      3610857.81     10286690.50      3610869.44     10286651.19
      3610861.92     10286627.20      3610811.34     10286605.01
      3610715.61     10286525.02      3610663.69     10286435.85
      3610655.75     10286360.54      3610585.92     10286330.09
      3610576.89     10286192.74      3610514.23     10285975.76
      3610504.02     10285884.96      3610448.75     10285830.45
      3610380.36     10285817.59      3610316.60     10285608.94
      3610229.96     10285527.44      3610175.19     10285445.33
      3610082.74     10285381.36      3610065.64     10285300.91
      3610030.40     10285277.12      3609977.14     10285201.80
      3609923.55     10285197.74      3609881.97     10285166.98
      3609880.97     10285052.06      3609861.56     10284981.80
      3609692.29     10284900.86      3609631.31     10284823.74
      3609579.65     10284798.41      3609562.11     10284741.64

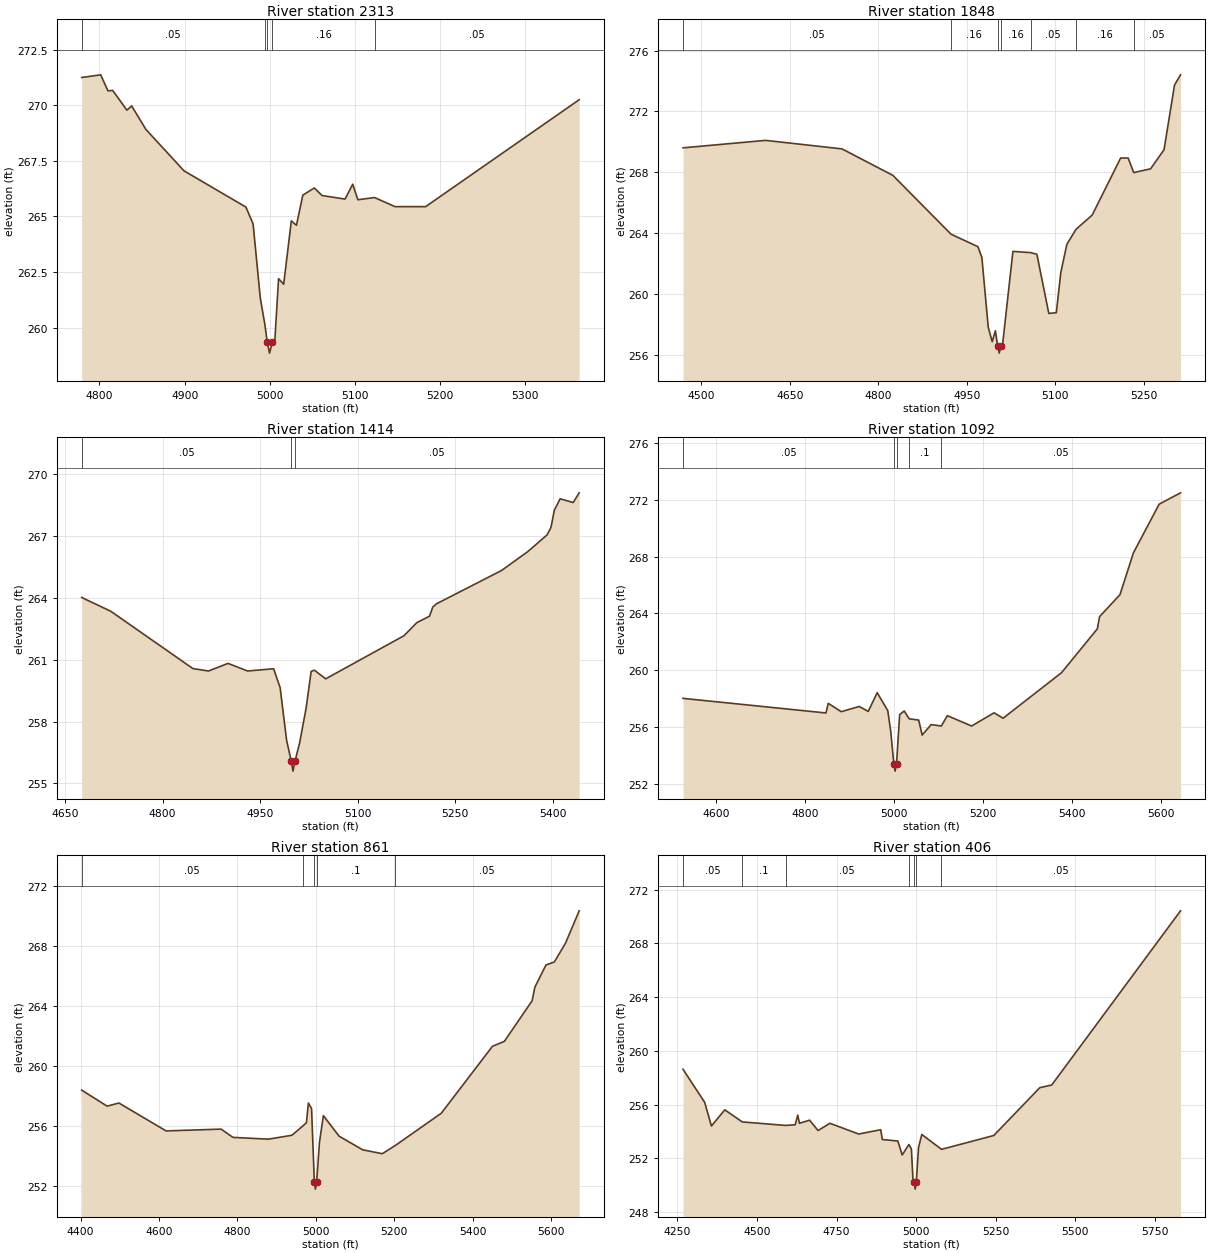
Type RM Length L Ch R = 1,2313,465,465,465
BEGIN DESCRIPTION:
UNT04824 IN WICK 4.0
END DESCRIPTION:
XS GIS Cut Line= 3
      3610892.14     10286391.62      3610692.11     10286491.64
      3610392.11     10286691.64
#Sta/Elev= 30
  4779.1  271.25  4801.5  271.37  4809.9  270.65  4815.5  270.67  4832.2  269.78
  4837.8  269.97  4854.6  268.91  4899.3  267.05  4972.0  265.42  4980.4  264.66
  4988.8  261.34  4994.3  260.12  4997.0  259.35  4999.7  258.85  5003.0  259.35
  5005.8  259.35  5010.3  262.20  5016.3  261.95  5025.3  264.80  5031.3  264.60
  5038.8  265.96  5052.3  266.28  5061.3  265.94  5088.4  265.78  5097.4  266.45
  5103.4  265.75  5123.0  265.85  5147.0  265.44  5183.0  265.44  5363.3  270.25
#Mann=5,-1,0
  4779.1    0.05       0  4994.3    0.16       0  4997.0    0.07       0
  5003.0    0.16       0  5123.0    0.05       0
Bank Sta=4997,5003
Exp/Cntr=0.3,0.1

Type RM Length L Ch R = 1,1848,434,434,434
BEGIN DESCRIPTION:
UNT04824 IN WICK 3.0
END DESCRIPTION:
XS GIS Cut Line= 3
      3611042.13     10286291.65      3610542.11     10286091.64
      3610242.08     10286141.65
#Sta/Elev= 30
  4469.3  269.61  4609.3  270.10  4738.6  269.54  4824.7  267.80  4923.3  263.93
  4968.8  263.11  4975.5  262.40  4986.3  257.81  4993.0  256.86  4998.4  257.58
  5002.1  256.61  5004.9  256.11  5008.1  256.61  5010.4  256.61  5028.1  262.80
  5057.9  262.72  5068.7  262.61  5088.9  258.72  5101.6  258.77  5109.2  261.40
  5119.4  263.26  5134.9  264.25  5162.4  265.19  5210.6  268.94  5223.3  268.94
  5232.7  267.98  5261.3  268.23  5284.1  269.49  5301.8  273.74  5312.0  274.41
#Mann=7,-1,0
  4469.3    0.05       0  4923.3    0.16       0  5002.1    0.07       0
  5008.1    0.16       0  5057.9    0.05       0  5134.9    0.16       0
  5232.7    0.05       0
Bank Sta=5002.1,5008.1
Exp/Cntr=0.3,0.1

Type RM Length L Ch R = 1,1414,322,322,322
BEGIN DESCRIPTION:
UNT04824 IN WICK 2.0
END DESCRIPTION:
XS GIS Cut Line= 2
      3610686.84     10285737.28      3609922.88     10285778.95
#Sta/Elev= 30
  4675.5  264.03  4720.3  263.36  4846.5  260.58  4870.5  260.46  4900.6  260.83
  4930.6  260.46  4970.7  260.57  4980.7  259.65  4990.7  257.09  4997.7  256.10
  5000.5  255.60  5003.7  256.10  5010.7  256.97  5020.7  258.67  5028.4  260.44
  5033.4  260.50  5050.8  260.08  5171.0  262.17  5191.0  262.81  5210.4  263.12
  5215.4  263.56  5221.0  263.72  5321.2  265.34  5361.3  266.25  5391.3  267.07
  5397.3  267.44  5402.3  268.26  5411.3  268.82  5431.4  268.64  5440.6  269.11
#Mann=3,-1,0
  4675.5    0.05       0  4997.7    0.03       0  5003.7    0.05       0
Bank Sta=4997.7,5003.7
Exp/Cntr=0.3,0.1

Type RM Length L Ch R = 1,1092,231,231,231
BEGIN DESCRIPTION:
Mapping XS a8874057
END DESCRIPTION:
XS GIS Cut Line= 2
      3610674.08     10285419.34      3609567.37     10285583.39
#Sta/Elev= 30
  4524.7  258.01  4846.2  256.98  4851.3  257.66  4880.5  257.07  4921.0  257.44
  4941.2  257.09  4961.4  258.41  4985.2  257.14  4991.7  255.72  4998.8  253.38
  5001.6  252.88  5004.8  253.38  5011.9  256.86  5022.1  257.12  5033.2  256.57
  5054.7  256.48  5062.5  255.42  5082.7  256.16  5105.6  256.06  5119.1  256.79
  5173.7  256.06  5224.2  256.99  5244.5  256.61  5375.9  259.82  5456.4  262.91
  5461.4  263.77  5507.3  265.32  5537.6  268.27  5595.4  271.70  5643.5  272.50
#Mann=5,-1,0
  4524.7    0.05       0  4998.8    0.03       0  5004.8    0.05       0
  5033.2     0.1       0  5105.6    0.05       0
Bank Sta=4998.8,5004.8
Exp/Cntr=0.3,0.1

Type RM Length L Ch R = 1,861,455,455,455
BEGIN DESCRIPTION:
Mapping XS b597dccc
END DESCRIPTION:
XS GIS Cut Line= 3
      3610666.83     10285271.99      3609607.83     10285354.45
      3609465.83     10285505.05
#Sta/Elev= 30
  4402.7  258.37  4467.7  257.30  4497.7  257.51  4618.1  255.65  4758.5  255.77
  4788.6  255.22  4878.9  255.10  4939.0  255.36  4966.6  255.97  4976.0  256.20
  4981.1  257.51  4989.2  257.13  4996.2  252.27  4999.0  251.77  5002.2  252.27
  5009.3  254.88  5019.3  256.67  5059.4  255.30  5119.6  254.39  5169.7  254.13
  5202.9  254.68  5320.2  256.83  5450.6  261.29  5481.1  261.62  5551.9  264.33
  5558.8  265.23  5587.1  266.71  5608.5  266.91  5636.9  268.16  5671.9  270.32
#Mann=5,-1,0
  4402.7    0.05       0  4966.6     0.1       0  4996.2    0.07       0
  5002.2     0.1       0  5202.9    0.05       0
Bank Sta=4996.2,5002.2
Exp/Cntr=0.3,0.1

Type RM Length L Ch R = 1,406,0,0,0
BEGIN DESCRIPTION:
UNT04824 IN WICK 1.0
END DESCRIPTION:
XS GIS Cut Line= 4
      3610556.94     10285169.34      3609926.72     10284963.60
      3609413.70     10285083.40      3609283.50     10285432.33
#Sta/Elev= 30
  4267.9  258.64  4335.9  256.18  4357.1  254.42  4399.2  255.62  4454.1  254.72
  4590.4  254.46  4620.1  254.51  4628.2  255.23  4633.5  254.62  4665.4  254.85
  4692.0  254.08  4729.1  254.62  4819.6  253.82  4888.6  254.14  4893.9  253.41
  4942.5  253.30  4956.1  252.26  4977.1  253.04  4985.0  252.72  4990.1  250.37
  4994.2  250.22  4996.9  249.72  5000.2  250.22  5007.5  252.83  5017.7  253.79
  5079.5  252.68  5243.7  253.71  5388.3  257.27  5425.7  257.47  5830.1  270.43
#Mann=7,-1,0
  4267.9    0.05       0  4454.1     0.1       0  4590.4    0.05       0
  4977.1     0.1       0  4994.2    0.07       0  5000.2     0.1       0
  5079.5    0.05       0
Bank Sta=4994.2,5000.2
Exp/Cntr=0.3,0.1

Chan Stop Cuts=-1