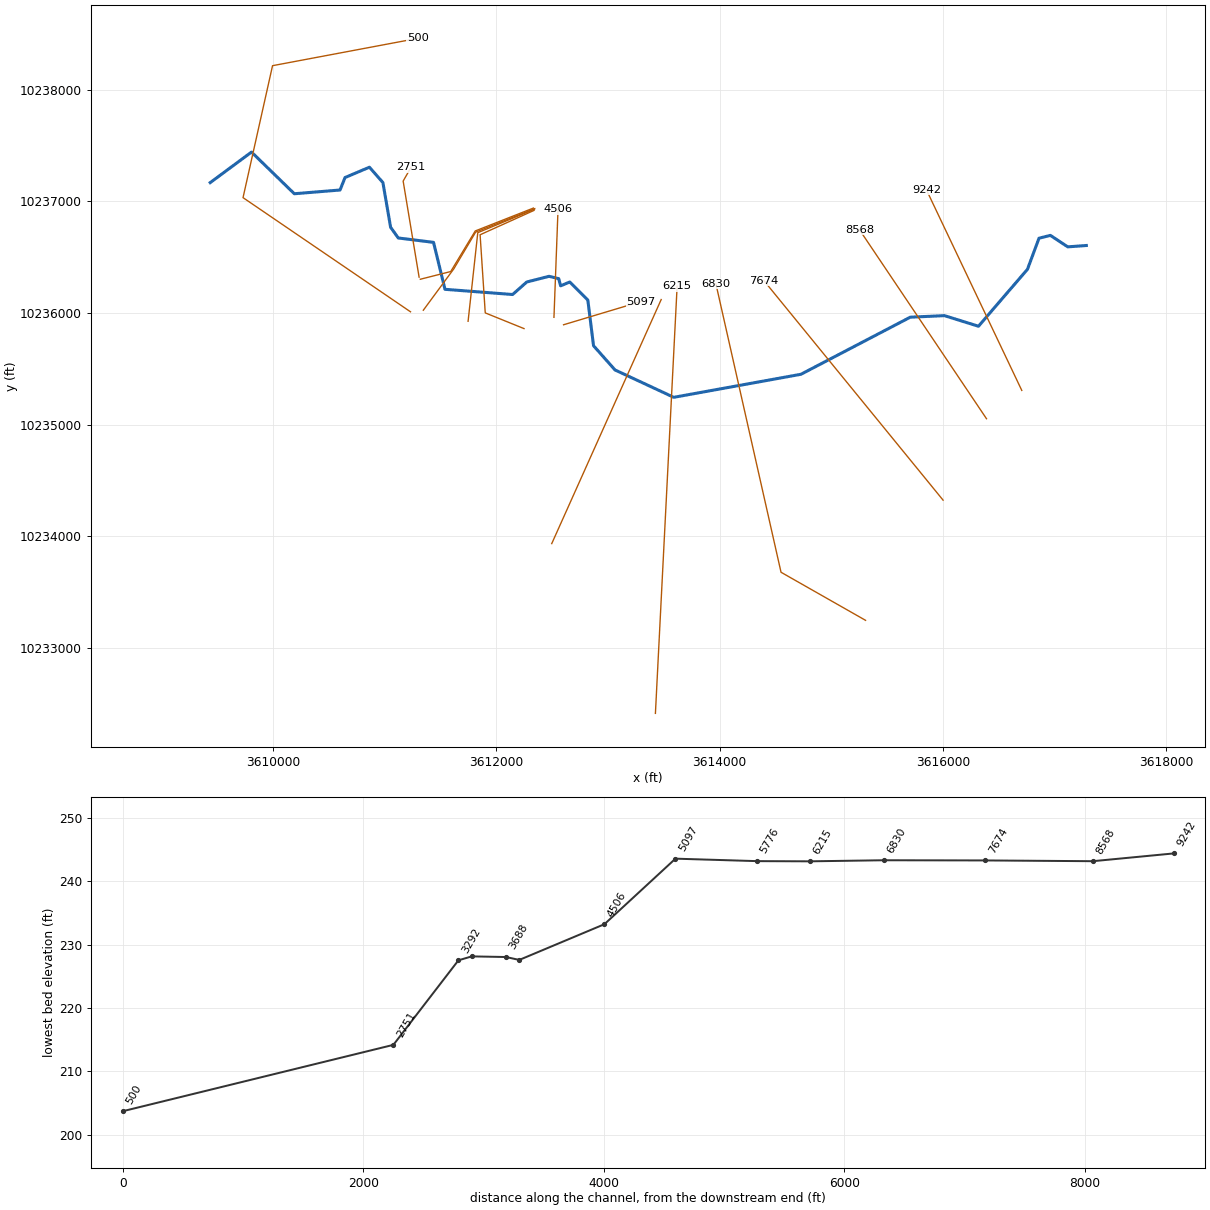
--- UNT0485 IN WICK.prj (project) ---

Proj Title=UNT0485 IN WICK Base Level Engineering
Current Plan=p01
Default Exp/Contr=0.3,0.1
English Units
Geom File=g01
Flow File=f01
Plan File=p01
Y Axis Title=Elevation
X Axis Title(PF)=Main Channel Distance
X Axis Title(XS)=Station
BEGIN DESCRIPTION:
UNT0485 IN WICK
END DESCRIPTION:
DSS Export Rating Curves= 0
DSS Export Rating Curve Sorted= 0
DSS Export Volume Flow Curves= 0
DXF OffsetX= 0
DXF OffsetY= 0
DXF ScaleX= 1
DXF ScaleY= 10

--- UNT0485 IN WICK.p01 (plan) ---

Plan Title=Multiple Run
Short Identifier=Multiple
Geom File=g01
Flow File=f01
Subcritical Flow
K Sum by GR= 0
Std Step Tol= 0.01
Critical Tol= 0.01
Num of Std Step Trials= 20
Max Error Tol= 0.3
Flow Tol Ratio= 0.001
Split Flow NTrial= 30
Split Flow Tol= 0.02
Split Flow Ratio= 0.02
Log Output Level= 0
Friction Slope Method= 1
Unsteady Friction Slope Method= 2
Unsteady Bridges Friction Slope Method= 1
Parabolic Critical Depth
Global Vel Dist=  1 , 1 , 1
Global Log Level= 0
CheckData=True
Encroach Param= -1, 0, 0, 0
BEGIN DESCRIPTION:
Multiple Run
END DESCRIPTION:

--- UNT0485 IN WICK.f01 (steady flow) ---

Flow Title=Multiple
Program Version=4.10
Number of Profiles= 7
Profile Names=10-year,25-year,50-year,1pct_min,100-year,1pct_plu,500-year
River Rch & RM=UNT0485 IN WICK,Reach-1         ,9242
     705     960    1171    1047    1417    1916    2075
River Rch & RM=UNT0485 IN WICK,Reach-1         ,4506
     940    1302    1605    1450    1961    2652    2931
Boundary for River Rch & Prof#=UNT0485 IN WICK,Reach-1         , 1
Up Type= 0
Dn Type= 3
Dn Slope=0.005
Boundary for River Rch & Prof#=UNT0485 IN WICK,Reach-1         , 2
Up Type= 0
Dn Type= 3
Dn Slope=0.005
Boundary for River Rch & Prof#=UNT0485 IN WICK,Reach-1         , 3
Up Type= 0
Dn Type= 3
Dn Slope=0.005
Boundary for River Rch & Prof#=UNT0485 IN WICK,Reach-1         , 4
Up Type= 0
Dn Type= 3
Dn Slope=0.005
Boundary for River Rch & Prof#=UNT0485 IN WICK,Reach-1         , 5
Up Type= 0
Dn Type= 3
Dn Slope=0.005
Boundary for River Rch & Prof#=UNT0485 IN WICK,Reach-1         , 6
Up Type= 0
Dn Type= 3
Dn Slope=0.005
Boundary for River Rch & Prof#=UNT0485 IN WICK,Reach-1         , 7
Up Type= 0
Dn Type= 3
Dn Slope=0.005
DSS Import GetInterval= 0
DSS Import GetPeak= 0
DSS Import FillOption= 0

--- UNT0485 IN WICK.g01 (geometry) ---

Geom Title=Existing Conditions
Program Version=4.10

River Reach=UNT0485 IN WICK ,Reach-1
Reach XY= 30
      3617285.54     10236605.04      3617119.01      10236592.9
      3616963.41      10236695.6      3616861.42     10236670.16
      3616758.34     10236392.38      3616319.31     10235881.85
      3616014.62     10235976.91      3615708.42     10235962.88
      3614729.43     10235451.65      3613590.54     10235245.37
       3613064.5     10235490.17      3612871.79     10235707.18
      3612820.76     10236116.11      3612659.03     10236277.89
      3612577.06      10236244.1       3612559.8     10236308.04
       3612473.4     10236328.98      3612273.58     10236278.08
      3612147.17     10236166.09      3611541.32     10236212.57
      3611438.74     10236633.12      3611122.88     10236672.34
      3611054.33     10236768.41      3610985.23      10237168.8
      3610864.71     10237306.31       3610646.2     10237213.56
      3610601.54     10237102.03      3610191.98     10237068.55
      3609808.48     10237441.69      3609438.75     10237168.26

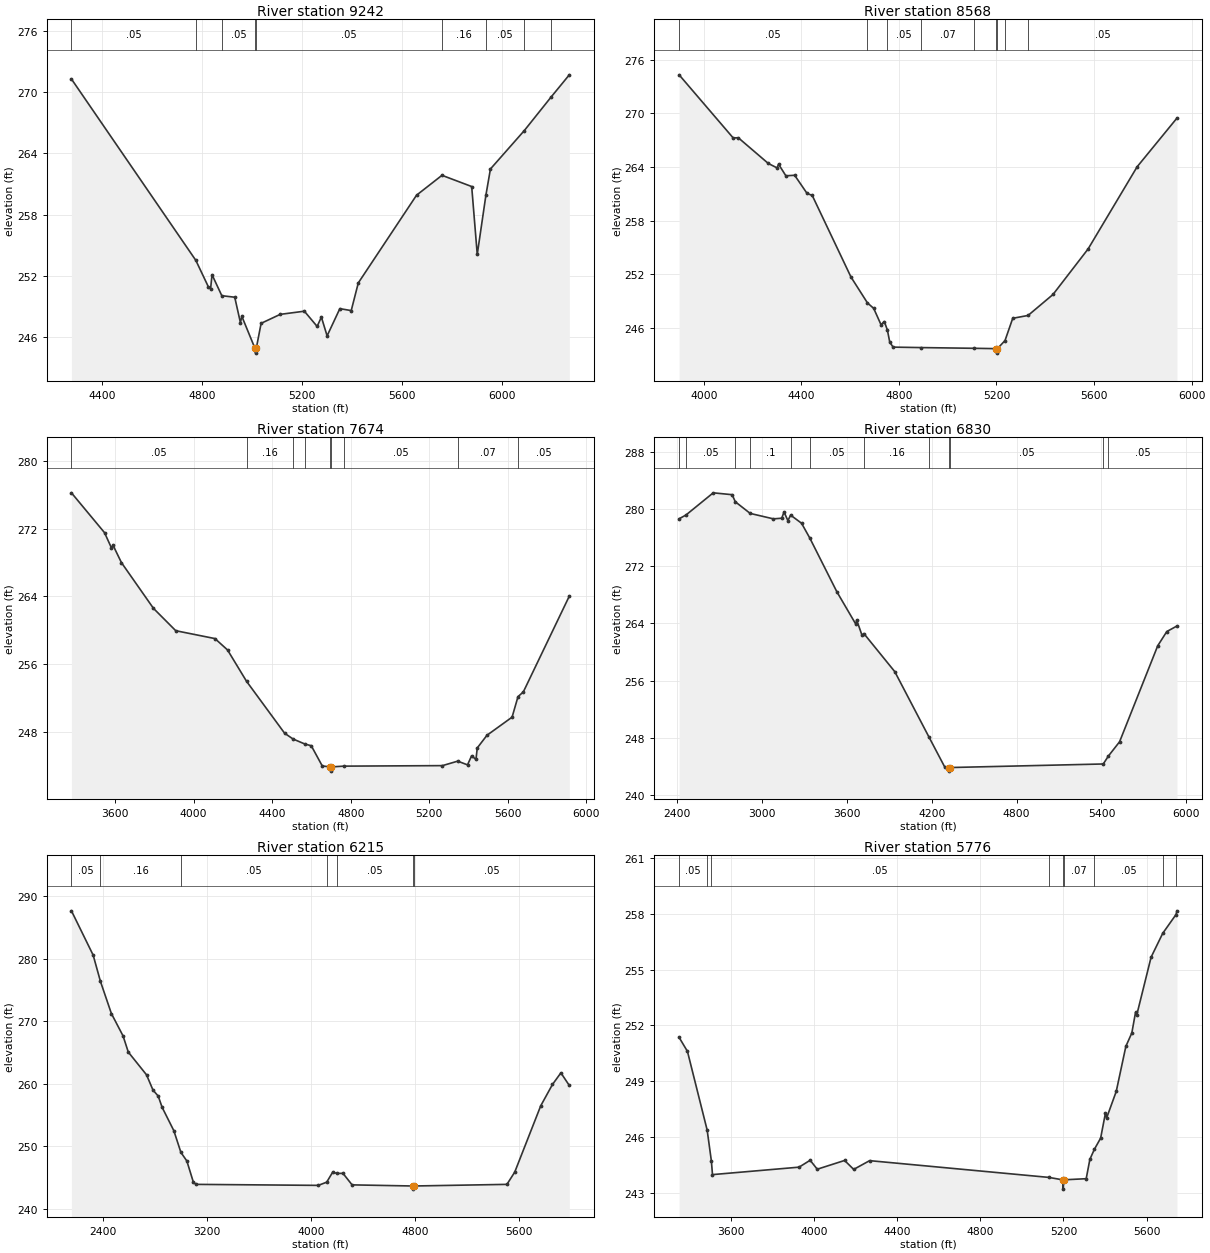
Type RM Length L Ch R = 1 ,9242    ,674,674,674
BEGIN DESCRIPTION:
UNT0485 IN WICK 15.0
END DESCRIPTION:
XS GIS Cut Line= 2
      3616707.21     10235307.05      3615853.03     10237103.95
#Sta/Elev= 30
  4277.5   271.3  4774.7  253.52  4825.1  250.91  4833.7  250.75  4839.3  252.12
  4878.4  250.06  4930.1  249.91  4952.8  247.42  4958.4  248.04  5010.4  244.93
  5013.1  244.43  5016.4  244.93  5035.5  247.35  5111.9  248.23  5208.3  248.54
  5259.3  247.05  5276.4  247.96  5299.2  246.12  5350.1  248.79  5395.6   248.6
  5423.8  251.31  5656.6  259.91  5758.3  261.86    5877  260.76  5899.2   254.1
  5933.9  259.93  5951.9  262.48  6087.4  266.25  6194.2  269.53  6267.1  271.71
#Mann= 9 ,-1 , 0
  4277.5     .05       0  4774.7     .16       0  4878.4     .05       0
  5010.4    .035       0  5016.4     .05       0  5758.3     .16       0
  5933.9     .05       0  6087.4      .1       0  6194.2     .05       0
Bank Sta=5010.4,5016.4
XS Rating Curve= 0 ,0
Exp/Cntr=0.3,0.1

Type RM Length L Ch R = 1 ,8568    ,894,894,894
BEGIN DESCRIPTION:
UNT0485 IN WICK 14.0
END DESCRIPTION:
XS GIS Cut Line= 2
      3616391.24     10235053.57      3615252.81     10236747.34
#Sta/Elev= 30
  3899.2  274.29  4120.8  267.24  4141.8  267.26  4264.8  264.39  4300.8  263.89
  4306.8  264.31  4336.8  263.01  4372.8  263.07  4423.7  261.04  4444.8  260.82
  4603.7   251.7  4671.2  248.81  4696.8   248.2  4726.7  246.38  4740.3  246.73
  4752.8  245.79  4762.7  244.42  4776.4  243.87    4891  243.82  5107.7  243.74
  5197.8   243.7  5200.5   243.2  5203.8   243.7    5235   244.6  5266.7  247.09
  5329.6  247.41  5431.7  249.75  5575.7  254.84  5776.7  264.02    5940  269.46
#Mann= 9 ,-1 , 0
  3899.2     .05       0  4671.2     .07       0  4752.8     .05       0
    4891     .07       0  5107.7     .05       0  5197.8     .07       0
  5203.8     .05       0    5235      .1       0  5329.6     .05       0
Bank Sta=5197.8,5203.8
XS Rating Curve= 0 ,0
Exp/Cntr=0.3,0.1

Type RM Length L Ch R = 1 ,7674    ,844,844,844
BEGIN DESCRIPTION:
UNT0485 IN WICK 12.0
END DESCRIPTION:
XS GIS Cut Line= 2
      3616002.33     10234324.43      3614399.41     10236288.19
#Sta/Elev= 30
  3378.2  276.22  3546.7  271.51  3581.9  269.71  3589.8  270.03  3632.8  267.97
  3795.9  262.56  3909.3  259.92  4108.9  258.99  4172.8  257.65  4269.7  253.94
  4463.6   247.8  4506.4  247.12  4566.2  246.53  4599.3  246.32  4655.3  243.93
  4695.4  243.82  4698.1  243.32  4701.4  243.82    4766  243.91    5267  243.97
    5345   244.5  5394.8  244.06  5415.6  245.13  5437.9   244.7  5444.4  246.06
  5493.9  247.56  5621.7   249.7  5651.8  252.12  5679.1  252.69  5913.1  264.01
#Mann= 9 ,-1 , 0
  3378.2     .05       0  4269.7     .16       0  4506.4     .05       0
  4566.2     .07       0  4695.4    .033       0  4701.4     .07       0
    4766     .05       0    5345     .07       0  5651.8     .05       0
Bank Sta=4695.4,4701.4
XS Rating Curve= 0 ,0
Exp/Cntr=0.3,0.1

Type RM Length L Ch R = 1 ,6830    ,615,615,615
BEGIN DESCRIPTION:
UNT0485 IN WICK 10.0
END DESCRIPTION:
XS GIS Cut Line= 3
      3615307.92     10233248.02      3614550.96     10233678.59
      3613967.63     10236261.89
#Sta/Elev= 30
  2414.7  278.64  2463.3  279.17  2655.9  282.27  2789.5  282.01  2811.8  281.02
  2917.2  279.39  3081.1  278.63  3140.2  278.72  3156.1  279.59  3183.5  278.39
    3203  279.15    3280  278.02  3338.6  275.94  3529.8  268.43  3664.6  263.87
  3669.7  264.49  3707.8  262.33  3720.6  262.59  3939.2  257.26  4180.2  248.14
  4293.4  243.88  4321.1  243.85  4323.9  243.35  4327.1  243.85  5412.8  244.35
  5448.3  245.44  5528.2  247.46  5797.7  260.88  5861.9  262.87  5933.9  263.65
#Mann= 12 ,-1 , 0
  2414.7      .1       0  2463.3     .05       0  2811.8     .16       0
  2917.2      .1       0    3203     .16       0  3338.6     .05       0
  3720.6     .16       0  4180.2     .05       0  4321.1    .033       0
  4327.1     .05       0  5412.8     .07       0  5448.3     .05       0
Bank Sta=4321.1,4327.1
XS Rating Curve= 0 ,0
Exp/Cntr=0.3,0.1

Type RM Length L Ch R = 1 ,6215    ,439,439,439
BEGIN DESCRIPTION:
UNT0485 IN WICK 8.0
END DESCRIPTION:
XS GIS Cut Line= 2
      3613425.95     10232414.67       3613620.4     10236241.13
#Sta/Elev= 30
  2156.2  287.65  2323.4  280.57  2379.5  276.37  2463.6  271.24  2553.7  267.65
  2593.7  265.08  2733.9  261.45    2784     259    2824  258.05  2854.1  256.25
  2944.2  252.52  2998.6  249.05  3044.3  247.68  3094.4   244.3  3114.4  243.94
  4055.6  243.78  4120.5  244.29  4165.8  245.86  4203.1  245.69  4245.9   245.7
    4316  243.86  4783.6  243.68  4786.3  243.18  4789.6  243.68  5507.5  243.94
  5567.6   245.9  5767.8   256.5  5857.9   259.9  5922.8  261.76  5987.6  259.74
#Mann= 7 ,-1 , 0
  2156.2     .05       0  2379.5     .16       0  2998.6     .05       0
  4120.5     .16       0  4203.1     .05       0  4783.6    .033       0
  4789.6     .05       0
Bank Sta=4783.6,4789.6
XS Rating Curve= 0 ,0
Exp/Cntr=0.3,0.1

Type RM Length L Ch R = 1 ,5776    ,679,679,679
BEGIN DESCRIPTION:
UNT0485 IN WICK 7.0
END DESCRIPTION:
XS GIS Cut Line= 2
      3612497.46     10233935.08      3613477.73     10236121.16
#Sta/Elev= 30
  3350.7  251.36  3390.8  250.61  3485.7  246.38  3506.1  244.71  3511.3  243.99
  3927.8  244.39  3981.2  244.76  4015.5  244.28    4147  244.75  4190.8  244.27
  4267.5  244.74  5129.8  243.84  5196.1  243.71  5198.8  243.21  5202.1  243.71
  5309.6  243.77  5327.3  244.81    5349  245.35  5379.1  245.95  5402.3   247.3
  5407.8  247.03  5454.2  248.46  5500.5  250.88  5529.2   251.6  5546.9   252.7
  5552.3  252.54  5621.9  255.67  5677.8  256.95  5741.7  257.96  5746.5  258.16
#Mann= 9 ,-1 , 0
  3350.7     .05       0  3485.7      .1       0  3506.1     .05       0
  5129.8     .07       0  5196.1    .033       0  5202.1     .07       0
    5349     .05       0  5677.8     .08       0  5741.7     .05       0
Bank Sta=5196.1,5202.1
XS Rating Curve= 0 ,0
Exp/Cntr=0.3,0.1

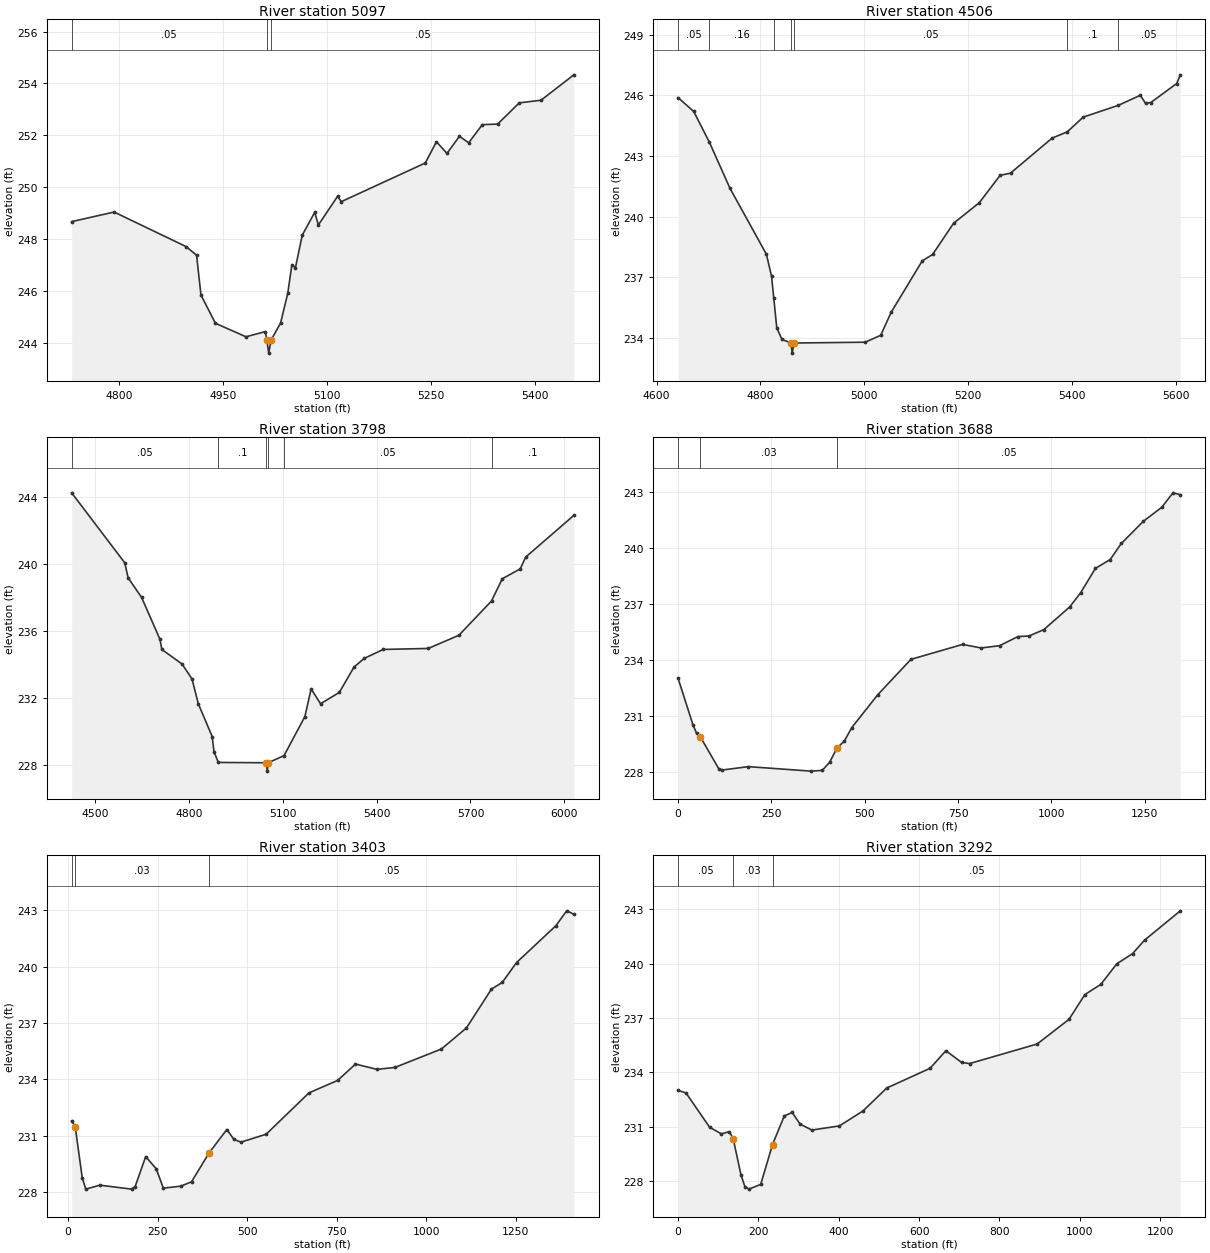
Type RM Length L Ch R = 1 ,5097    ,591,591,591
BEGIN DESCRIPTION:
Mapping XS 27701401
END DESCRIPTION:
XS GIS Cut Line= 2
      3612603.37     10235895.16       3613297.5      10236103.4
#Sta/Elev= 30
  4731.7  248.67    4793  249.04  4897.4   247.7    4912  247.37  4918.3  245.84
  4939.2  244.75  4983.3  244.23  5011.2  244.43  5013.4   244.1  5016.1   243.6
  5019.4   244.1  5033.2  244.76  5043.6  245.91  5049.4  246.99  5054.7   246.9
  5064.5  248.15  5082.5  249.03  5087.7  248.54  5115.6  249.65  5120.8  249.44
    5242  250.93  5258.2  251.75  5273.3   251.3  5291.3  251.96  5304.6  251.71
  5324.4  252.41  5346.4  252.43  5377.7  253.25    5409  253.35  5456.4  254.33
#Mann= 3 ,-1 , 0
  4731.7     .05       0  5013.4     .04       0  5019.4     .05       0
Bank Sta=5013.4,5019.4
XS Rating Curve= 0 ,0
Exp/Cntr=0.3,0.1

Type RM Length L Ch R = 1 ,4506    ,708,708,708
BEGIN DESCRIPTION:
Mapping XS d7cbf398
END DESCRIPTION:
XS GIS Cut Line= 2
      3612517.32     10235961.63      3612553.71     10236928.55
#Sta/Elev= 30
  4641.4  245.88  4671.4   245.2  4701.8  243.67  4741.5  241.39  4811.5  238.14
  4821.5  237.04  4825.7  235.97  4831.5   234.5  4841.5  233.93  4858.6  233.75
  4861.3  233.25  4864.6  233.75  5001.7  233.79  5031.7  234.13  5051.7  235.26
  5111.7  237.81  5131.8  238.13  5172.1  239.67  5221.8  240.69  5261.8  242.04
  5281.9  242.15  5361.9  243.88  5391.1  244.19    5422  244.92  5489.5   245.5
    5532     246    5542   245.6  5552.1  245.64  5602.1  246.58    5609  247.01
#Mann= 7 ,-1 , 0
  4641.4     .05       0  4701.8     .16       0  4825.7     .05       0
  4858.6    .035       0  4864.6     .05       0  5391.1      .1       0
  5489.5     .05       0
Bank Sta=4858.6,4864.6
XS Rating Curve= 0 ,0
Exp/Cntr=0.3,0.1

Type RM Length L Ch R = 1 ,3798    ,110,110,110
BEGIN DESCRIPTION:
Mapping XS 6fda1f1a
END DESCRIPTION:
XS GIS Cut Line= 4
       3612249.3     10235860.73      3611901.96     10236001.44
      3611855.86     10236701.26      3612338.71     10236919.32
#Sta/Elev= 30
  4424.6  244.26  4594.2  240.08  4605.3  239.17  4648.1  238.01  4707.1  235.49
  4712.9  234.89  4777.6  234.02  4809.6  233.12  4829.6  231.64    4874  229.68
  4879.7  228.78  4893.6  228.13  5047.1  228.11  5049.9  227.61  5053.1  228.11
  5103.8  228.54  5170.4  230.87  5190.4  232.53  5220.5  231.64  5280.6  232.32
  5327.7  233.84  5360.8  234.36  5420.9  234.89  5565.1  234.95  5663.1  235.74
  5767.2  237.79  5801.8  239.12    5859  239.71  5876.7  240.42  6030.5  242.91
#Mann= 6 ,-1 , 0
  4424.6     .05       0  4893.6      .1       0  5047.1     .07       0
  5053.1      .1       0  5103.8     .05       0  5767.2      .1       0
Bank Sta=5047.1,5053.1
XS Rating Curve= 0 ,0
Exp/Cntr=0.3,0.1

Type RM Length L Ch R = 1 ,3688    ,285,285,285
XS GIS Cut Line= 3
     3611748.242    10235926.408     3611835.048    10236719.811
     3612341.992     10236929.88
#Sta/Elev= 30
       0  233.03   39.59  230.56   49.49  230.09   59.39  229.91  108.88   228.2
  118.78  228.13  188.07  228.31  356.35  228.07  386.04  228.11  405.84  228.54
  425.64  229.31  445.43  229.68  465.23   230.4  534.52  232.15  623.61  234.05
  762.18  234.85  811.66  234.66  861.08  234.78  910.49  235.27  940.14   235.3
  979.67  235.64 1048.85  236.85  1078.5  237.62 1118.03  238.92 1157.56  239.39
 1187.21  240.25 1246.51  241.44 1295.92  242.19 1325.57  242.96 1345.33  242.86
#Mann= 3 , 0 , 0
       0     .05       0   59.39     .03       0  425.64     .05       0
Bank Sta=59.39,425.64
XS Rating Curve= 0 ,0
Exp/Cntr=0.3,0.1

Type RM Length L Ch R = 1 ,3403    ,111,111,111
XS GIS Cut Line= 4
     3611347.201    10236025.367      3611619.77    10236395.158
     3611815.951    10236725.019     3612345.465    10236935.089
#Sta/Elev= 30
    9.84  231.79   19.68   231.5   39.36  228.78    49.2  228.17   88.57  228.38
  177.13  228.17  186.97   228.3  216.49   229.9  246.02  229.25   265.7  228.22
   314.9  228.33  344.42  228.56  393.63   230.1  442.96  231.34  462.91  230.81
  482.86  230.67  552.68  231.09  672.37  233.29  752.17  233.95  802.04  234.82
   861.9  234.54  911.87  234.64  1041.8  235.62 1111.76  236.74 1181.72  238.81
  1211.7  239.16 1251.68  240.22 1361.61  242.18  1391.6  242.97 1411.58  242.79
#Mann= 3 , 0 , 0
    9.84     .05       0   19.68     .03       0  393.63     .05       0
Bank Sta=19.68,393.63
XS Rating Curve= 0 ,0
Exp/Cntr=0.3,0.1

Type RM Length L Ch R = 1 ,3292    ,541,541,541
BEGIN DESCRIPTION:
Mapping XS 5ebd620d
END DESCRIPTION:
XS GIS Cut Line= 4
      3611320.41     10236302.77      3611592.59     10236371.79
    3611812.4778    10236735.436     3612333.312    10236940.297
#Sta/Elev= 30
       0     233   19.58  232.86   78.32  230.97  107.69   230.6  127.27  230.72
  137.06  230.34  156.64  228.32  166.43  227.68  176.22  227.55  205.59  227.81
  234.96  230.01  264.33  231.59  283.93  231.78  303.55  231.14  332.98  230.81
  401.65  231.04   460.5  231.87  519.36  233.13  627.27  234.22  666.51  235.19
  705.83  234.54  725.63  234.48  893.86  235.56  973.03  236.92 1012.62  238.29
  1052.2  238.85 1091.79  239.98 1131.37  240.55 1161.06  241.29 1250.13  242.91
#Mann= 3 , 0 , 0
       0     .05       0  137.06     .03       0  234.96     .05       0
Bank Sta=137.06,234.96
XS Rating Curve= 0 ,0
Exp/Cntr=0.3,0.1

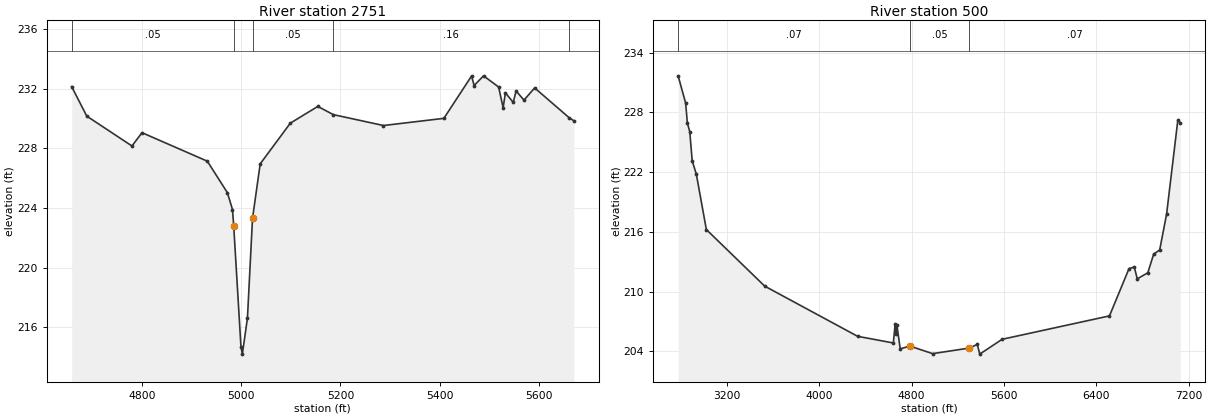
Type RM Length L Ch R = 1 ,2751    ,2251,2251,2251
BEGIN DESCRIPTION:
UNT0485 IN WICK 5.0
END DESCRIPTION:
XS GIS Cut Line= 3
      3611309.46     10236321.58      3611166.63     10237182.07
      3611236.87     10237304.61
#Sta/Elev= 30
  4657.5  232.13    4688  230.15  4779.2  228.15  4799.5  229.04  4931.3  227.13
  4971.8  225.02  4982.1  223.89 4984.54   222.8  4999.2   214.7    5002   214.2
  5012.3  216.62  5022.5  223.29    5038  226.95  5098.9  229.68  5154.3   230.8
  5185.6  230.25  5286.8  229.52  5408.7     230  5464.6  232.84  5469.7   232.2
  5488.8  232.85  5519.2   232.1  5528.3  230.71  5532.9  231.71  5548.7  231.07
  5554.5  231.84  5570.3  231.22  5591.9  232.04    5662  230.03    5671  229.84
#Mann= 5 ,-1 , 0
  4657.5     .05       0 4984.54    .035       0  5022.5     .05       0
  5185.6     .16       0    5662     .12       0
Bank Sta=4984.54,5022.5
XS Rating Curve= 0 ,0
Exp/Cntr=0.3,0.1

Type RM Length L Ch R = 1 ,500     ,0,0,0
BEGIN DESCRIPTION:
UNT0485 IN WICK 1.0
END DESCRIPTION:
XS GIS Cut Line= 4
       3611232.6     10236011.07       3609732.6     10237033.64
      3609996.86     10238215.46      3611298.71     10238460.42
#Sta/Elev= 30
  2776.3  231.67  2841.5  228.94  2856.4  226.95  2877.4  226.04  2898.3  223.14
  2934.3  221.78    3021  216.23  3526.5  210.55  4331.4  205.51  4640.9  204.84
  4657.2  206.76  4662.3  205.72  4671.6  206.67  4700.6  204.25  4784.3  204.53
  4981.5  203.77  5300.8  204.33  5368.4   204.7  5389.7  203.72  5583.6  205.21
  6513.7  207.56  6683.1  212.31  6728.7  212.47  6754.4  211.28  6845.9  211.89
  6896.8  213.77  6948.8  214.18  7008.7  217.79  7106.2  227.24  7127.4  226.96
#Mann= 3 , 0 , 0
  2776.3     .07       0  4784.3     .05       0  5300.8     .07       0
Bank Sta=4784.3,5300.8
XS Rating Curve= 0 ,0
Exp/Cntr=0.3,0.1

Chan Stop Cuts=-1
Use User Specified Reach Order=0
Composite Channel Slope=5