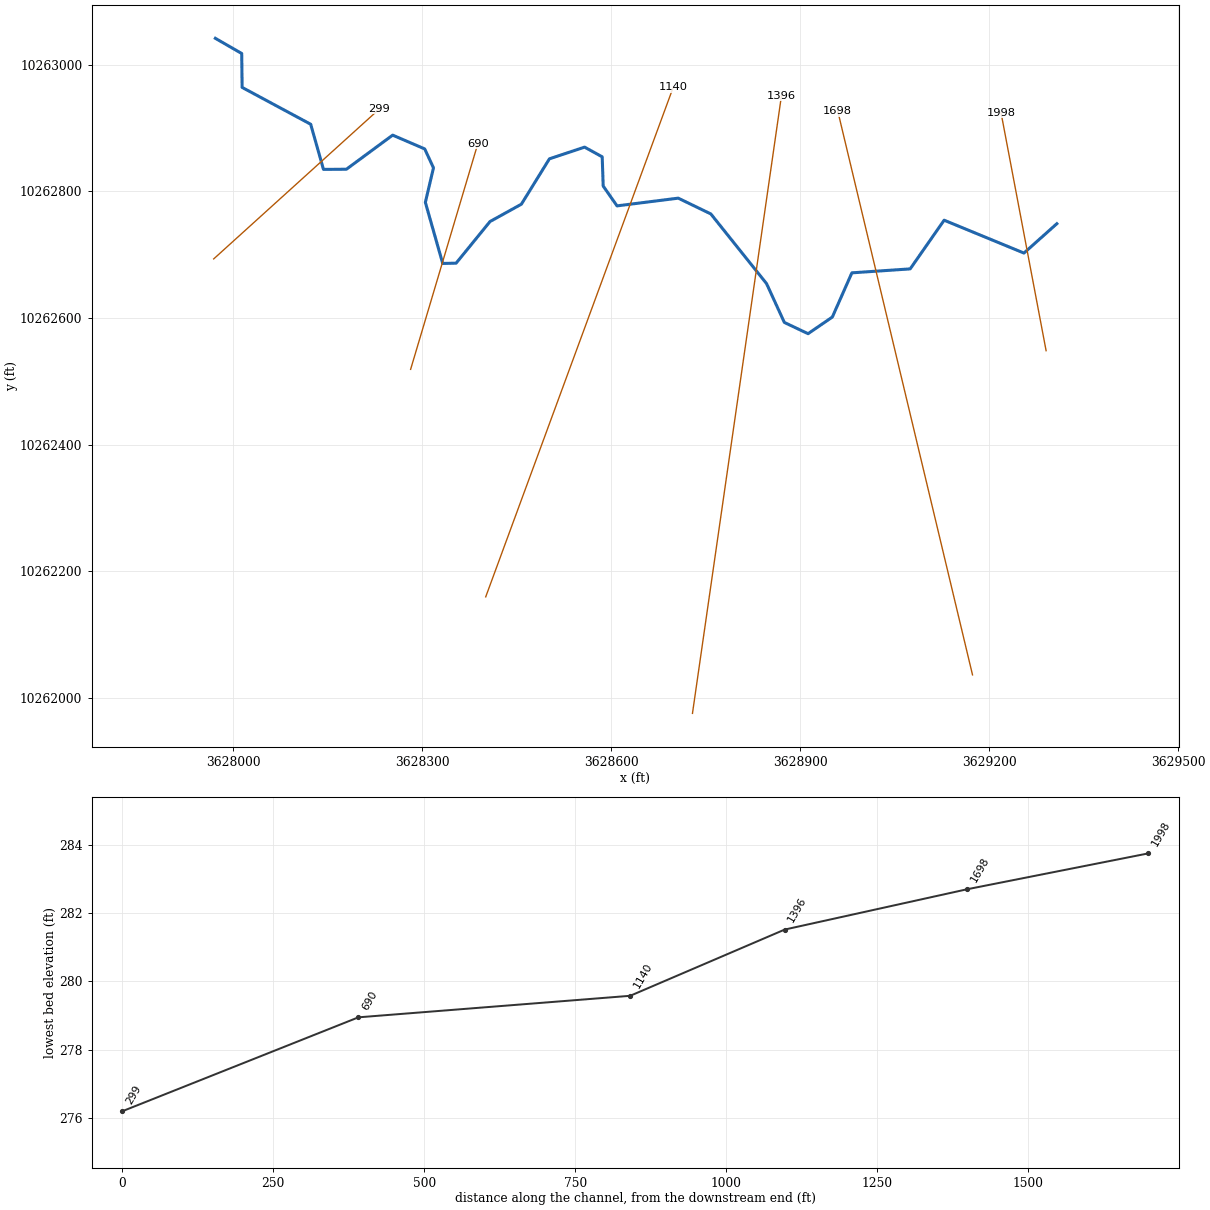
--- UNT04878 IN WICK.prj (project) ---

Proj Title=UNT04878 IN WICK Base Level Engineering
Current Plan=p01
Default Exp/Contr=0.3,0.1
English Units
Geom File=g01
Flow File=f01
Plan File=p01
BEGIN DESCRIPTION:
UNT04878 IN WICK
END DESCRIPTION:

--- UNT04878 IN WICK.p01 (plan) ---

Plan Title=Multiple Run
Short Identifier=Multiple
Geom File=g01
Flow File=f01
Subcritical Flow
K Sum by GR= 0
Std Step Tol= 0.01
Critical Tol= 0.01
Num of Std Step Trials= 20
Max Error Tol= 0.3
Flow Tol Ratio= 0.001
Split Flow NTrial= 30
Split Flow Tol= 0.02
Split Flow Ratio= 0.02
Log Output Level= 0
Friction Slope Method= 1
Unsteady Friction Slope Method= 2
Unsteady Bridges Friction Slope Method= 1
Parabolic Critical Depth
Global Vel Dist=  1 , 1 , 1
Global Log Level= 0
CheckData=True
Encroach Param= -1, 0, 0, 0
BEGIN DESCRIPTION:
Multiple Run
END DESCRIPTION:

--- UNT04878 IN WICK.f01 (steady flow) ---

Flow Title=Multiple
Number of Profiles=7
Profile Names=10-year,25-year,50-year,1pct_min,100-year,1pct_plu,500-year
River Rch & RM= UNT04878 IN WICK,Reach-1,1998
     282     360     422     363     491     664     664
Boundary for River Rch & Prof#=UNT04878 IN WICK,Reach-1,1
Up Type=0
Dn Type=3
Dn Slope=0.005
Boundary for River Rch & Prof#=UNT04878 IN WICK,Reach-1,2
Up Type=0
Dn Type=3
Dn Slope=0.005
Boundary for River Rch & Prof#=UNT04878 IN WICK,Reach-1,3
Up Type=0
Dn Type=3
Dn Slope=0.005
Boundary for River Rch & Prof#=UNT04878 IN WICK,Reach-1,4
Up Type=0
Dn Type=3
Dn Slope=0.005
Boundary for River Rch & Prof#=UNT04878 IN WICK,Reach-1,5
Up Type=0
Dn Type=3
Dn Slope=0.005
Boundary for River Rch & Prof#=UNT04878 IN WICK,Reach-1,6
Up Type=0
Dn Type=3
Dn Slope=0.005
Boundary for River Rch & Prof#=UNT04878 IN WICK,Reach-1,7
Up Type=0
Dn Type=3
Dn Slope=0.005

--- UNT04878 IN WICK.g01 (geometry) ---

Geom Title=Existing Conditions

River Reach=UNT04878 IN WICK,Reach-1
Reach XY= 30
      3629307.54     10262748.79      3629255.34     10262702.43
      3629128.67     10262754.35      3629074.80     10262677.44
      3628982.27     10262671.21      3628951.24     10262601.32
      3628912.72     10262575.08      3628875.10     10262592.85
      3628846.88     10262654.12      3628758.44     10262764.24
      3628706.68     10262789.17      3628609.53     10262776.97
      3628587.58     10262808.30      3628586.02     10262854.45
      3628558.06     10262869.78      3628502.25     10262851.31
      3628457.75     10262779.63      3628407.95     10262752.22
      3628354.19     10262686.48      3628332.92     10262686.04
      3628305.34     10262782.54      3628318.26     10262837.06
      3628304.34     10262866.94      3628253.47     10262888.73
      3628180.04     10262834.84      3628143.65     10262834.63
      3628123.40     10262905.91      3628014.55     10262964.13
      3628013.90     10263017.70      3627972.11     10263041.64

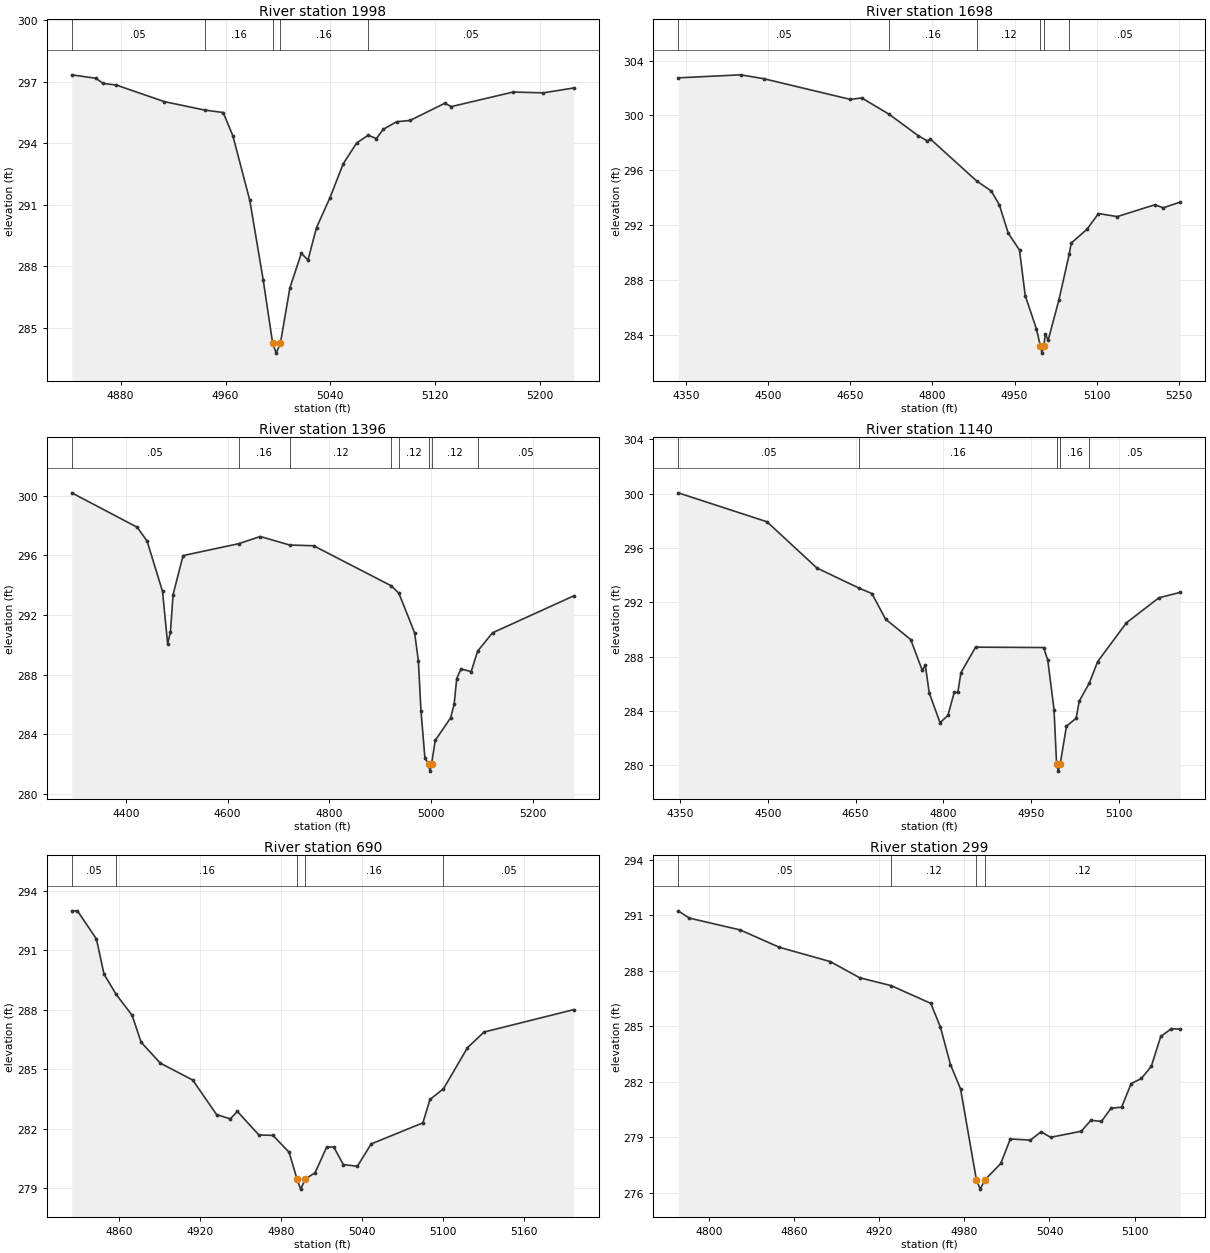
Type RM Length L Ch R = 1,1998,300,300,300
BEGIN DESCRIPTION:
UNT04878 IN WICK 2.0
END DESCRIPTION:
XS GIS Cut Line= 2
      3629290.51     10262548.21      3629218.91     10262924.46
#Sta/Elev= 30
  4842.7  297.34  4861.2  297.17  4866.6  296.92  4876.7  296.84  4913.4  296.03
  4944.0  295.62  4958.2  295.50  4965.6  294.36  4978.5  291.21  4988.7  287.34
  4995.9  284.25  4998.6  283.75  5001.9  284.25  5009.1  286.94  5017.8  288.62
  5022.9  288.30  5029.4  289.88  5039.6  291.33  5049.8  293.00  5060.0  294.01
  5068.8  294.39  5075.1  294.23  5080.3  294.68  5090.5  295.05  5100.7  295.11
  5127.2  295.95  5132.3  295.79  5179.4  296.50  5202.5  296.46  5225.7  296.70
#Mann=5,-1,0
  4842.7    0.05       0  4944.0    0.16       0  4995.9    0.07       0
  5001.9    0.16       0  5068.8    0.05       0
Bank Sta=4995.9,5001.9
Exp/Cntr=0.3,0.1

Type RM Length L Ch R = 1,1698,302,302,302
BEGIN DESCRIPTION:
Mapping XS eca2d7c3
END DESCRIPTION:
XS GIS Cut Line= 2
      3629173.72     10262036.12      3628959.83     10262926.90
#Sta/Elev= 30
  4336.4  302.74  4450.2  302.96  4492.2  302.68  4650.6  301.17  4671.2  301.28
  4721.1  300.09  4774.0  298.54  4791.2  298.14  4796.4  298.29  4880.7  295.24
  4907.7  294.50  4922.3  293.49  4938.6  291.43  4959.1  290.20  4969.5  286.89
  4990.0  284.46  4997.3  283.20  5000.0  282.70  5003.3  283.20  5006.3  284.09
  5011.4  283.64  5031.1  286.59  5050.0  289.94  5053.4  290.71  5082.5  291.73
  5103.1  292.86  5137.4  292.64  5206.0  293.50  5221.4  293.28  5252.5  293.70
#Mann=6,-1,0
  4336.4    0.05       0  4721.1    0.16       0  4880.7    0.12       0
  4997.3    0.07       0  5003.3    0.12       0  5050.0    0.05       0
Bank Sta=4997.3,5003.3
Exp/Cntr=0.3,0.1

Type RM Length L Ch R = 1,1396,256,256,256
BEGIN DESCRIPTION:
Mapping XS e616a5de
END DESCRIPTION:
XS GIS Cut Line= 2
      3628729.27     10261975.29      3628870.51     10262951.02
#Sta/Elev= 30
  4294.1  300.19  4422.7  297.88  4442.0  296.95  4472.3  293.58  4482.4  290.06
  4487.9  290.87  4493.0  293.36  4512.7  295.98  4622.1  296.78  4664.3  297.26
  4721.9  296.69  4769.0  296.64  4921.6  293.95  4936.5  293.45  4967.4  290.79
  4974.7  288.92  4979.8  285.58  4987.6  282.38  4994.7  282.02  4997.5  281.52
  5000.7  282.02  5007.8  283.58  5038.1  285.10  5045.0  286.02  5050.0  287.73
  5058.3  288.37  5078.5  288.20  5091.0  289.57  5120.3  290.80  5280.0  293.28
#Mann=8,-1,0
  4294.1    0.05       0  4622.1    0.16       0  4721.9    0.12       0
  4921.6    0.16       0  4936.5    0.12       0  4994.7    0.07       0
  5000.7    0.12       0  5091.0    0.05       0
Bank Sta=4994.7,5000.7
Exp/Cntr=0.3,0.1

Type RM Length L Ch R = 1,1140,450,450,450
BEGIN DESCRIPTION:
Mapping XS 1cc6edf5
END DESCRIPTION:
XS GIS Cut Line= 2
      3628401.14     10262159.33      3628698.65     10262964.09
#Sta/Elev= 30
  4347.0  300.05  4498.7  297.92  4584.0  294.52  4655.1  293.06  4678.0  292.64
  4701.3  290.76  4744.2  289.26  4763.9  287.01  4769.3  287.35  4775.9  285.34
  4794.4  283.14  4807.9  283.68  4818.6  285.37  4824.8  285.37  4830.1  286.82
  4855.2  288.70  4971.5  288.67  4978.5  287.74  4989.2  284.11  4993.6  280.08
  4996.3  279.58  4999.6  280.08  5010.5  282.89  5027.0  283.47  5032.3  284.73
  5049.4  286.05  5063.8  287.64  5112.9  290.49  5168.4  292.33  5205.0  292.73
#Mann=5,-1,0
  4347.0    0.05       0  4655.1    0.16       0  4993.6    0.07       0
  4999.6    0.16       0  5049.4    0.05       0
Bank Sta=4993.6,4999.6
Exp/Cntr=0.3,0.1

Type RM Length L Ch R = 1,690,391,391,391
BEGIN DESCRIPTION:
Mapping XS 07fdc913
END DESCRIPTION:
XS GIS Cut Line= 2
      3628281.96     10262518.71      3628388.73     10262875.47
#Sta/Elev= 30
  4824.6  292.98  4828.8  292.98  4842.9  291.56  4848.5  289.79  4857.5  288.77
  4869.4  287.71  4876.0  286.36  4890.3  285.30  4914.3  284.45  4932.0  282.71
  4942.2  282.49  4947.4  282.87  4963.4  281.68  4973.8  281.66  4985.8  280.81
  4991.7  279.45  4994.4  278.95  4997.7  279.45  5005.1  279.78  5013.6  281.06
  5018.9  281.08  5026.0  280.19  5036.4  280.10  5046.7  281.23  5085.0  282.29
  5090.3  283.47  5100.3  284.01  5118.1  286.08  5130.4  286.87  5197.0  288.00
#Mann=5,-1,0
  4824.6    0.05       0  4857.5    0.16       0  4991.7    0.07       0
  4997.7    0.16       0  5100.3    0.05       0
Bank Sta=4991.7,4997.7
Exp/Cntr=0.3,0.1

Type RM Length L Ch R = 1,299,0,0,0
BEGIN DESCRIPTION:
UNT04878 IN WICK 1.0
END DESCRIPTION:
XS GIS Cut Line= 2
      3627969.44     10262693.19      3628232.51     10262930.22
#Sta/Elev= 30
  4778.2  291.24  4785.9  290.85  4821.8  290.21  4849.5  289.27  4885.3  288.50
  4906.3  287.62  4928.3  287.20  4956.3  286.24  4963.1  284.96  4970.2  282.93
  4977.3  281.62  4988.5  276.70  4991.2  276.20  4994.5  276.70  5005.7  277.59
  5012.4  278.91  5026.6  278.85  5034.1  279.30  5040.8  279.00  5062.5  279.33
  5069.2  279.92  5076.7  279.86  5083.4  280.57  5090.9  280.63  5097.6  281.90
  5104.8  282.18  5111.8  282.83  5118.5  284.45  5126.0  284.87  5132.3  284.85
#Mann=4,-1,0
  4778.2    0.05       0  4928.3    0.12       0  4988.5    0.07       0
  4994.5    0.12       0
Bank Sta=4988.5,4994.5
Exp/Cntr=0.3,0.1

Chan Stop Cuts=-1