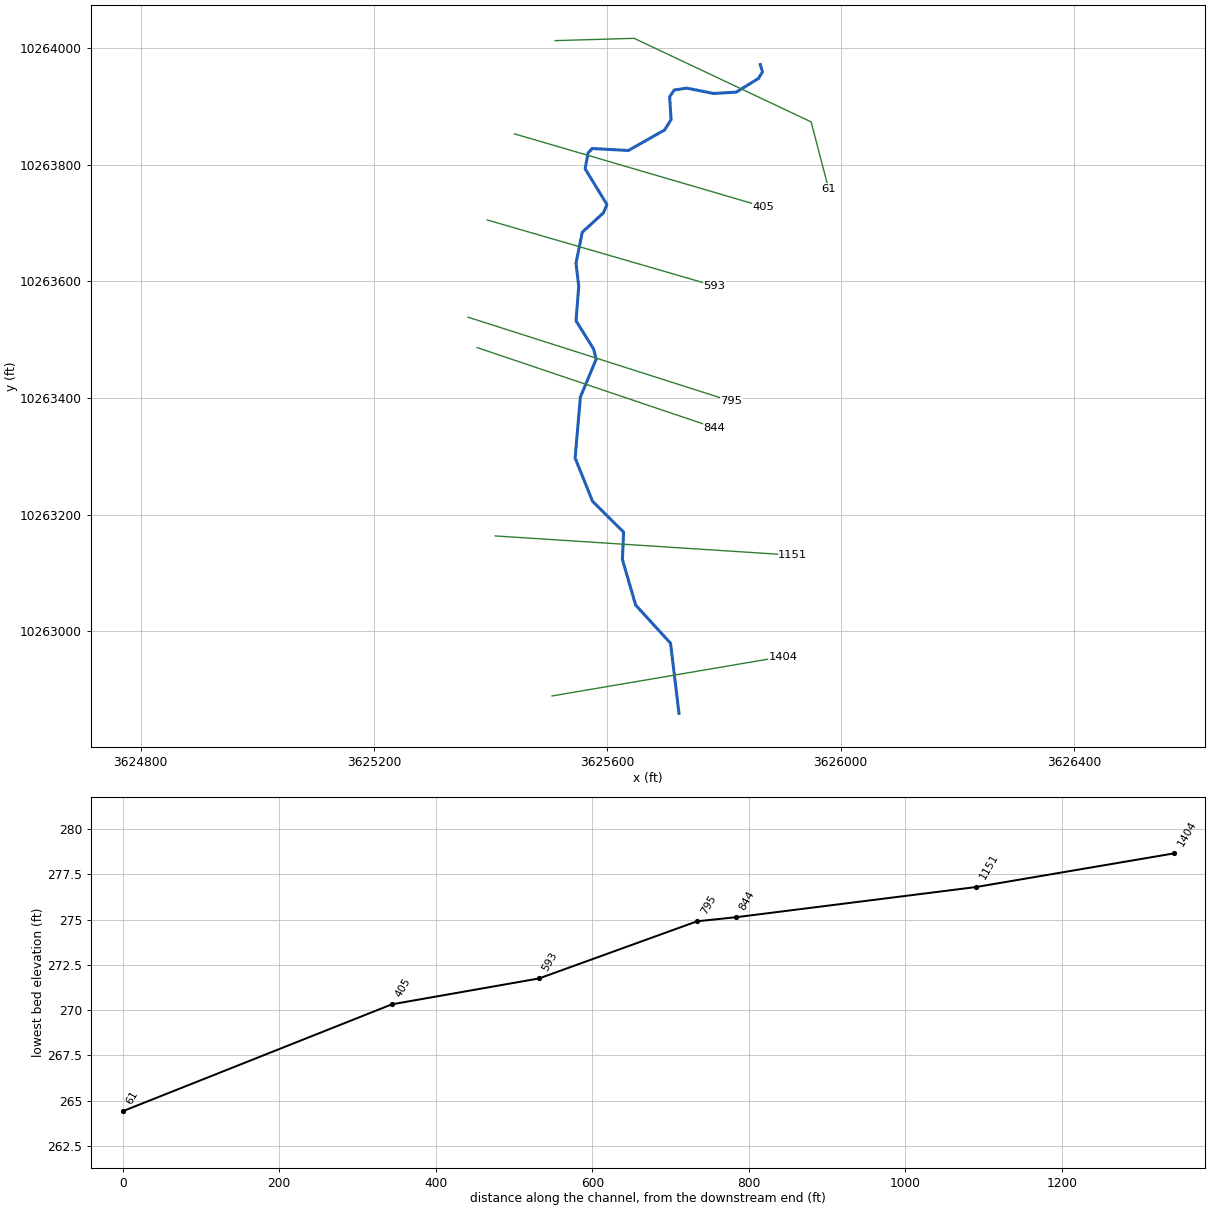
--- UNT04879 IN WICK.prj (project) ---

Proj Title=UNT04879 IN WICK Base Level Engineering
Current Plan=p01
Default Exp/Contr=0.3,0.1
English Units
Geom File=g01
Flow File=f01
Plan File=p01
Y Axis Title=Elevation
X Axis Title(PF)=Main Channel Distance
X Axis Title(XS)=Station
BEGIN DESCRIPTION:
UNT04879 IN WICK
END DESCRIPTION:
DSS Export Rating Curves= 0
DSS Export Rating Curve Sorted= 0
DSS Export Volume Flow Curves= 0
DXF OffsetX= 0
DXF OffsetY= 0
DXF ScaleX= 1
DXF ScaleY= 10

--- UNT04879 IN WICK.p01 (plan) ---

Plan Title=Multiple Run
Short Identifier=Multiple
Geom File=g01
Flow File=f01
Subcritical Flow
K Sum by GR= 0
Std Step Tol= 0.01
Critical Tol= 0.01
Num of Std Step Trials= 20
Max Error Tol= 0.3
Flow Tol Ratio= 0.001
Split Flow NTrial= 30
Split Flow Tol= 0.02
Split Flow Ratio= 0.02
Log Output Level= 0
Friction Slope Method= 1
Unsteady Friction Slope Method= 2
Unsteady Bridges Friction Slope Method= 1
Parabolic Critical Depth
Global Vel Dist=  1 , 1 , 1
Global Log Level= 0
CheckData=True
Encroach Param= -1, 0, 0, 0
BEGIN DESCRIPTION:
Multiple Run
END DESCRIPTION:

--- UNT04879 IN WICK.f01 (steady flow) ---

Flow Title=Multiple
Number of Profiles=7
Profile Names=10-year,25-year,50-year,1pct_min,100-year,1pct_plu,500-year
River Rch & RM= UNT04879 IN WICK,Reach-1,1404
     171     212     243     206     278     377     364
River Rch & RM= UNT04879 IN WICK,Reach-1,61
     610     813     977     860    1163    1572    1649
Boundary for River Rch & Prof#=UNT04879 IN WICK,Reach-1,1
Up Type=0
Dn Type=3
Dn Slope=0.005
Boundary for River Rch & Prof#=UNT04879 IN WICK,Reach-1,2
Up Type=0
Dn Type=3
Dn Slope=0.005
Boundary for River Rch & Prof#=UNT04879 IN WICK,Reach-1,3
Up Type=0
Dn Type=3
Dn Slope=0.005
Boundary for River Rch & Prof#=UNT04879 IN WICK,Reach-1,4
Up Type=0
Dn Type=3
Dn Slope=0.005
Boundary for River Rch & Prof#=UNT04879 IN WICK,Reach-1,5
Up Type=0
Dn Type=3
Dn Slope=0.005
Boundary for River Rch & Prof#=UNT04879 IN WICK,Reach-1,6
Up Type=0
Dn Type=3
Dn Slope=0.005
Boundary for River Rch & Prof#=UNT04879 IN WICK,Reach-1,7
Up Type=0
Dn Type=3
Dn Slope=0.005

--- UNT04879 IN WICK.g01 (geometry) ---

Geom Title=Existing Conditions
Program Version=4.10

River Reach=UNT04879 IN WICK,Reach-1
Reach XY= 30
      3625722.79     10262859.34      3625708.31     10262979.53
      3625648.54     10263044.93      3625625.84     10263122.85
      3625627.77     10263170.13      3625574.69     10263222.65
      3625544.74     10263297.09      3625553.75     10263401.55
      3625580.86     10263466.65      3625576.47     10263483.92
      3625546.26     10263532.31      3625550.96     10263591.59
      3625546.21     10263631.02      3625556.97     10263684.06
      3625593.39      10263717.5      3625599.29     10263731.78
      3625561.81     10263792.78      3625566.98      10263820.1
      3625574.15     10263827.67      3625636.08     10263824.26
      3625698.19     10263859.51       3625709.2     10263877.12
      3625706.75     10263916.45      3625714.62     10263927.93
      3625736.15     10263931.17      3625782.18       10263922.
      3625820.94     10263924.32      3625859.05     10263947.73
      3625865.97     10263959.12      3625862.11     10263971.64

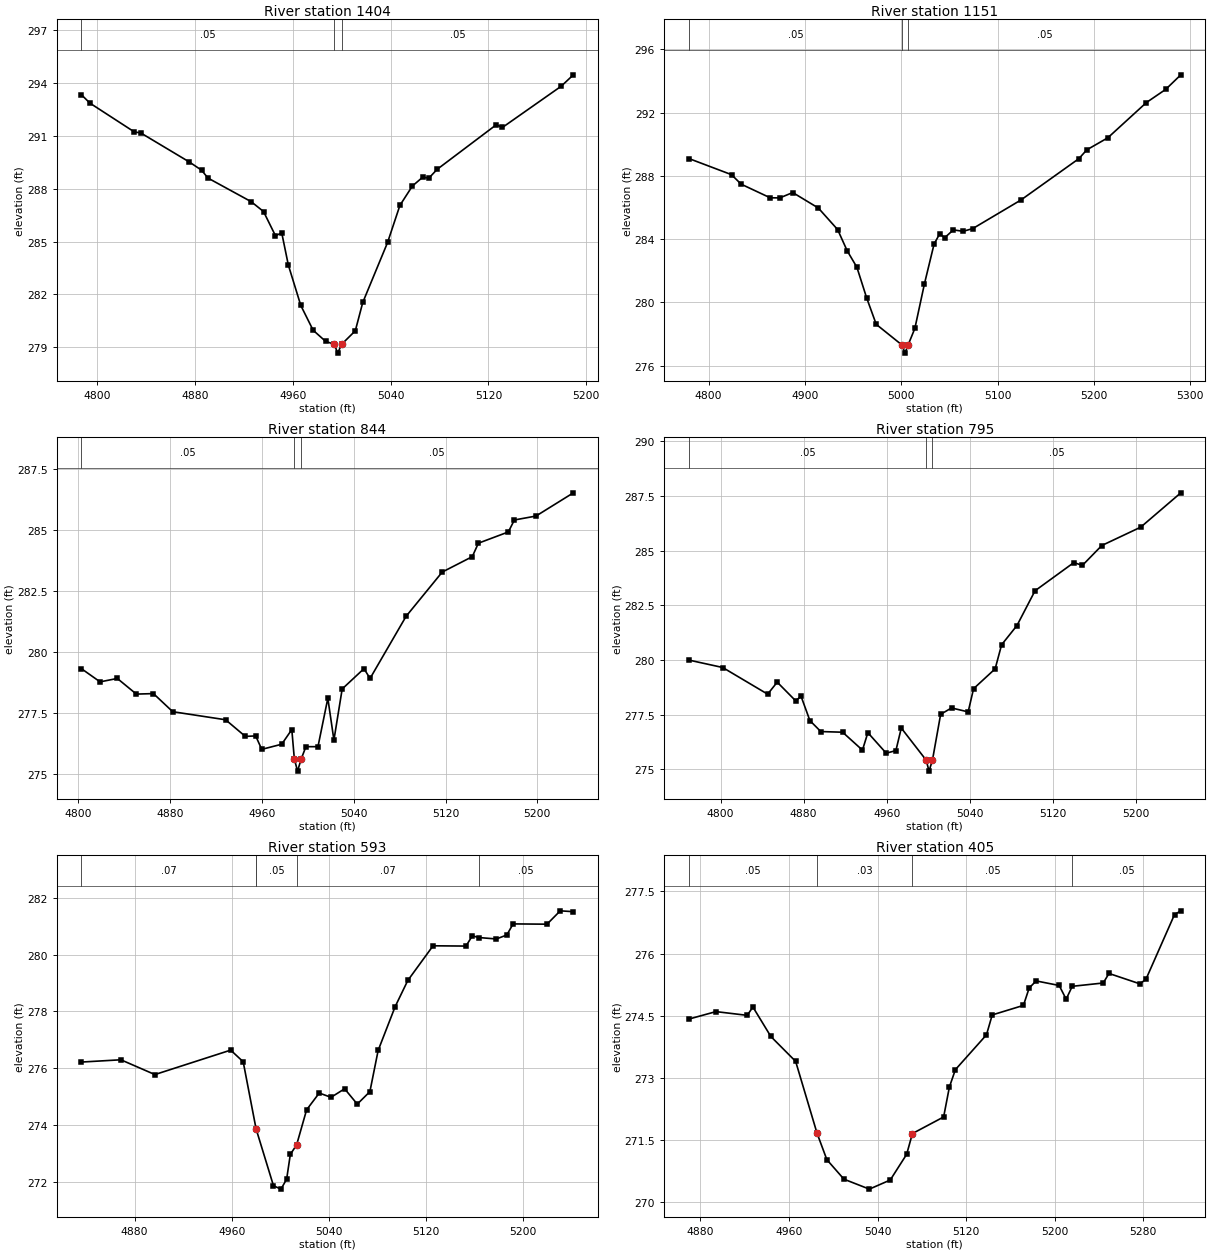
Type RM Length L Ch R = 1 ,1404    ,253,253,253
BEGIN DESCRIPTION:
UNT04879 IN WICK 2.0
END DESCRIPTION:
XS GIS Cut Line= 2
      3625505.17      10262889.2      3625901.96     10262956.78
#Sta/Elev= 30
    4787  293.35    4794  292.87  4830.4  291.23  4835.5  291.18  4875.2  289.53
  4885.3  289.06  4890.6  288.61  4925.9  287.27    4936  286.71  4945.8  285.33
  4950.9   285.5  4956.3  283.67  4966.5  281.37  4976.6  279.96  4986.8  279.33
  4993.9  279.16  4996.7  278.66  4999.9  279.16  5011.1  279.93  5017.2  281.54
  5037.5  284.95  5047.6  287.06  5057.8  288.16  5066.2  288.66  5071.3  288.61
  5078.1  289.11  5126.4  291.64  5131.5  291.49  5179.5  293.83  5189.5  294.48
#Mann= 3 ,-1 , 0
    4787     .05       0  4993.9     .03       0  4999.9     .05       0
Bank Sta=4993.9,4999.9
XS Rating Curve= 0 ,0
Exp/Cntr=0.3,0.1

Type RM Length L Ch R = 1 ,1151    ,307,307,307
BEGIN DESCRIPTION:
Mapping XS e4480ef6
END DESCRIPTION:
XS GIS Cut Line= 2
      3625407.93     10263163.51      3625917.77     10263130.56
#Sta/Elev= 30
  4779.4   289.1  4823.7  288.08  4833.7  287.48  4863.8  286.62  4873.8  286.61
  4887.3  286.95  4913.9  285.97  4933.9  284.61  4943.9  283.26  4953.9  282.23
    4964   280.3    4974  278.62    5001   277.3  5003.8   276.8    5007   277.3
  5014.1  278.36  5024.1  281.19  5034.1   283.7    5040  284.35    5045  284.09
  5054.1  284.59  5064.2   284.5  5074.2  284.67  5124.3  286.48  5184.4  289.09
  5192.7  289.65  5214.5  290.41  5254.6  292.64  5274.6  293.47  5290.3  294.39
#Mann= 3 ,-1 , 0
  4779.4     .05       0    5001     .03       0    5007     .05       0
Bank Sta=5001,5007
XS Rating Curve= 0 ,0
Exp/Cntr=0.3,0.1

Type RM Length L Ch R = 1 ,844     ,49,49,49
BEGIN DESCRIPTION:
Mapping XS f45a5940
END DESCRIPTION:
XS GIS Cut Line= 2
       3625376.7     10263486.42      3625782.97     10263349.26
#Sta/Elev= 30
  4802.6  279.32  4818.9  278.78  4833.9  278.92  4850.5  278.28  4865.4   278.3
  4882.2  277.56  4928.3  277.23  4945.5  276.55  4954.5  276.57  4959.8  276.02
  4977.2  276.23    4986  276.83  4988.2  275.63    4991  275.13  4994.2  275.63
  4998.3  276.13  5008.8  276.13  5017.4  278.11  5022.7   276.4  5029.9  278.49
  5048.9  279.32  5054.2  278.92  5085.6  281.46  5117.1  283.27  5143.3   283.9
  5148.6  284.45  5174.7  284.91    5180   285.4  5198.8  285.56  5231.4  286.51
#Mann= 3 ,-1 , 0
  4802.6     .05       0  4988.2     .03       0  4994.2     .05       0
Bank Sta=4988.2,4994.2
XS Rating Curve= 0 ,0
Exp/Cntr=0.3,0.1

Type RM Length L Ch R = 1 ,795     ,202,202,202
BEGIN DESCRIPTION:
Mapping XS 078a68ee
END DESCRIPTION:
XS GIS Cut Line= 2
      3625361.06     10263538.51      3625812.42     10263394.42
#Sta/Elev= 30
  4769.4  279.99    4802  279.65  4845.3  278.43  4854.5  278.98  4872.2  278.13
  4877.5  278.33    4886  277.22  4896.5  276.72  4917.5  276.69  4936.6  275.87
  4941.8  276.67  4959.5  275.73  4968.8  275.85    4974  276.88    4998  275.41
  5000.7  274.91    5004  275.41  5011.9  277.51  5022.4   277.8  5038.4  277.62
  5043.6  278.68  5064.4  279.59  5070.6  280.69  5085.4  281.57  5102.8  283.16
  5140.2  284.45  5148.4  284.32  5167.1  285.23  5204.6  286.07  5243.2  287.64
#Mann= 3 ,-1 , 0
  4769.4     .05       0    4998     .03       0    5004     .05       0
Bank Sta=4998,5004
XS Rating Curve= 0 ,0
Exp/Cntr=0.3,0.1

Type RM Length L Ch R = 1 ,593     ,188,188,188
BEGIN DESCRIPTION:
Mapping XS ead82afc
END DESCRIPTION:
XS GIS Cut Line= 2
      3625394.03     10263705.18      3625782.99     10263592.31
#Sta/Elev= 30
  4836.2  276.22  4868.7   276.3  4896.7  275.78  4959.1  276.64  4969.4  276.23
    4980  273.87 4994.32  271.87  5000.5  271.75 5005.16   272.1  5008.2  272.97
  5013.4  273.31  5021.6  274.54    5032  275.13  5041.7  274.98  5052.9  275.28
  5063.3  274.74  5073.7  275.18  5080.5  276.63  5094.5  278.17  5104.9  279.09
  5125.7  280.31  5152.8   280.3    5158  280.66  5163.5   280.6  5177.8  280.55
  5186.4  280.69  5191.6  281.08  5219.5  281.07  5230.4  281.54  5241.2  281.51
#Mann= 5 ,-1 , 0
  4836.2     .07       0    4980     .12       0    4980     .05       0
  5013.4     .07       0  5163.5     .05       0
Bank Sta=4980,5013.4
XS Rating Curve= 0 ,0
Exp/Cntr=0.3,0.1

Type RM Length L Ch R = 1 ,405     ,344,344,344
BEGIN DESCRIPTION:
Mapping XS 981a0b67
END DESCRIPTION:
XS GIS Cut Line= 2
      3625440.97     10263852.73      3625867.57     10263727.87
#Sta/Elev= 30
  4869.5  274.42    4894   274.6  4922.2  274.51  4927.4  274.71  4943.6     274
    4966   273.4  4985.3  271.67  4994.2  271.03 5009.63  270.56  5032.6  270.32
 5051.48  270.54  5066.3  271.16  5071.5  271.66  5099.7  272.06  5104.9  272.78
  5110.3   273.2  5138.4  274.04  5143.6  274.52  5171.8  274.75    5177  275.17
  5183.3  275.34  5204.1  275.23  5210.4   274.9  5215.9  275.21  5243.9  275.29
  5249.1  275.52    5277  275.27  5282.5  275.38  5308.3  276.94    5314  277.03
#Mann= 4 ,-1 , 0
  4869.5     .05       0  4985.3     .03       0  5071.5     .05       0
  5215.9     .05       0
Bank Sta=4985.3,5071.5
XS Rating Curve= 0 ,0
Exp/Cntr=0.3,0.1

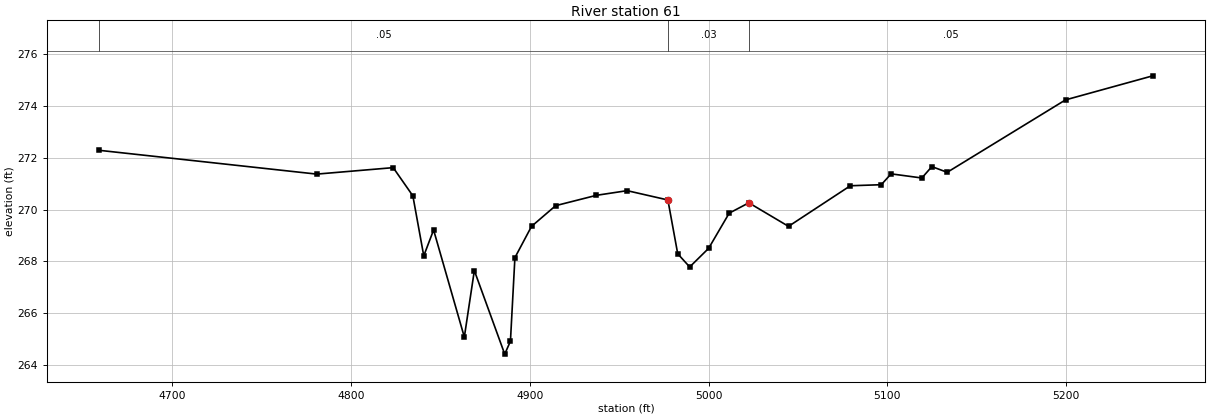
Type RM Length L Ch R = 1 ,61      ,0,0,0
BEGIN DESCRIPTION:
UNT04879 IN WICK 1.0
END DESCRIPTION:
XS GIS Cut Line= 4
      3625510.45     10264012.61      3625645.92     10264016.52
       3625949.3     10263873.29      3625979.26     10263758.66
#Sta/Elev= 30
    4659  272.29  4780.7  271.37  4823.5  271.62  4834.5  270.53  4840.6  268.21
  4846.1  269.21  4863.3  265.07  4868.9  267.64  4885.9  264.41  4889.1  264.91
  4891.6  268.14  4900.9  269.35  4914.4  270.15  4937.2  270.55  4954.4  270.73
  4977.2  270.37  4982.7  268.29  4989.4  267.78    5000   268.5  5011.5  269.86
  5022.5  270.26  5044.7  269.35  5079.3  270.92  5096.6  270.96  5102.1  271.38
  5119.3  271.22  5124.9  271.66  5133.5  271.44  5199.7  274.24  5248.5  275.17
#Mann= 3 ,-1 , 0
    4659     .05       0  4977.2     .03       0  5022.5     .05       0
Bank Sta=4977.2,5022.5
XS Rating Curve= 0 ,0
Exp/Cntr=0.3,0.1

Chan Stop Cuts=-1
Use User Specified Reach Order=0
Composite Channel Slope=5