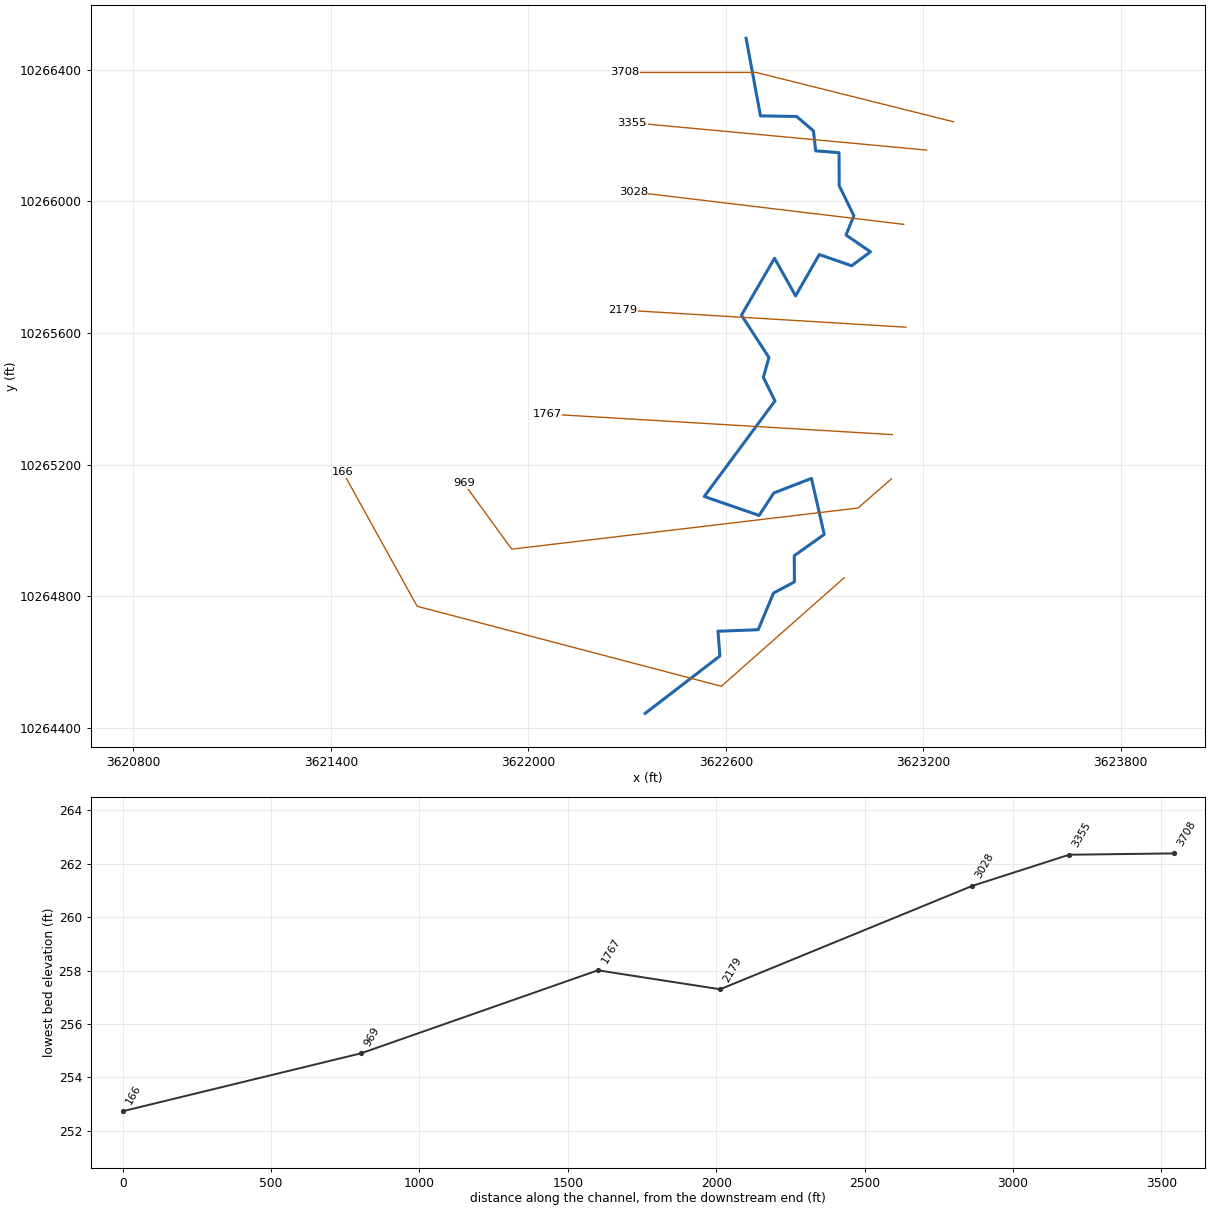
--- UNT04881 IN WICK.prj (project) ---

Proj Title=UNT04881 IN WICK Base Level Engineering
Current Plan=p01
Default Exp/Contr=0.3,0.1
English Units
Geom File=g01
Flow File=f01
Plan File=p01
Y Axis Title=Elevation
X Axis Title(PF)=Main Channel Distance
X Axis Title(XS)=Station
BEGIN DESCRIPTION:
UNT04881 IN WICK
END DESCRIPTION:
DSS Export Rating Curves= 0
DSS Export Rating Curve Sorted= 0
DSS Export Volume Flow Curves= 0
DXF OffsetX= 0
DXF OffsetY= 0
DXF ScaleX= 1
DXF ScaleY= 10

--- UNT04881 IN WICK.p01 (plan) ---

Plan Title=Multiple Run
Short Identifier=Multiple
Geom File=g01
Flow File=f01
Subcritical Flow
K Sum by GR= 0
Std Step Tol= 0.01
Critical Tol= 0.01
Num of Std Step Trials= 20
Max Error Tol= 0.3
Flow Tol Ratio= 0.001
Split Flow NTrial= 30
Split Flow Tol= 0.02
Split Flow Ratio= 0.02
Log Output Level= 0
Friction Slope Method= 1
Unsteady Friction Slope Method= 2
Unsteady Bridges Friction Slope Method= 1
Parabolic Critical Depth
Global Vel Dist=  1 , 1 , 1
Global Log Level= 0
CheckData=True
Encroach Param= -1, 0, 0, 0
BEGIN DESCRIPTION:
Multiple Run
END DESCRIPTION:

--- UNT04881 IN WICK.f01 (steady flow) ---

Flow Title=Multiple
Number of Profiles=7
Profile Names=10-year,25-year,50-year,1pct_min,100-year,1pct_plu,500-year
River Rch & RM= UNT04881 IN WICK,Reach-1,3708
     478     633     756     664     898    1214    1265
Boundary for River Rch & Prof#=UNT04881 IN WICK,Reach-1,1
Up Type=0
Dn Type=3
Dn Slope=0.005
Boundary for River Rch & Prof#=UNT04881 IN WICK,Reach-1,2
Up Type=0
Dn Type=3
Dn Slope=0.005
Boundary for River Rch & Prof#=UNT04881 IN WICK,Reach-1,3
Up Type=0
Dn Type=3
Dn Slope=0.005
Boundary for River Rch & Prof#=UNT04881 IN WICK,Reach-1,4
Up Type=0
Dn Type=3
Dn Slope=0.005
Boundary for River Rch & Prof#=UNT04881 IN WICK,Reach-1,5
Up Type=0
Dn Type=3
Dn Slope=0.005
Boundary for River Rch & Prof#=UNT04881 IN WICK,Reach-1,6
Up Type=0
Dn Type=3
Dn Slope=0.005
Boundary for River Rch & Prof#=UNT04881 IN WICK,Reach-1,7
Up Type=0
Dn Type=3
Dn Slope=0.005

--- UNT04881 IN WICK.g01 (geometry) ---

Geom Title=Existing Conditions
Program Version=4.10

River Reach=UNT04881 IN WICK,Reach-1
Reach XY= 30
      3622661.79     10266495.21      3622705.46     10266259.58
      3622815.23     10266257.74      3622866.42     10266213.99
      3622873.14     10266153.39       3622944.1     10266147.74
      3622944.68     10266047.54      3622989.27     10265956.01
      3622965.29     10265897.53      3623039.65     10265846.53
      3622982.49     10265804.13      3622884.01     10265838.12
       3622812.1     10265712.66      3622748.09     10265826.97
      3622647.61     10265653.92      3622731.16     10265525.32
      3622714.23     10265464.99      3622749.39     10265393.38
      3622534.56     10265102.93      3622701.17     10265045.41
       3622745.9     10265113.65      3622860.33     10265157.88
      3622899.19     10264987.67      3622808.12     10264922.98
      3622808.46     10264843.15      3622745.13     10264809.67
      3622698.51      10264698.1      3622576.27     10264693.44
      3622582.15      10264618.3      3622355.01     10264443.87

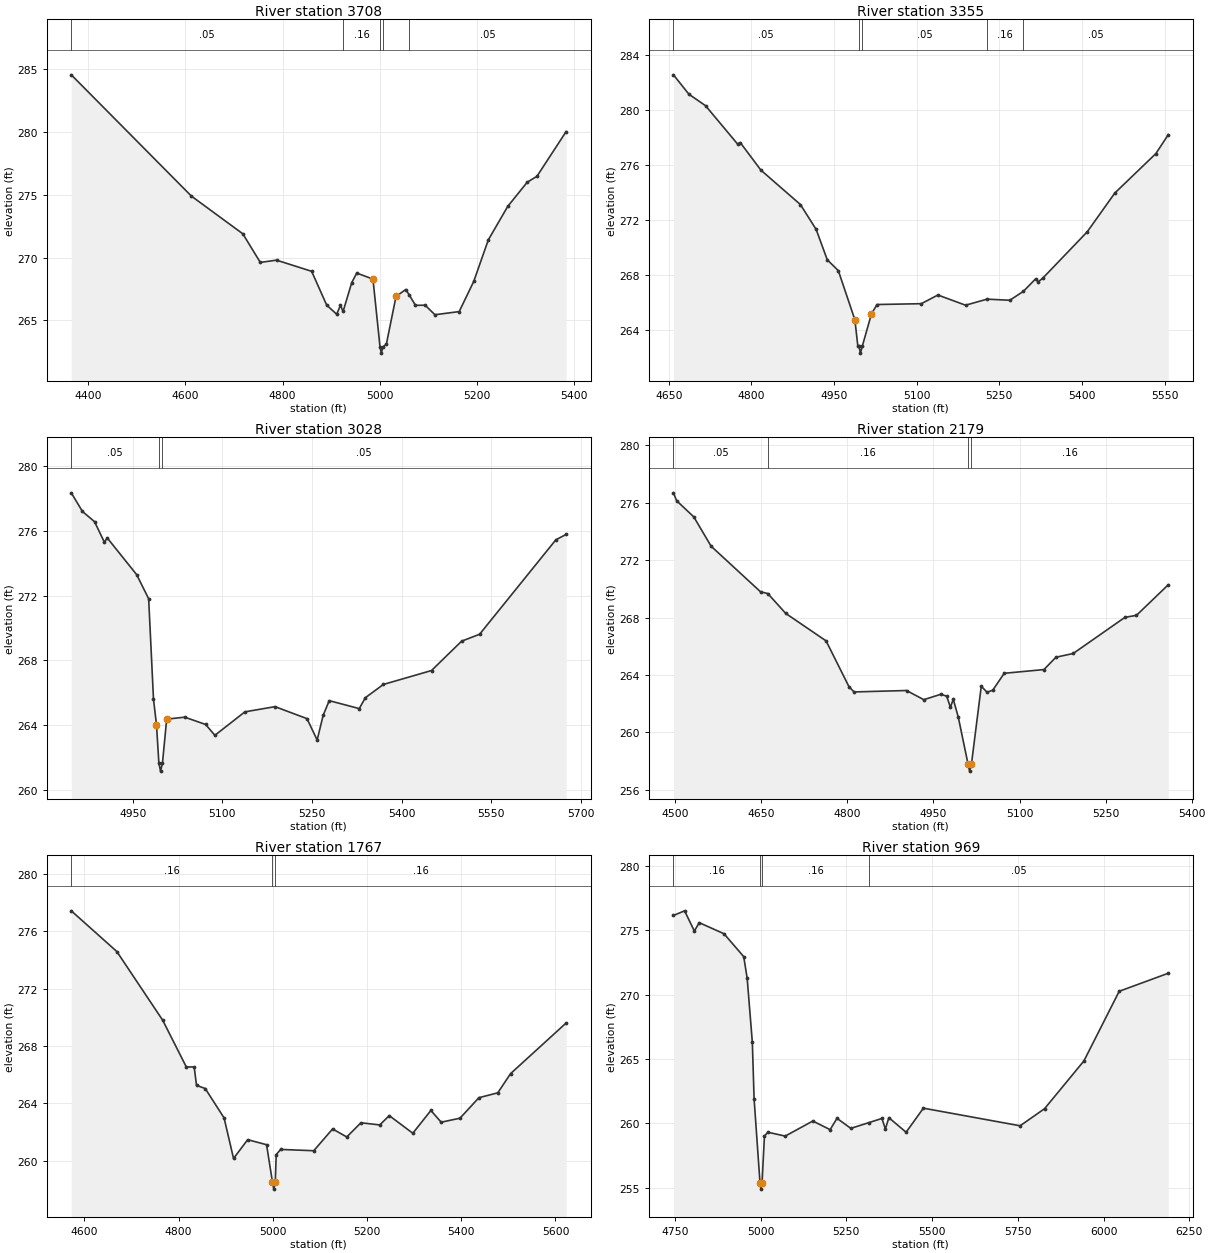
Type RM Length L Ch R = 1 ,3708    ,353,353,353
BEGIN DESCRIPTION:
UNT04881 IN WICK 6.0
END DESCRIPTION:
XS GIS Cut Line= 3
      3623292.12     10266241.64      3622692.11     10266391.64
      3622292.09     10266391.64
#Sta/Elev= 30
  4364.9  284.57  4612.3   274.9    4718   271.9    4754  269.62  4787.5   269.8
  4859.7  268.91  4890.6  266.22  4911.2  265.49    4919   266.2  4924.4  265.71
  4942.2  268.01  4952.5  268.77  4985.9  268.29  5000.4  262.89  5003.1  262.39
  5006.4  262.89  5013.4  263.09  5033.4  266.91  5053.4  267.46  5060.2  267.05
  5073.4   266.2  5093.4  266.21  5113.4  265.45  5163.4   265.7  5193.4  268.11
  5223.4  271.42  5263.4  274.09  5303.4  276.01  5323.4  276.48  5383.4  280.04
#Mann= 5 ,-1 , 0
  4364.9     .05       0  4924.4     .16       0  5000.4     .07       0
  5006.4     .16       0  5060.2     .05       0
Bank Sta=4985.9,5033.4
XS Rating Curve= 0 ,0
Exp/Cntr=0.3,0.1

Type RM Length L Ch R = 1 ,3355    ,327,327,327
BEGIN DESCRIPTION:
UNT04881 IN WICK 5.0
END DESCRIPTION:
XS GIS Cut Line= 2
       3623210.1     10266155.61      3622315.66     10266238.81
#Sta/Elev= 30
  4658.4  282.55  4686.5  281.14  4716.6  280.31  4774.7  277.53  4779.7  277.63
  4817.1  275.63  4888.9  273.13  4917.5  271.32  4937.6  269.12  4957.7  268.33
  4987.8  264.76  4993.1  262.86  4995.2  262.84  4997.9  262.34  5001.2  262.84
  5017.9  265.19    5028  265.87  5108.3  265.93  5138.5  266.56  5188.7  265.82
  5227.8  266.26    5269  266.18  5293.8  266.83  5315.8  267.73  5320.8  267.52
  5329.3   267.8  5409.6  271.15  5459.8  273.97  5534.2  276.83  5556.7   278.2
#Mann= 5 ,-1 , 0
  4658.4     .05       0  4995.2     .03       0  5001.2     .05       0
  5227.8     .16       0  5293.8     .05       0
Bank Sta=4987.8,5017.9
XS Rating Curve= 0 ,0
Exp/Cntr=0.3,0.1

Type RM Length L Ch R = 1 ,3028    ,849,849,849
BEGIN DESCRIPTION:
UNT04881 IN WICK 4.0
END DESCRIPTION:
XS GIS Cut Line= 2
      3623140.69     10265929.91      3622318.47     10266028.48
#Sta/Elev= 30
  4847.1  278.35  4865.8   277.2    4886  276.57  4902.4  275.31  4907.4  275.56
  4956.5   273.3  4976.6  271.81  4984.7  265.61  4989.7  264.04  4993.7  261.67
  4996.5  261.17  4999.7  261.67  5006.8  264.38    5037   264.5    5072  264.05
  5087.4  263.38  5137.7  264.83  5188.1  265.15  5241.6  264.41  5258.6  263.09
  5268.7  264.62  5278.8  265.52  5329.1  265.03  5339.2   265.7  5369.4  266.52
    5450  267.38  5500.3  269.19  5530.5  269.62  5658.1  275.45  5675.2  275.78
#Mann= 3 ,-1 , 0
  4847.1     .05       0  4993.7     .03       0  4999.7     .05       0
Bank Sta=4989.7,5006.8
XS Rating Curve= 0 ,0
Exp/Cntr=0.3,0.1

Type RM Length L Ch R = 1 ,2179    ,412,412,412
BEGIN DESCRIPTION:
UNT04881 IN WICK 3.0
END DESCRIPTION:
XS GIS Cut Line= 2
      3623147.58     10265617.42      3622286.76     10265669.48
#Sta/Elev= 30
  4496.8   276.7  4502.3  276.15  4532.3  275.02  4562.4  272.98  4648.6   269.8
  4661.2  269.68  4692.6  268.29  4762.8  266.38  4802.8  263.18  4811.6  262.82
    4903  262.92  4933.1  262.28  4963.1  262.66  4973.1  262.52  4979.5  261.75
  4984.5  262.31  4993.2  261.07  5010.2   257.8    5013   257.3  5016.2   257.8
  5033.3  263.22  5043.3   262.8  5053.3  262.94  5073.3  264.12  5142.5  264.38
  5163.5  265.24  5193.5   265.5  5283.7  268.02  5303.8  268.16  5359.2  270.29
#Mann= 4 ,-1 , 0
  4496.8     .05       0  4661.2     .16       0  5010.2     .07       0
  5016.2     .16       0
Bank Sta=5010.2,5016.2
XS Rating Curve= 0 ,0
Exp/Cntr=0.3,0.1

Type RM Length L Ch R = 1 ,1767    ,798,798,798
BEGIN DESCRIPTION:
UNT04881 IN WICK 2.0
END DESCRIPTION:
XS GIS Cut Line= 2
      3623105.96     10265291.02      3622057.33     10265353.53
#Sta/Elev= 30
    4572  277.43  4668.7  274.59  4766.2  269.79  4816.3  266.53  4832.9  266.54
  4837.9  265.25  4856.4  265.03  4896.4  262.98  4916.5  260.15  4946.5  261.46
  4986.6  261.11  4999.1  258.51  5001.9  258.01  5005.1  258.51  5007.1  260.42
  5016.6  260.78  5086.8  260.69  5126.8  262.21  5156.9  261.65  5186.9  262.64
    5227  262.49  5247.1  263.14  5297.1  261.91  5335.5   263.5  5357.3  262.68
  5397.3  262.96  5437.4  264.39  5477.5  264.73  5504.7  266.07  5622.5   269.6
#Mann= 3 ,-1 , 0
    4572     .16       0  4999.1     .07       0  5005.1     .16       0
Bank Sta=4999.1,5005.1
XS Rating Curve= 0 ,0
Exp/Cntr=0.3,0.1

Type RM Length L Ch R = 1 ,969     ,803,803,803
BEGIN DESCRIPTION:
Mapping XS 18049040
END DESCRIPTION:
XS GIS Cut Line= 4
      3623103.26      10265156.4      3623001.71     10265067.86
      3621949.62     10264942.86      3621803.76     10265143.42
#Sta/Elev= 30
  4746.2  276.16  4778.6  276.52  4807.1  274.95  4821.3   275.6  4893.5  274.74
    4951  272.96  4961.1  271.27  4976.1  266.31  4981.2  261.94  4998.4   255.4
  5001.1   254.9  5004.4   255.4  5011.4  259.03  5021.5  259.32  5071.9  259.02
  5152.4  260.19  5202.8  259.52  5222.9   260.4  5263.2  259.62  5316.2  260.07
  5353.8  260.39  5363.9  259.57    5374  260.45  5424.3  259.32  5474.7  261.19
  5756.6  259.82  5827.9  261.15  5942.6  264.86  6045.4  270.27  6188.4  271.67
#Mann= 4 ,-1 , 0
  4746.2     .16       0  4998.4     .07       0  5004.4     .16       0
  5316.2     .05       0
Bank Sta=4998.4,5004.4
XS Rating Curve= 0 ,0
Exp/Cntr=0.3,0.1

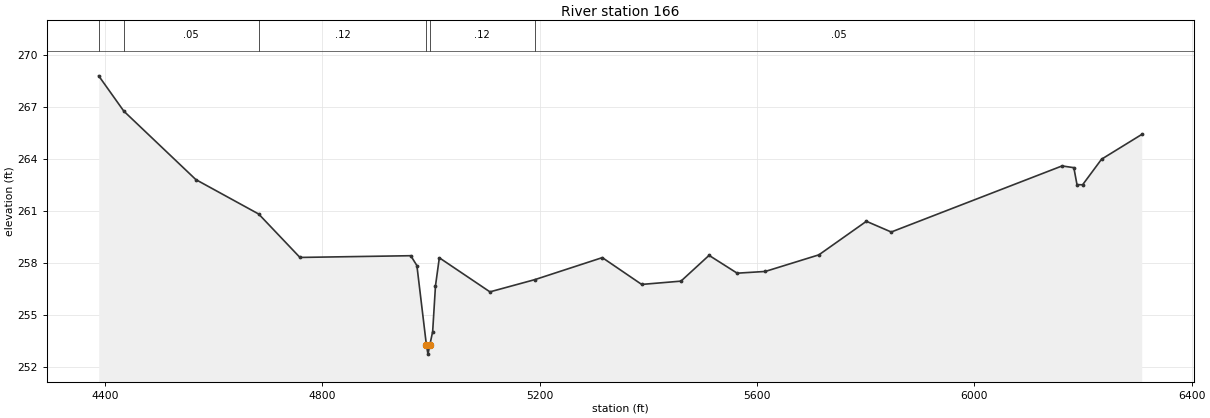
Type RM Length L Ch R = 1 ,166     ,0,0,0
BEGIN DESCRIPTION:
UNT04881 IN WICK 1.0
END DESCRIPTION:
XS GIS Cut Line= 4
      3622959.82     10264856.11      3622586.53     10264526.23
      3621662.06     10264769.29       3621436.9      10265176.3
#Sta/Elev= 30
  4388.9  268.82  4435.1  266.78  4567.7  262.82  4683.3  260.83  4759.2  258.32
  4963.1  258.42  4974.4  257.85    4992  253.23  4994.8  252.73    4998  253.23
  5003.4  254.03  5008.6  256.68  5015.7   258.3  5108.8  256.33  5191.7  257.04
  5315.6  258.31    5388  256.76  5460.3  256.95    5512  258.44  5563.7  257.41
  5615.4  257.51  5714.1  258.47  5801.5  260.41  5847.2  259.79  6161.5  263.61
  6183.2  263.51    6189  262.53  6199.3  262.52  6234.2     264  6308.1  265.43
#Mann= 6 ,-1 , 0
  4388.9     .16       0  4435.1     .05       0  4683.3     .12       0
    4992     .07       0    4998     .12       0  5191.7     .05       0
Bank Sta=4992,4998
XS Rating Curve= 0 ,0
Exp/Cntr=0.3,0.1

Chan Stop Cuts=-1
Use User Specified Reach Order=0
Composite Channel Slope=5