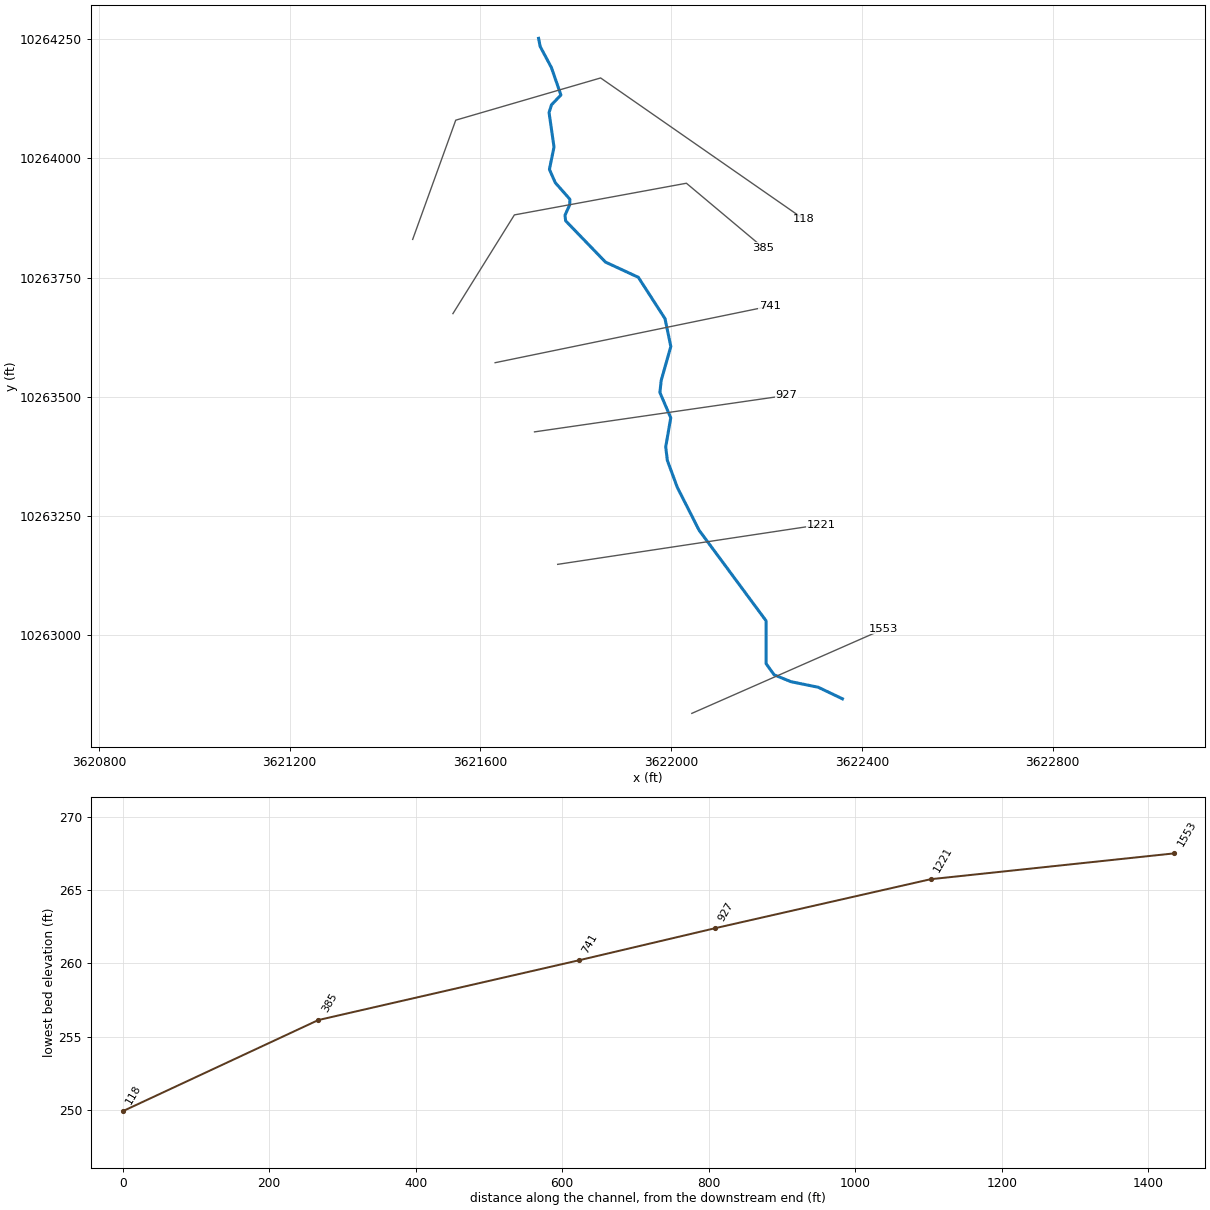
--- UNT04883 IN WICK.prj (project) ---

Proj Title=UNT04883 IN WICK Base Level Engineering
Current Plan=p01
Default Exp/Contr=0.3,0.1
English Units
Geom File=g01
Flow File=f01
Plan File=p01
BEGIN DESCRIPTION:
UNT04883 IN WICK
END DESCRIPTION:

--- UNT04883 IN WICK.p01 (plan) ---

Plan Title=Multiple Run
Short Identifier=Multiple
Geom File=g01
Flow File=f01
Subcritical Flow
K Sum by GR= 0
Std Step Tol= 0.01
Critical Tol= 0.01
Num of Std Step Trials= 20
Max Error Tol= 0.3
Flow Tol Ratio= 0.001
Split Flow NTrial= 30
Split Flow Tol= 0.02
Split Flow Ratio= 0.02
Log Output Level= 0
Friction Slope Method= 1
Unsteady Friction Slope Method= 2
Unsteady Bridges Friction Slope Method= 1
Parabolic Critical Depth
Global Vel Dist=  1 , 1 , 1
Global Log Level= 0
CheckData=True
Encroach Param= -1, 0, 0, 0
BEGIN DESCRIPTION:
Multiple Run
END DESCRIPTION:

--- UNT04883 IN WICK.f01 (steady flow) ---

Flow Title=Multiple
Number of Profiles=7
Profile Names=10-year,25-year,50-year,1pct_min,100-year,1pct_plu,500-year
River Rch & RM= UNT04883 IN WICK,Reach-1,1553
     158     196     224     190     256     347     334
Boundary for River Rch & Prof#=UNT04883 IN WICK,Reach-1,1
Up Type=0
Dn Type=3
Dn Slope=0.005
Boundary for River Rch & Prof#=UNT04883 IN WICK,Reach-1,2
Up Type=0
Dn Type=3
Dn Slope=0.005
Boundary for River Rch & Prof#=UNT04883 IN WICK,Reach-1,3
Up Type=0
Dn Type=3
Dn Slope=0.005
Boundary for River Rch & Prof#=UNT04883 IN WICK,Reach-1,4
Up Type=0
Dn Type=3
Dn Slope=0.005
Boundary for River Rch & Prof#=UNT04883 IN WICK,Reach-1,5
Up Type=0
Dn Type=3
Dn Slope=0.005
Boundary for River Rch & Prof#=UNT04883 IN WICK,Reach-1,6
Up Type=0
Dn Type=3
Dn Slope=0.005
Boundary for River Rch & Prof#=UNT04883 IN WICK,Reach-1,7
Up Type=0
Dn Type=3
Dn Slope=0.005

--- UNT04883 IN WICK.g01 (geometry) ---

Geom Title=Existing Conditions

River Reach=UNT04883 IN WICK,Reach-1
Reach XY= 30
      3622359.27     10262866.72      3622308.57     10262890.90
      3622251.27     10262902.62      3622216.12     10262916.94
      3622199.19     10262940.38      3622199.19     10263030.22
      3622058.57     10263220.33      3622012.99     10263310.17
      3621992.11     10263366.64      3621988.71     10263394.84
      3621999.27     10263455.93      3621976.48     10263508.97
      3621979.26     10263534.32      3621999.40     10263605.50
      3621987.24     10263663.83      3621931.29     10263750.52
      3621862.41     10263782.46      3621778.86     10263869.01
      3621777.54     10263880.64      3621787.36     10263902.60
      3621787.76     10263914.20      3621757.05     10263949.08
      3621744.85     10263976.85      3621754.49     10264023.70
      3621744.07     10264095.92      3621749.28     10264112.24
      3621768.91     10264132.80      3621749.13     10264190.15
      3621725.44     10264234.60      3621722.11     10264251.64

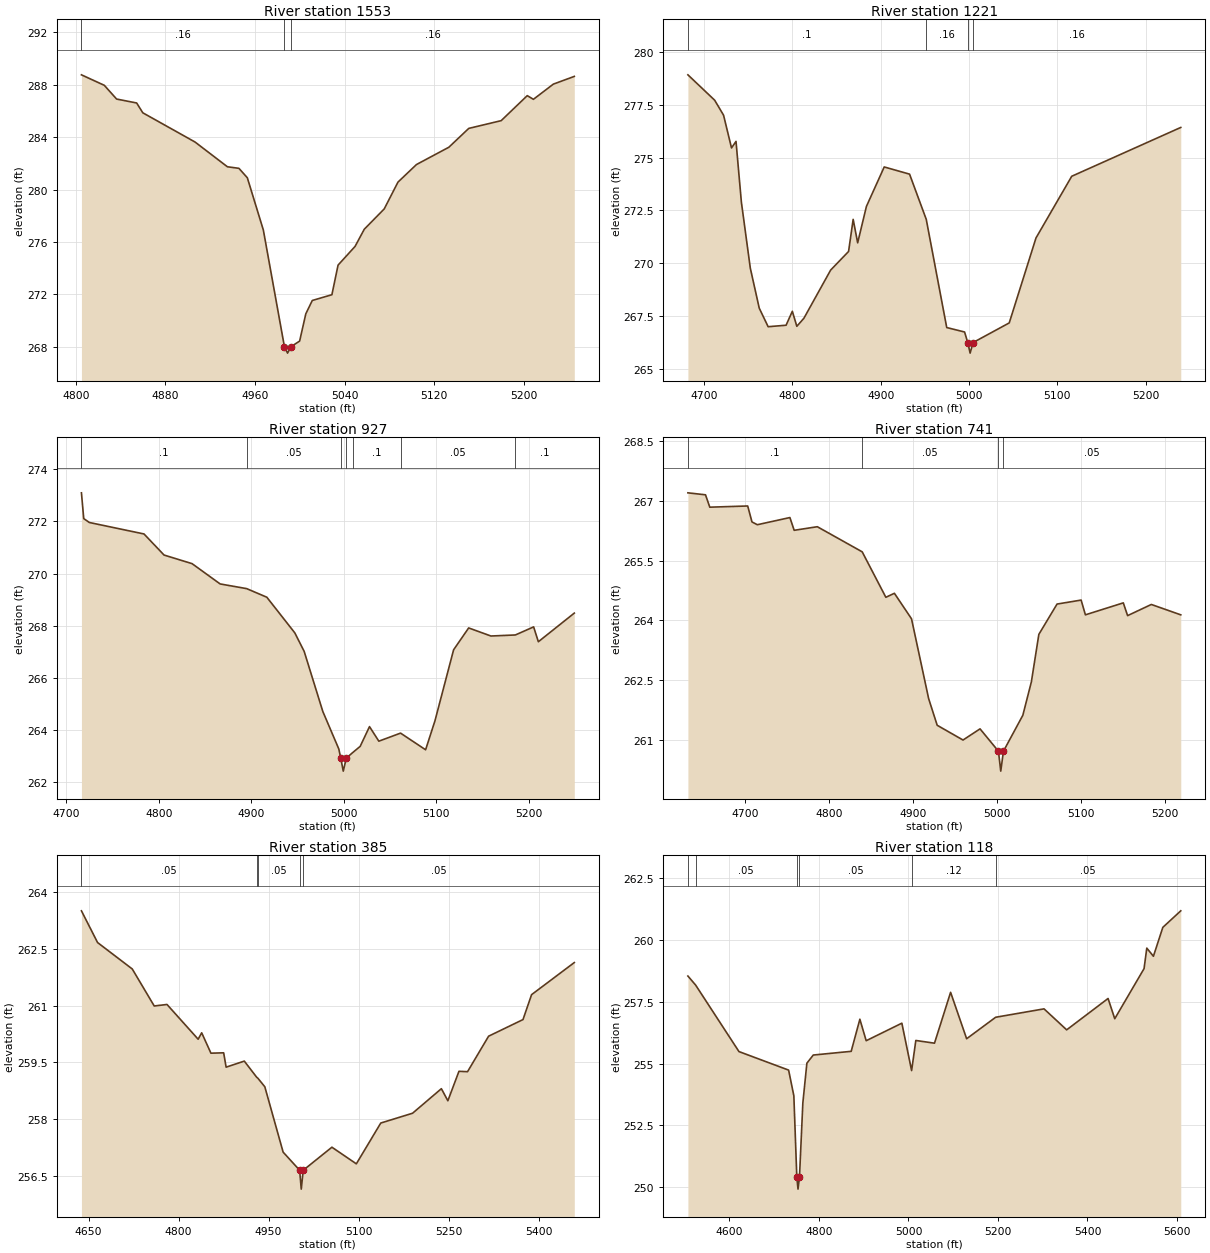
Type RM Length L Ch R = 1,1553,332,332,332
BEGIN DESCRIPTION:
UNT04883 IN WICK 3.0
END DESCRIPTION:
XS GIS Cut Line= 2
      3622043.44     10262836.16      3622446.23     10263013.25
#Sta/Elev= 30
  4805.1  288.76  4825.5  287.96  4836.5  286.91  4854.4  286.61  4859.9  285.86
  4906.5  283.63  4935.4  281.74  4945.7  281.62  4953.2  280.90  4967.5  276.91
  4986.3  268.01  4989.1  267.51  4992.3  268.01  4999.9  268.43  5005.4  270.51
  5011.2  271.53  5028.7  271.97  5034.2  274.23  5049.4  275.66  5057.6  276.97
  5075.4  278.52  5087.7  280.57  5104.2  281.91  5133.1  283.23  5150.9  284.67
  5179.8  285.26  5203.1  287.17  5208.6  286.89  5226.4  288.05  5245.1  288.64
#Mann=3,-1,0
  4805.1    0.16       0  4986.3    0.07       0  4992.3    0.16       0
Bank Sta=4986.3,4992.3
Exp/Cntr=0.3,0.1

Type RM Length L Ch R = 1,1221,294,294,294
BEGIN DESCRIPTION:
UNT04883 IN WICK 2.0
END DESCRIPTION:
XS GIS Cut Line= 2
      3621762.19     10263148.66      3622314.24     10263231.99
#Sta/Elev= 30
  4681.6  278.92  4711.9  277.72  4722.0  277.01  4731.0  275.46  4736.1  275.77
  4742.2  272.89  4752.3  269.77  4762.4  267.88  4772.5  267.00  4792.8  267.07
  4799.9  267.73  4805.0  267.02  4813.0  267.40  4843.3  269.68  4863.6  270.56
  4868.8  272.08  4873.9  270.97  4883.8  272.69  4904.0  274.56  4932.7  274.22
  4951.6  272.08  4974.8  266.96  4995.0  266.75  4998.6  266.25  5001.3  265.75
  5004.6  266.25  5045.6  267.18  5075.9  271.20  5116.4  274.12  5239.9  276.43
#Mann=4,-1,0
  4681.6     0.1       0  4951.6    0.16       0  4998.6    0.07       0
  5004.6    0.16       0
Bank Sta=4998.6,5004.6
Exp/Cntr=0.3,0.1

Type RM Length L Ch R = 1,927,186,186,186
BEGIN DESCRIPTION:
Mapping XS 0c0f853f
END DESCRIPTION:
XS GIS Cut Line= 2
      3621713.59     10263426.44      3622241.39     10263502.83
#Sta/Elev= 30
  4716.2  273.10  4718.7  272.11  4724.8  271.96  4783.9  271.52  4805.6  270.71
  4835.9  270.38  4866.3  269.60  4895.0  269.42  4916.8  269.09  4947.1  267.72
  4957.2  267.01  4977.4  264.70  4994.7  263.26  4996.8  262.91  4999.5  262.41
  5002.8  262.91  5010.3  263.14  5017.8  263.36  5027.9  264.12  5038.0  263.56
  5061.5  263.87  5088.6  263.23  5098.7  264.34  5118.9  267.07  5135.2  267.91
  5159.3  267.60  5185.7  267.64  5205.5  267.95  5210.6  267.38  5249.5  268.48
#Mann=7,-1,0
  4716.2     0.1       0  4895.0    0.05       0  4996.8   0.035       0
  5002.8    0.05       0  5010.3     0.1       0  5061.5    0.05       0
  5185.7     0.1       0
Bank Sta=4996.8,5002.8
Exp/Cntr=0.3,0.1

Type RM Length L Ch R = 1,741,356,356,356
BEGIN DESCRIPTION:
Mapping XS 03cdb93d
END DESCRIPTION:
XS GIS Cut Line= 2
      3621631.00     10263571.49      3622206.53     10263689.98
#Sta/Elev= 30
  4631.4  267.20  4652.4  267.15  4657.5  266.84  4702.7  266.87  4707.8  266.47
  4714.2  266.40  4753.0  266.58  4758.1  266.26  4785.7  266.35  4839.2  265.72
  4867.4  264.58  4877.6  264.68  4898.0  264.04  4918.4  262.04  4928.6  261.37
  4959.4  261.00  4979.7  261.28  5001.6  260.72  5004.4  260.22  5007.6  260.72
  5030.7  261.62  5040.9  262.46  5049.8  263.65  5071.5  264.41  5100.2  264.51
  5105.3  264.14  5150.5  264.44  5155.6  264.12  5183.9  264.40  5219.0  264.14
#Mann=4,-1,0
  4631.4     0.1       0  4839.2    0.05       0  5001.6   0.035       0
  5007.6    0.05       0
Bank Sta=5001.6,5007.6
Exp/Cntr=0.3,0.1

Type RM Length L Ch R = 1,385,267,267,267
BEGIN DESCRIPTION:
Mapping XS 056a892a
END DESCRIPTION:
XS GIS Cut Line= 4
      3621542.51     10263674.39      3621671.40     10263881.39
      3622032.08     10263947.80      3622193.52     10263812.40
#Sta/Elev= 30
  4638.2  263.51  4665.1  262.67  4722.9  261.97  4759.5  260.99  4780.8  261.03
  4832.7  260.11  4838.6  260.28  4854.0  259.74  4875.2  259.75  4879.3  259.37
  4909.6  259.53  4930.4  259.10  4932.1  259.08  4943.8  258.85  4974.3  257.12
  5001.8  256.64  5004.5  256.14  5007.8  256.64  5055.6  257.25  5096.3  256.81
  5137.0  257.89  5190.0  258.15  5238.0  258.80  5248.8  258.48  5267.3  259.26
  5281.6  259.25  5316.7  260.19  5374.0  260.63  5388.3  261.29  5459.5  262.14
#Mann=5,-1,0
  4638.2    0.05       0  4930.4     0.1       0  4932.1    0.05       0
  5001.8   0.035       0  5007.8    0.05       0
Bank Sta=5001.8,5007.8
Exp/Cntr=0.3,0.1

Type RM Length L Ch R = 1,118,0,0,0
BEGIN DESCRIPTION:
UNT04883 IN WICK 1.0
END DESCRIPTION:
XS GIS Cut Line= 4
      3621458.12     10263830.02      3621548.41     10264080.04
      3621852.23     10264168.58      3622278.24     10263872.45
#Sta/Elev= 30
  4507.3  258.55  4524.7  258.18  4621.4  255.49  4732.3  254.74  4744.0  253.70
  4750.6  250.42  4753.3  249.92  4756.6  250.42  4764.1  253.41  4773.1  255.02
  4787.4  255.35  4872.1  255.50  4891.5  256.80  4905.6  255.93  4985.3  256.64
  5007.1  254.72  5016.5  255.94  5058.2  255.83  5094.2  257.89  5130.0  256.01
  5194.9  256.88  5302.9  257.22  5353.5  256.37  5446.0  257.64  5460.9  256.82
  5526.4  258.85  5532.5  259.68  5547.3  259.35  5568.3  260.52  5608.4  261.19
#Mann=6,-1,0
  4507.3     0.1       0  4524.7    0.05       0  4750.6   0.035       0
  4756.6    0.05       0  5007.1    0.12       0  5194.9    0.05       0
Bank Sta=4750.6,4756.6
Exp/Cntr=0.3,0.1

Chan Stop Cuts=-1