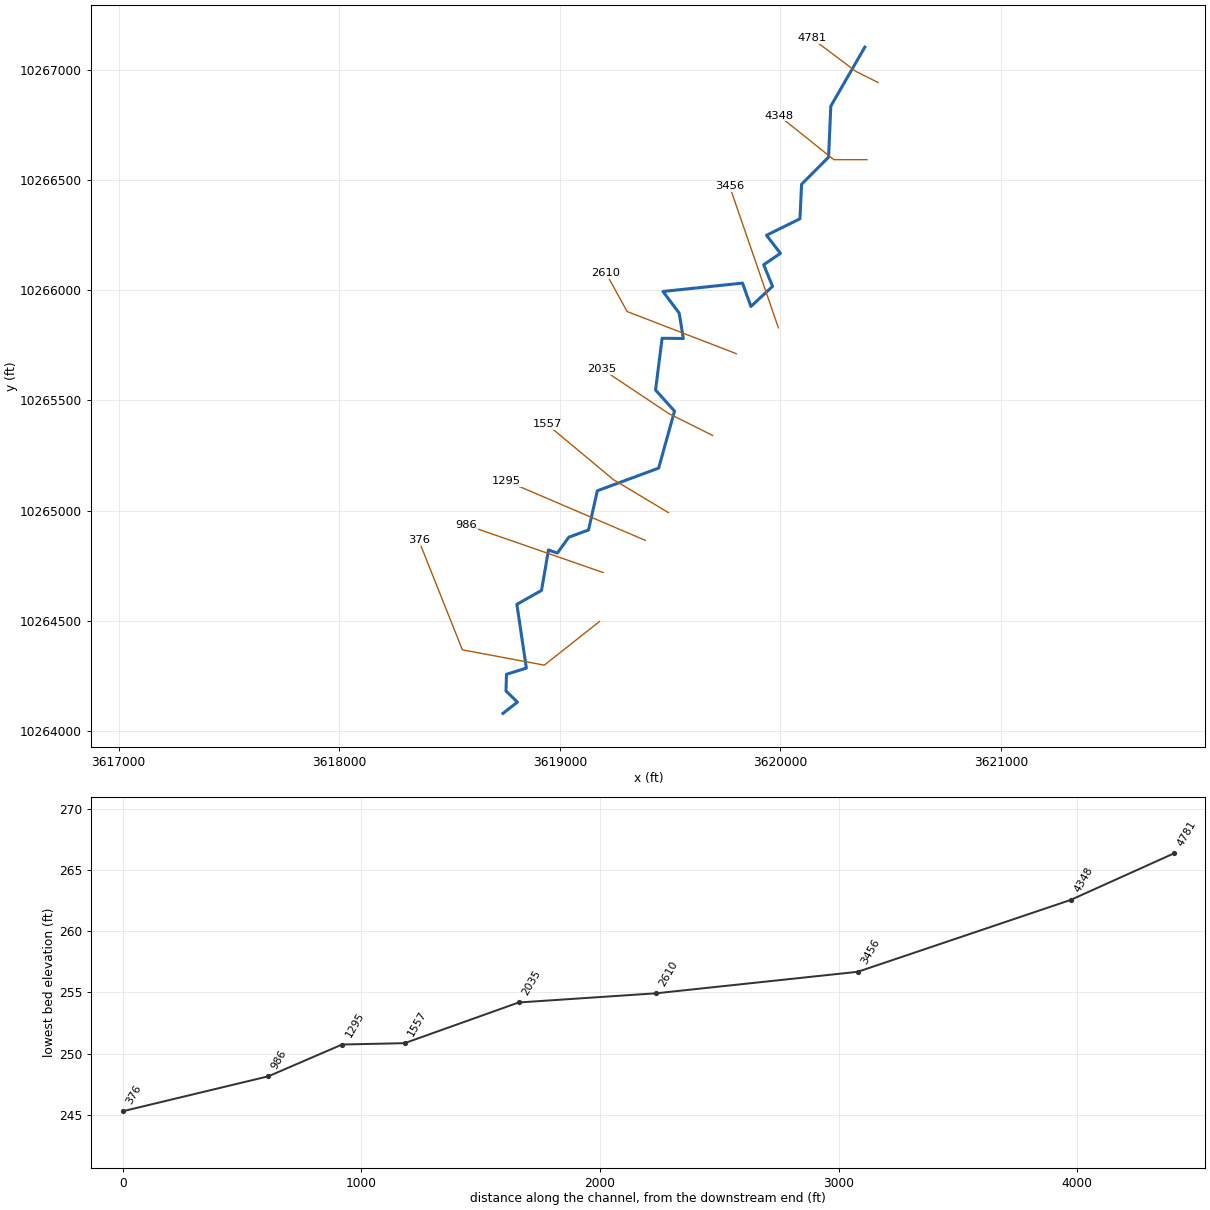
--- UNT04886 IN WICK.prj (project) ---

Proj Title=UNT04886 IN WICK Base Level Engineering
Current Plan=p01
Default Exp/Contr=0.3,0.1
English Units
Geom File=g01
Flow File=f01
Plan File=p01
BEGIN DESCRIPTION:
UNT04886 IN WICK
END DESCRIPTION:

--- UNT04886 IN WICK.p01 (plan) ---

Plan Title=Multiple Run
Short Identifier=Multiple
Geom File=g01
Flow File=f01
Subcritical Flow
K Sum by GR= 0
Std Step Tol= 0.01
Critical Tol= 0.01
Num of Std Step Trials= 20
Max Error Tol= 0.3
Flow Tol Ratio= 0.001
Split Flow NTrial= 30
Split Flow Tol= 0.02
Split Flow Ratio= 0.02
Log Output Level= 0
Friction Slope Method= 1
Unsteady Friction Slope Method= 2
Unsteady Bridges Friction Slope Method= 1
Parabolic Critical Depth
Global Vel Dist=  1 , 1 , 1
Global Log Level= 0
CheckData=True
Encroach Param= -1, 0, 0, 0
BEGIN DESCRIPTION:
Multiple Run
END DESCRIPTION:

--- UNT04886 IN WICK.f01 (steady flow) ---

Flow Title=Multiple
Number of Profiles=7
Profile Names=10-year,25-year,50-year,1pct_min,100-year,1pct_plu,500-year
River Rch & RM= UNT04886 IN WICK,Reach-1,4781
     333     431     508     440     595     805     816
Boundary for River Rch & Prof#=UNT04886 IN WICK,Reach-1,1
Up Type=0
Dn Type=3
Dn Slope=0.005
Boundary for River Rch & Prof#=UNT04886 IN WICK,Reach-1,2
Up Type=0
Dn Type=3
Dn Slope=0.005
Boundary for River Rch & Prof#=UNT04886 IN WICK,Reach-1,3
Up Type=0
Dn Type=3
Dn Slope=0.005
Boundary for River Rch & Prof#=UNT04886 IN WICK,Reach-1,4
Up Type=0
Dn Type=3
Dn Slope=0.005
Boundary for River Rch & Prof#=UNT04886 IN WICK,Reach-1,5
Up Type=0
Dn Type=3
Dn Slope=0.005
Boundary for River Rch & Prof#=UNT04886 IN WICK,Reach-1,6
Up Type=0
Dn Type=3
Dn Slope=0.005
Boundary for River Rch & Prof#=UNT04886 IN WICK,Reach-1,7
Up Type=0
Dn Type=3
Dn Slope=0.005

--- UNT04886 IN WICK.g01 (geometry) ---

Geom Title=Existing Conditions

River Reach=UNT04886 IN WICK,Reach-1
Reach XY= 30
      3620382.22     10267101.58      3620228.17     10266834.40
      3620218.08     10266602.93      3620095.62     10266480.10
      3620088.32     10266323.77      3619936.56     10266248.79
      3620000.00     10266166.99      3619923.91     10266115.34
      3619964.07     10266017.48      3619865.99     10265926.08
      3619827.83     10266032.08      3619467.17     10265994.14
      3619540.83     10265896.09      3619559.65     10265781.01
      3619463.42     10265782.02      3619433.74     10265547.35
      3619519.67     10265451.89      3619447.76     10265193.39
      3619169.77     10265090.70      3619129.92     10264913.03
      3619040.43     10264880.20      3618988.49     10264808.29
      3618948.42     10264822.47      3618916.79     10264639.01
      3618805.07     10264575.85      3618848.04     10264286.77
      3618757.98     10264258.91      3618755.73     10264183.27
      3618807.61     10264132.59      3618742.11     10264081.64

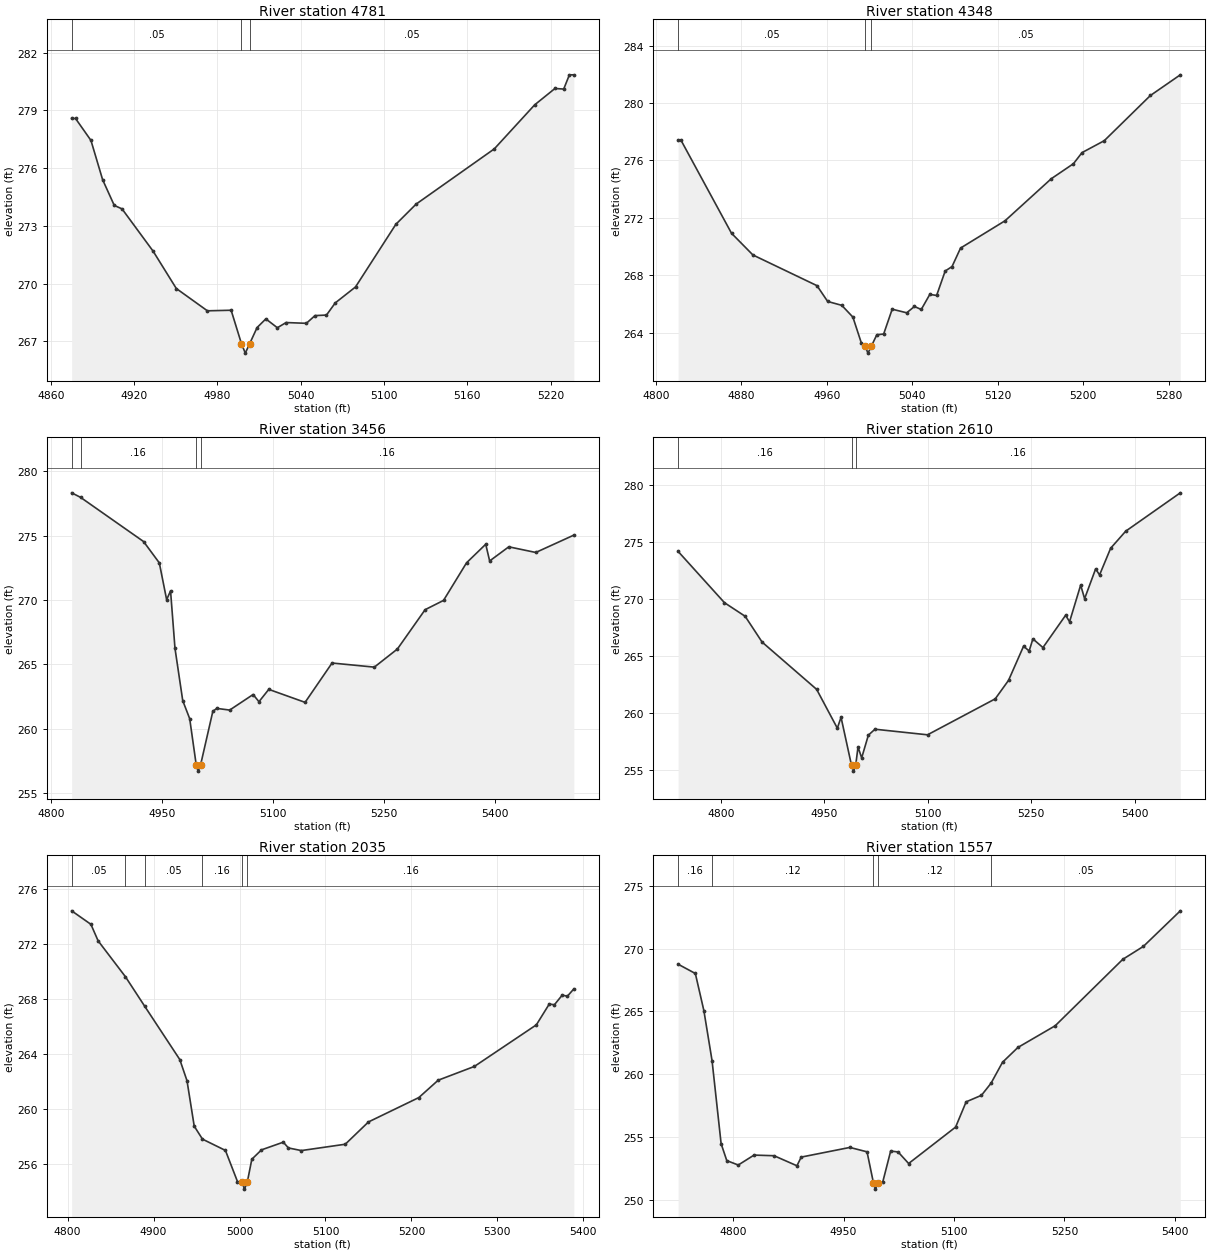
Type RM Length L Ch R = 1,4781,433,433,433
BEGIN DESCRIPTION:
UNT04886 IN WICK 9.0
END DESCRIPTION:
XS GIS Cut Line= 3
      3620442.07     10266941.66      3620342.11     10266991.64
      3620142.08     10267141.66
#Sta/Elev= 30
  4875.0  278.58  4877.8  278.58  4888.9  277.44  4897.3  275.40  4905.7  274.06
  4911.3  273.88  4933.7  271.68  4950.4  269.74  4972.8  268.58  4989.9  268.61
  4997.3  266.88  5000.1  266.38  5003.3  266.88  5008.6  267.71  5014.9  268.16
  5023.2  267.70  5029.5  267.97  5044.1  267.93  5050.3  268.33  5058.6  268.36
  5064.9  268.99  5079.5  269.82  5108.6  273.08  5123.2  274.13  5179.5  277.00
  5208.6  279.29  5223.2  280.14  5229.5  280.11  5233.6  280.85  5236.8  280.85
#Mann=3,-1,0
  4875.0    0.05       0  4997.3    0.03       0  5003.3    0.05       0
Bank Sta=4997.3,5003.3
Exp/Cntr=0.3,0.1

Type RM Length L Ch R = 1,4348,892,892,892
BEGIN DESCRIPTION:
UNT04886 IN WICK 8.0
END DESCRIPTION:
XS GIS Cut Line= 3
      3620392.07     10266591.64      3620242.11     10266591.64
      3619992.12     10266791.63
#Sta/Elev= 30
  4820.9  277.43  4823.4  277.43  4870.9  270.92  4890.9  269.41  4950.9  267.27
  4960.9  266.17  4974.1  265.90  4984.5  265.08  4992.5  263.26  4995.9  263.07
  4998.6  262.57  5001.9  263.07  5006.9  263.85  5013.3  263.90  5021.3  265.63
  5034.9  265.38  5042.1  265.82  5048.5  265.61  5056.5  266.66  5062.9  266.59
  5070.9  268.29  5077.3  268.60  5085.3  269.89  5126.9  271.79  5170.2  274.72
  5191.0  275.77  5199.0  276.54  5219.8  277.37  5263.0  280.52  5291.0  281.96
#Mann=3,-1,0
  4820.9    0.05       0  4995.9    0.03       0  5001.9    0.05       0
Bank Sta=4995.9,5001.9
Exp/Cntr=0.3,0.1

Type RM Length L Ch R = 1,3456,846,846,846
BEGIN DESCRIPTION:
UNT04886 IN WICK 6.0
END DESCRIPTION:
XS GIS Cut Line= 2
      3619990.50     10265829.51      3619769.15     10266471.84
#Sta/Elev= 30
  4827.3  278.34  4839.3  277.99  4924.6  274.55  4945.9  272.89  4955.8  270.03
  4961.1  270.71  4967.1  266.24  4977.6  262.17  4987.0  260.77  4995.8  257.19
  4998.5  256.69  5001.8  257.19  5018.3  261.34  5023.6  261.57  5041.1  261.44
  5072.8  262.65  5080.7  262.09  5094.0  263.05  5143.1  262.04  5179.6  265.10
  5236.8  264.78  5268.0  266.19  5305.5  269.25  5330.4  269.97  5361.6  272.90
  5387.5  274.34  5392.8  273.04  5418.7  274.14  5455.2  273.70  5506.7  275.05
#Mann=4,-1,0
  4827.3    0.05       0  4839.3    0.16       0  4995.8    0.07       0
  5001.8    0.16       0
Bank Sta=4995.8,5001.8
Exp/Cntr=0.3,0.1

Type RM Length L Ch R = 1,2610,575,575,575
BEGIN DESCRIPTION:
UNT04886 IN WICK 5.0
END DESCRIPTION:
XS GIS Cut Line= 3
      3619799.51     10265712.33      3619304.73     10265903.29
      3619209.34     10266076.74
#Sta/Elev= 30
  4738.1  274.17  4805.3  269.68  4835.3  268.49  4859.9  266.23  4939.0  262.09
  4969.0  258.69  4974.4  259.64  4989.6  255.43  4992.3  254.93  4995.6  255.43
  4999.0  257.04  5004.3  256.09  5014.0  258.08  5023.6  258.60  5099.8  258.11
  5198.0  261.26  5217.3  262.88  5239.1  265.87  5247.2  265.45  5252.6  266.51
  5267.2  265.75  5300.1  268.58  5305.8  268.01  5321.9  271.22  5327.6  270.03
  5343.6  272.64  5349.3  272.11  5365.4  274.45  5387.2  275.94  5466.4  279.30
#Mann=3,-1,0
  4738.1    0.16       0  4989.6    0.07       0  4995.6    0.16       0
Bank Sta=4989.6,4995.6
Exp/Cntr=0.3,0.1

Type RM Length L Ch R = 1,2035,478,478,478
BEGIN DESCRIPTION:
UNT04886 IN WICK 4.0
END DESCRIPTION:
XS GIS Cut Line= 3
      3619692.12     10265341.64      3619492.11     10265441.64
      3619192.08     10265641.66
#Sta/Elev= 30
  4804.7  274.39  4827.1  273.41  4835.5  272.21  4867.2  269.61  4889.8  267.45
  4930.5  263.59  4938.9  262.05  4947.3  258.75  4956.9  257.81  4983.6  256.99
  4997.6  254.73  5003.0  254.68  5005.7  254.18  5009.0  254.68  5014.3  256.35
  5025.5  257.03  5050.9  257.59  5056.9  257.17  5071.9  256.98  5123.0  257.44
  5150.0  259.06  5208.6  260.83  5231.1  262.09  5273.2  263.09  5345.3  266.11
  5360.3  267.62  5366.3  267.57  5375.4  268.27  5381.4  268.19  5388.9  268.72
#Mann=6,-1,0
  4804.7    0.05       0  4867.2    0.16       0  4889.8    0.05       0
  4956.9    0.16       0  5003.0    0.07       0  5009.0    0.16       0
Bank Sta=5003,5009
Exp/Cntr=0.3,0.1

Type RM Length L Ch R = 1,1557,262,262,262
BEGIN DESCRIPTION:
UNT04886 IN WICK 3.0
END DESCRIPTION:
XS GIS Cut Line= 3
      3619492.15     10264991.62      3619242.11     10265141.64
      3618942.11     10265391.64
#Sta/Elev= 30
  4725.2  268.76  4748.6  268.02  4760.2  265.06  4771.3  261.08  4783.6  254.47
  4791.3  253.12  4806.9  252.77  4828.3  253.56  4855.5  253.51  4886.6  252.71
  4892.4  253.40  4958.5  254.17  4981.8  253.82  4990.5  251.35  4993.2  250.85
  4996.5  251.35  5003.2  251.43  5013.9  253.88  5024.0  253.81  5038.3  252.89
  5102.1  255.79  5116.4  257.80  5137.2  258.32  5150.2  259.28  5165.8  260.95
  5186.7  262.13  5237.4  263.86  5329.2  269.15  5357.2  270.18  5407.3  273.01
#Mann=5,-1,0
  4725.2    0.16       0  4771.3    0.12       0  4990.5    0.07       0
  4996.5    0.12       0  5150.2    0.05       0
Bank Sta=4990.5,4996.5
Exp/Cntr=0.3,0.1

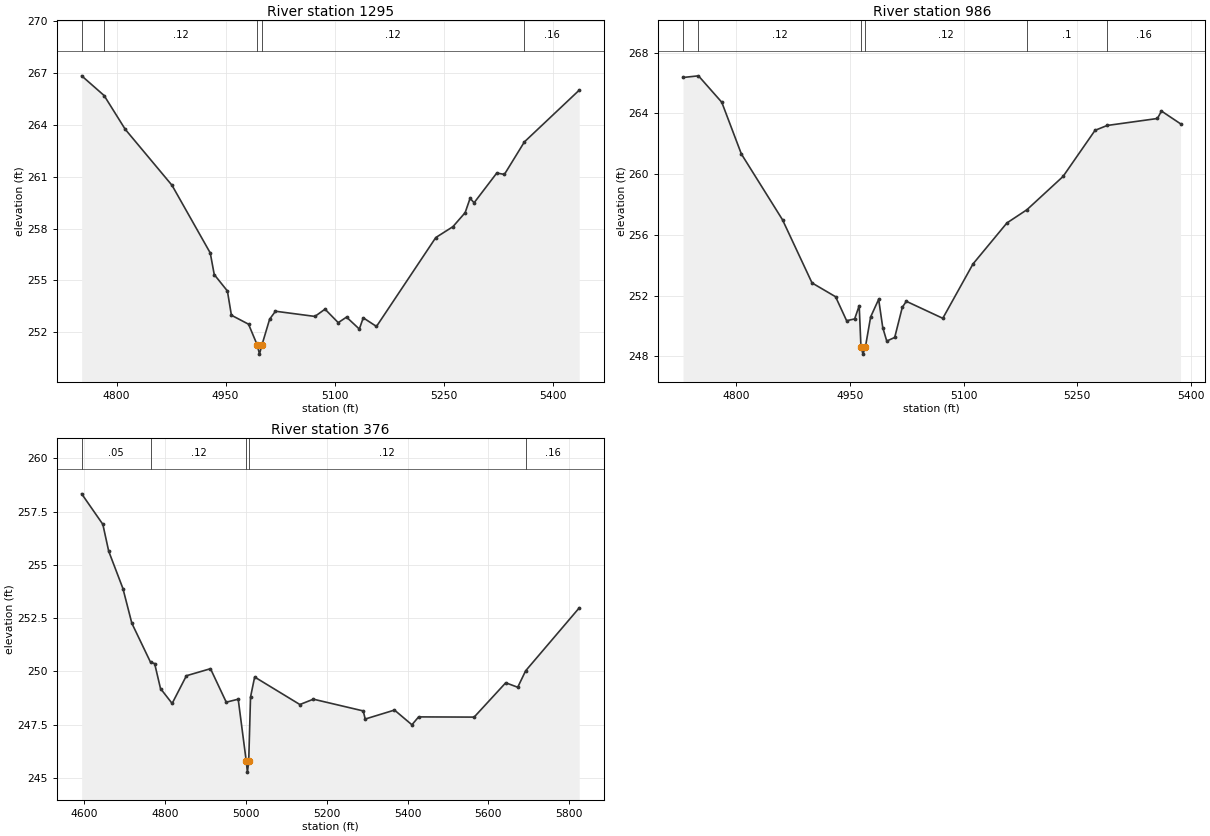
Type RM Length L Ch R = 1,1295,309,309,309
BEGIN DESCRIPTION:
UNT04886 IN WICK 2.0
END DESCRIPTION:
XS GIS Cut Line= 2
      3619387.20     10264865.97      3618757.82     10265135.08
#Sta/Elev= 30
  4752.0  266.83  4782.9  265.69  4811.9  263.74  4876.3  260.50  4928.9  256.59
  4934.4  255.34  4952.5  254.39  4958.0  252.99  4981.6  252.47  4993.8  251.24
  4996.6  250.74  4999.8  251.24  5010.6  252.76  5018.6  253.22  5072.9  252.92
  5086.8  253.34  5105.0  252.56  5116.4  252.88  5134.0  252.19  5139.4  252.84
  5157.6  252.34  5239.2  257.48  5262.8  258.11  5279.6  258.92  5286.4  259.75
  5291.9  259.49  5323.1  261.21  5333.6  261.13  5361.1  263.01  5436.5  266.00
#Mann=5,-1,0
  4752.0    0.05       0  4782.9    0.12       0  4993.8    0.07       0
  4999.8    0.12       0  5361.1    0.16       0
Bank Sta=4993.8,4999.8
Exp/Cntr=0.3,0.1

Type RM Length L Ch R = 1,986,610,610,610
BEGIN DESCRIPTION:
Mapping XS a447ef3f
END DESCRIPTION:
XS GIS Cut Line= 2
      3619196.22     10264720.08      3618575.48     10264935.65
#Sta/Elev= 30
  4729.4  266.36  4749.8  266.47  4780.6  264.73  4806.5  261.32  4860.8  256.99
  4899.8  252.83  4930.9  251.92  4945.5  250.34  4956.1  250.46  4962.1  251.33
  4964.4  248.64  4967.1  248.14  4970.4  248.64  4977.2  250.59  4987.8  251.75
  4993.2  249.89  4998.5  249.00  5009.0  249.24  5019.0  251.22  5024.3  251.62
  5072.5  250.50  5112.4  254.08  5157.2  256.78  5183.6  257.65  5231.3  259.84
  5273.6  262.88  5289.6  263.20  5356.0  263.66  5361.3  264.15  5386.5  263.31
#Mann=6,-1,0
  4729.4    0.05       0  4749.8    0.12       0  4964.4    0.07       0
  4970.4    0.12       0  5183.6     0.1       0  5289.6    0.16       0
Bank Sta=4964.4,4970.4
Exp/Cntr=0.3,0.1

Type RM Length L Ch R = 1,376,0,0,0
BEGIN DESCRIPTION:
UNT04886 IN WICK 1.0
END DESCRIPTION:
XS GIS Cut Line= 4
      3619179.51     10264498.16      3618929.53     10264300.26
      3618558.01     10264369.71      3618360.09     10264866.22
#Sta/Elev= 30
  4593.4  258.33  4645.8  256.90  4660.3  255.64  4695.5  253.89  4717.6  252.26
  4763.9  250.43  4774.0  250.37  4788.5  249.20  4817.3  248.50  4852.6  249.80
  4912.2  250.13  4951.2  248.56  4980.8  248.70  5000.8  245.78  5003.6  245.28
  5006.8  245.78  5011.3  248.80  5021.5  249.74  5133.4  248.45  5166.9  248.70
  5290.2  248.15  5295.1  247.77  5367.6  248.19  5410.7  247.50  5427.3  247.87
  5564.7  247.86  5642.9  249.47  5672.6  249.26  5692.1  250.03  5824.7  252.98
#Mann=5,-1,0
  4593.4    0.05       0  4763.9    0.12       0  5000.8    0.07       0
  5006.8    0.12       0  5692.1    0.16       0
Bank Sta=5000.8,5006.8
Exp/Cntr=0.3,0.1

Chan Stop Cuts=-1