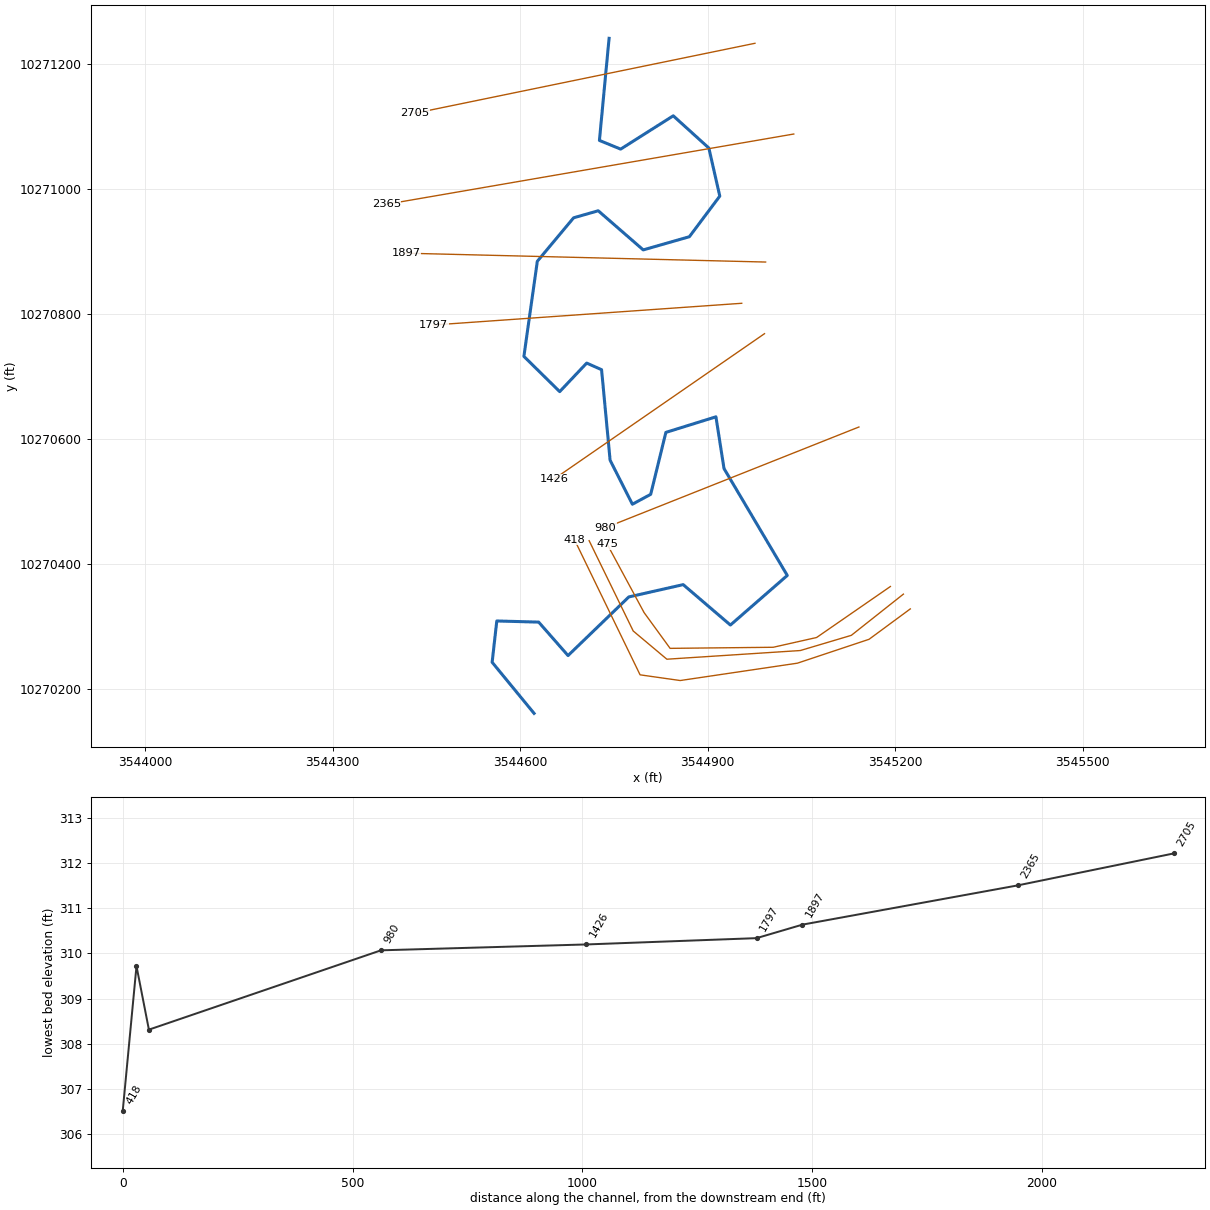
--- UNT0490 IN WICK.prj (project) ---

Proj Title=UNT0490 IN WICK Base Level Engineering
Current Plan=p01
Default Exp/Contr=0.3,0.1
English Units
Geom File=g01
Flow File=f01
Plan File=p01
BEGIN DESCRIPTION:
UNT0490 IN WICK
END DESCRIPTION:

--- UNT0490 IN WICK.p01 (plan) ---

Plan Title=Multiple Run
Short Identifier=Multiple
Geom File=g01
Flow File=f01
Subcritical Flow
K Sum by GR= 0
Std Step Tol= 0.01
Critical Tol= 0.01
Num of Std Step Trials= 20
Max Error Tol= 0.3
Flow Tol Ratio= 0.001
Split Flow NTrial= 30
Split Flow Tol= 0.02
Split Flow Ratio= 0.02
Log Output Level= 0
Friction Slope Method= 1
Unsteady Friction Slope Method= 2
Unsteady Bridges Friction Slope Method= 1
Parabolic Critical Depth
Global Vel Dist=  1 , 1 , 1
Global Log Level= 0
CheckData=True
Encroach Param= -1, 0, 0, 0
BEGIN DESCRIPTION:
Multiple Run
END DESCRIPTION:

--- UNT0490 IN WICK.f01 (steady flow) ---

Flow Title=Multiple
Number of Profiles=7
Profile Names=10-year,25-year,50-year,1pct_min,100-year,1pct_plu,500-year
River Rch & RM= UNT0490 IN WICK,Reach-1,2705
     522     695     833     732     990    1339    1401
Boundary for River Rch & Prof#=UNT0490 IN WICK,Reach-1,1
Up Type=0
Dn Type=3
Dn Slope=0.005
Boundary for River Rch & Prof#=UNT0490 IN WICK,Reach-1,2
Up Type=0
Dn Type=3
Dn Slope=0.005
Boundary for River Rch & Prof#=UNT0490 IN WICK,Reach-1,3
Up Type=0
Dn Type=3
Dn Slope=0.005
Boundary for River Rch & Prof#=UNT0490 IN WICK,Reach-1,4
Up Type=0
Dn Type=3
Dn Slope=0.005
Boundary for River Rch & Prof#=UNT0490 IN WICK,Reach-1,5
Up Type=0
Dn Type=3
Dn Slope=0.005
Boundary for River Rch & Prof#=UNT0490 IN WICK,Reach-1,6
Up Type=0
Dn Type=3
Dn Slope=0.005
Boundary for River Rch & Prof#=UNT0490 IN WICK,Reach-1,7
Up Type=0
Dn Type=3
Dn Slope=0.005

--- UNT0490 IN WICK.g01 (geometry) ---

Geom Title=Existing Conditions

River Reach=UNT0490 IN WICK,Reach-1
Reach XY= 30
      3544742.11     10271241.64      3544726.65     10271078.29
      3544760.64     10271064.40      3544844.77     10271117.69
      3544901.75     10271066.11      3544919.23     10270989.19
      3544870.54     10270924.23      3544796.78     10270903.16
      3544724.75     10270965.76      3544685.40     10270954.52
      3544627.29     10270884.94      3544605.83     10270732.79
      3544663.11     10270676.41      3544706.29     10270722.07
      3544730.10     10270711.50      3544743.75     10270566.70
      3544779.39     10270496.24      3544808.70     10270512.10
      3544832.96     10270611.17      3544913.08     10270636.09
      3544925.99     10270553.35      3545027.23     10270382.30
      3544936.22     10270302.96      3544860.68     10270367.61
      3544773.68     10270347.94      3544676.44     10270254.14
      3544629.47     10270307.65      3544562.46     10270309.47
      3544555.02     10270243.38      3544622.11     10270161.64

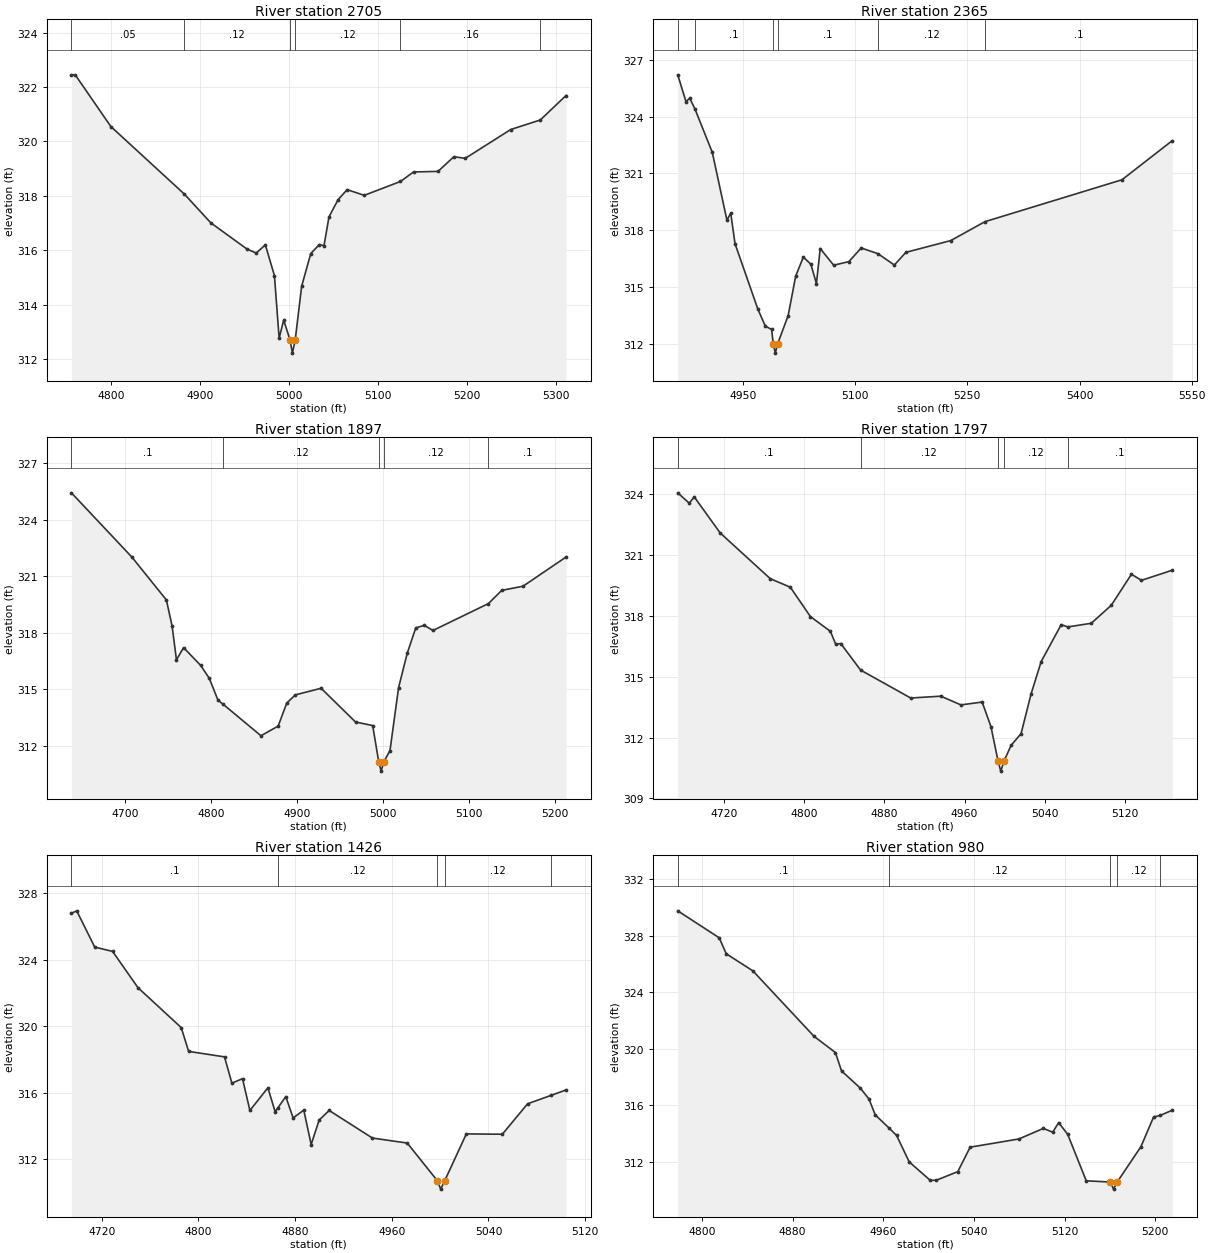
Type RM Length L Ch R = 1,2705,340,340,340
BEGIN DESCRIPTION:
UNT0490 IN WICK 10.0
END DESCRIPTION:
XS GIS Cut Line= 2
      3544975.54     10271233.72      3544431.24     10271121.74
#Sta/Elev= 30
  4755.5  322.45  4759.8  322.45  4799.8  320.55  4882.3  318.07  4912.1  317.01
  4953.0  316.04  4963.2  315.90  4973.4  316.20  4983.6  315.07  4988.9  312.77
  4994.0  313.43  5001.0  312.72  5003.8  312.22  5007.0  312.72  5014.2  314.68
  5024.4  315.88  5034.1  316.21  5039.3  316.17  5044.9  317.23  5055.1  317.86
  5065.3  318.23  5084.5  318.02  5125.2  318.53  5139.9  318.88  5167.4  318.90
  5185.2  319.44  5198.0  319.38  5249.1  320.44  5282.3  320.79  5311.2  321.69
#Mann=6,-1,0
  4755.5    0.05       0  4882.3    0.12       0  5001.0    0.07       0
  5007.0    0.12       0  5125.2    0.16       0  5282.3     0.1       0
Bank Sta=5001,5007
Exp/Cntr=0.3,0.1

Type RM Length L Ch R = 1,2365,468,468,468
BEGIN DESCRIPTION:
Mapping XS da396184
END DESCRIPTION:
XS GIS Cut Line= 2
      3545037.63     10271088.57      3544385.66     10270976.09
#Sta/Elev= 30
  4862.6  326.20  4873.6  324.79  4878.7  324.96  4885.5  324.41  4908.8  322.11
  4928.4  318.53  4933.5  318.90  4939.2  317.29  4969.7  313.84  4979.8  312.93
  4988.2  312.76  4990.3  312.01  4993.1  311.51  4996.3  312.01  5010.3  313.49
  5020.4  315.58  5030.6  316.58  5040.7  316.20  5048.1  315.18  5053.2  317.03
  5071.2  316.15  5091.5  316.34  5108.0  317.06  5130.4  316.76  5152.3  316.16
  5167.8  316.83  5227.7  317.45  5273.6  318.45  5456.8  320.66  5524.2  322.73
#Mann=6,-1,0
  4862.6    0.05       0  4885.5     0.1       0  4990.3    0.07       0
  4996.3     0.1       0  5130.4    0.12       0  5273.6     0.1       0
Bank Sta=4990.3,4996.3
Exp/Cntr=0.3,0.1

Type RM Length L Ch R = 1,1897,100,100,100
BEGIN DESCRIPTION:
Mapping XS ef6a99a6
END DESCRIPTION:
XS GIS Cut Line= 2
      3544992.54     10270883.72      3544417.32     10270897.88
#Sta/Elev= 30
  4637.7  325.42  4708.2  322.00  4748.2  319.73  4754.9  318.33  4759.9  316.55
  4768.2  317.20  4788.2  316.25  4798.2  315.56  4808.2  314.41  4814.5  314.18
  4858.2  312.52  4878.2  313.03  4888.2  314.25  4898.2  314.69  4928.2  315.04
  4968.2  313.25  4988.2  313.06  4995.2  311.14  4998.0  310.64  5001.2  311.14
  5008.3  311.73  5018.3  315.07  5028.3  316.89  5038.3  318.25  5048.3  318.38
  5058.3  318.11  5122.9  319.54  5138.3  320.24  5163.1  320.46  5213.1  322.01
#Mann=5,-1,0
  4637.7     0.1       0  4814.5    0.12       0  4995.2    0.07       0
  5001.2    0.12       0  5122.9     0.1       0
Bank Sta=4995.2,5001.2
Exp/Cntr=0.3,0.1

Type RM Length L Ch R = 1,1797,371,371,371
BEGIN DESCRIPTION:
Mapping XS 77d45231
END DESCRIPTION:
XS GIS Cut Line= 2
      3544954.37     10270817.75      3544461.29     10270783.02
#Sta/Elev= 30
  4673.4  324.08  4684.9  323.57  4689.9  323.88  4715.8  322.10  4765.9  319.84
  4785.9  319.42  4806.0  317.97  4826.0  317.24  4831.3  316.60  4836.3  316.64
  4856.1  315.33  4906.2  313.95  4936.3  314.04  4956.4  313.61  4977.6  313.75
  4986.4  312.54  4993.5  310.84  4996.2  310.34  4999.5  310.84  5006.5  311.61
  5016.5  312.19  5026.5  314.15  5036.6  315.75  5056.6  317.57  5063.3  317.46
  5086.7  317.64  5106.7  318.53  5126.8  320.06  5136.8  319.76  5167.7  320.26
#Mann=5,-1,0
  4673.4     0.1       0  4856.1    0.12       0  4993.5    0.07       0
  4999.5    0.12       0  5063.3     0.1       0
Bank Sta=4993.5,4999.5
Exp/Cntr=0.3,0.1

Type RM Length L Ch R = 1,1426,446,446,446
BEGIN DESCRIPTION:
Mapping XS 05be0c80
END DESCRIPTION:
XS GIS Cut Line= 2
      3544990.76     10270769.11      3544653.98     10270536.49
#Sta/Elev= 30
  4694.9  326.78  4699.3  326.93  4714.2  324.75  4729.0  324.49  4750.0  322.31
  4785.8  319.91  4791.9  318.48  4821.6  318.15  4827.7  316.57  4836.5  316.84
  4842.6  314.93  4857.5  316.29  4863.5  314.85  4865.6  315.07  4872.3  315.76
  4878.4  314.48  4887.2  314.95  4893.3  312.88  4899.9  314.35  4908.2  314.93
  4944.0  313.27  4972.8  312.97  4997.8  310.70  5000.5  310.20  5003.8  310.70
  5021.7  313.52  5051.5  313.50  5072.4  315.33  5091.6  315.83  5104.2  316.16
#Mann=5,-1,0
  4694.9     0.1       0  4865.6    0.12       0  4997.8    0.07       0
  5003.8    0.12       0  5091.6    0.16       0
Bank Sta=4997.8,5003.8
Exp/Cntr=0.3,0.1

Type RM Length L Ch R = 1,980,505,505,505
BEGIN DESCRIPTION:
Mapping XS 68e20047
END DESCRIPTION:
XS GIS Cut Line= 2
      3545141.87     10270619.84      3544736.33     10270458.66
#Sta/Elev= 30
  4778.7  329.77  4815.3  327.86  4821.5  326.73  4845.0  325.52  4898.9  320.89
  4917.8  319.74  4923.2  318.44  4939.9  317.21  4947.5  316.44  4952.9  315.33
  4965.2  314.39  4971.8  313.87  4982.9  312.00  5001.5  310.69  5006.9  310.70
  5025.8  311.31  5036.7  313.04  5079.7  313.62  5101.3  314.37  5109.5  314.10
  5114.8  314.78  5122.8  313.94  5139.1  310.66  5160.4  310.57  5163.2  310.07
  5166.4  310.57  5187.4  313.08  5198.5  315.17  5204.4  315.29  5215.1  315.66
#Mann=5,-1,0
  4778.7     0.1       0  4965.2    0.12       0  5160.4    0.07       0
  5166.4    0.12       0  5204.4    0.16       0
Bank Sta=5160.4,5166.4
Exp/Cntr=0.3,0.1

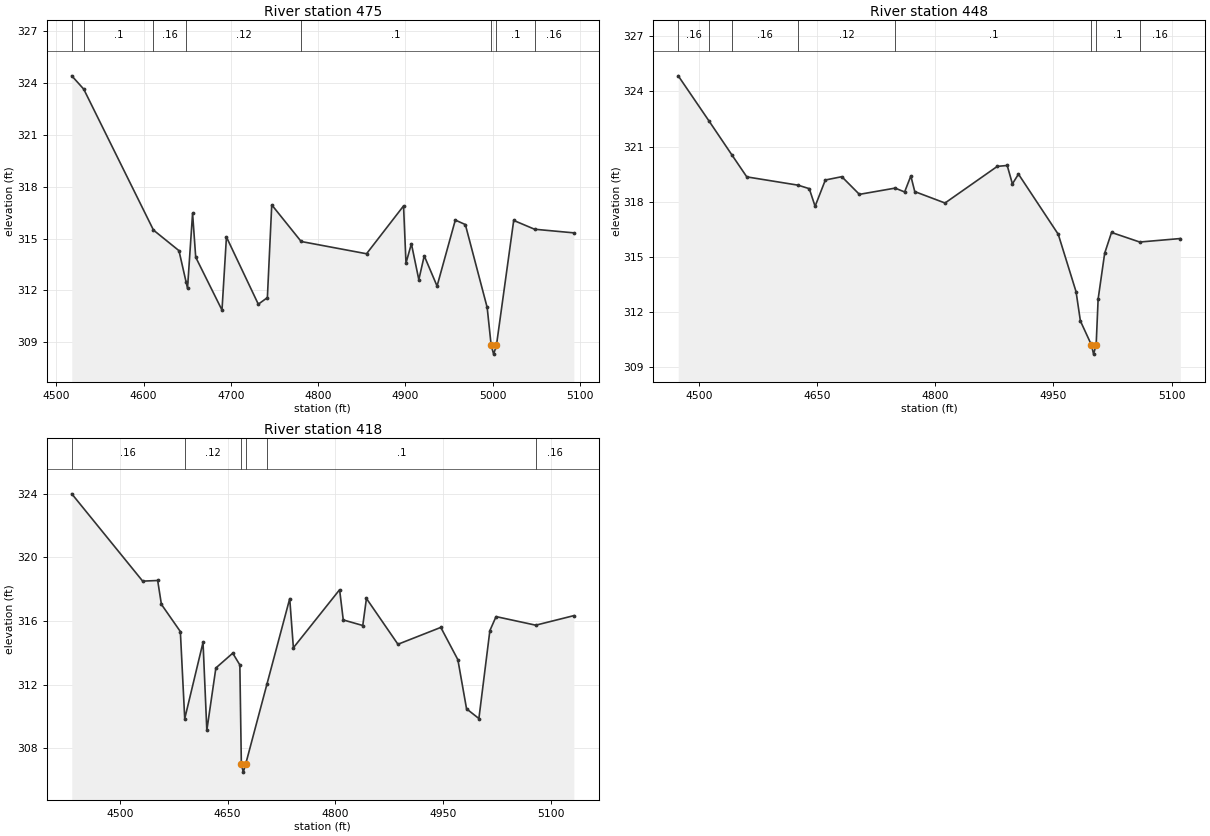
Type RM Length L Ch R = 1,475,27,27,27
BEGIN DESCRIPTION:
Mapping XS 469fc6d3
END DESCRIPTION:
XS GIS Cut Line= 6
      3545192.19     10270364.62      3545074.13     10270283.02
      3545004.69     10270267.40      3544839.76     10270265.66
      3544798.09     10270322.95      3544739.07     10270432.32
#Sta/Elev= 30
  4517.7  324.42  4531.4  323.65  4611.3  315.49  4640.5  314.30  4648.6  312.50
  4650.3  312.12  4656.1  316.46  4659.7  313.92  4689.8  310.86  4694.9  315.09
  4731.4  311.20  4741.8  311.58  4746.8  316.95  4780.5  314.83  4855.4  314.12
  4897.8  316.89  4900.6  313.58  4906.8  314.70  4915.3  312.62  4921.5  314.00
  4936.2  312.25  4957.1  316.07  4968.6  315.81  4993.6  311.01  4998.2  308.81
  5001.0  308.31  5004.2  308.81  5024.0  316.05  5047.9  315.54  5092.9  315.33
#Mann=8,-1,0
  4517.7    0.16       0  4531.4     0.1       0  4611.3    0.16       0
  4648.6    0.12       0  4780.5     0.1       0  4998.2    0.07       0
  5004.2     0.1       0  5047.9    0.16       0
Bank Sta=4998.2,5004.2
Exp/Cntr=0.3,0.1

Type RM Length L Ch R = 1,448,30,30,30
BEGIN DESCRIPTION:
Mapping XS 93418337
END DESCRIPTION:
XS GIS Cut Line= 6
      3545213.00     10270352.45      3545129.69     10270286.49
      3545048.09     10270262.19      3544834.55     10270248.30
      3544780.73     10270293.44      3544710.20     10270437.93
#Sta/Elev= 30
  4473.8  324.84  4512.8  322.39  4541.8  320.55  4560.8  319.35  4625.8  318.90
  4640.1  318.71  4647.5  317.75  4660.5  319.18  4681.4  319.36  4703.7  318.40
  4749.1  318.74  4761.1  318.53  4769.0  319.40  4774.0  318.55  4812.4  317.93
  4878.7  319.92  4891.3  319.97  4897.9  318.97  4905.6  319.50  4956.1  316.23
  4978.7  313.11  4984.2  311.52  4998.2  310.22  5000.9  309.72  5004.2  310.22
  5006.7  312.71  5015.0  315.20  5023.7  316.33  5059.5  315.81  5111.0  316.00
#Mann=8,-1,0
  4473.8    0.16       0  4512.8     0.1       0  4541.8    0.16       0
  4625.8    0.12       0  4749.1     0.1       0  4998.2    0.07       0
  5004.2     0.1       0  5059.5    0.16       0
Bank Sta=4998.2,5004.2
Exp/Cntr=0.3,0.1

Type RM Length L Ch R = 1,418,0,0,0
BEGIN DESCRIPTION:
UNT0490 IN WICK 1.0
END DESCRIPTION:
XS GIS Cut Line= 6
      3545224.03     10270328.79      3545158.03     10270280.16
      3545043.44     10270241.96      3544855.94     10270214.19
      3544791.71     10270223.30      3544686.69     10270439.67
#Sta/Elev= 30
  4432.8  324.00  4531.6  318.51  4552.5  318.55  4557.7  317.05  4584.1  315.34
  4590.2  309.86  4615.7  314.66  4621.0  309.13  4633.6  313.05  4657.1  313.98
  4667.0  313.24  4669.1  307.00  4671.8  306.50  4675.1  307.00  4704.8  312.04
  4736.5  317.41  4741.6  314.32  4806.0  317.97  4811.1  316.07  4838.3  315.72
  4843.4  317.42  4887.3  314.54  4947.0  315.60  4970.8  313.57  4982.9  310.48
  5000.1  309.87  5015.4  315.40  5024.0  316.28  5079.3  315.74  5132.4  316.34
#Mann=6,-1,0
  4432.8    0.16       0  4590.2    0.12       0  4669.1    0.07       0
  4675.1    0.12       0  4704.8     0.1       0  5079.3    0.16       0
Bank Sta=4669.1,4675.1
Exp/Cntr=0.3,0.1

Chan Stop Cuts=-1