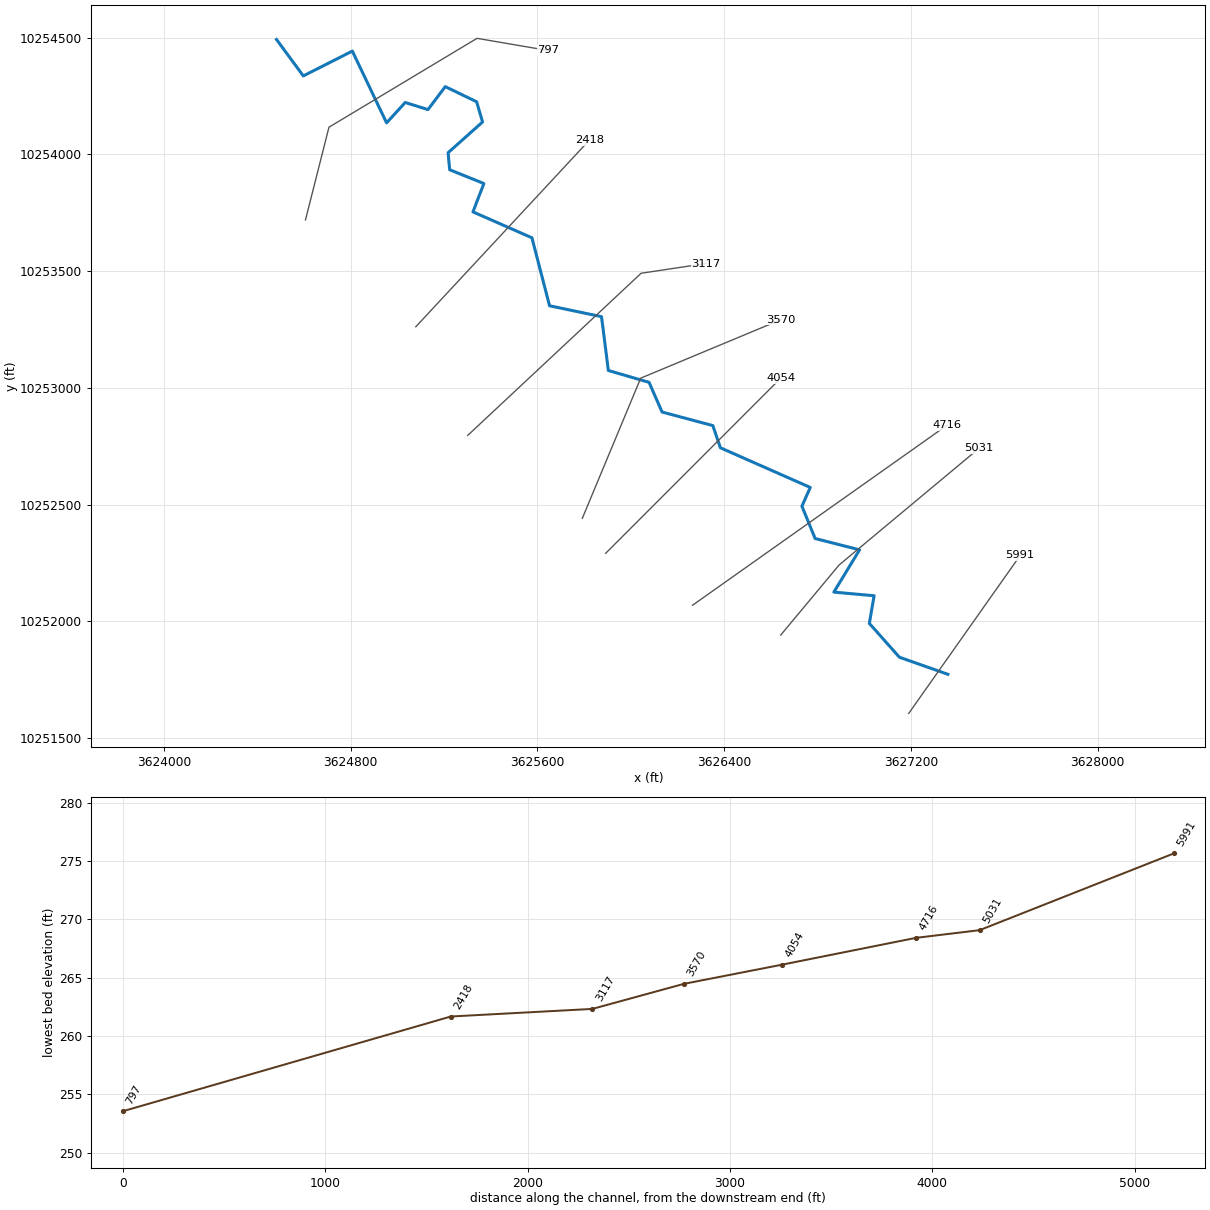
--- UNT05021 IN WICK.prj (project) ---

Proj Title=UNT05021 IN WICK Base Level Engineering
Current Plan=p01
Default Exp/Contr=0.3,0.1
English Units
Geom File=g01
Flow File=f01
Plan File=p01
Y Axis Title=Elevation
X Axis Title(PF)=Main Channel Distance
X Axis Title(XS)=Station
BEGIN DESCRIPTION:
UNT05021 IN WICK
END DESCRIPTION:
DSS Export Rating Curves= 0
DSS Export Rating Curve Sorted= 0
DSS Export Volume Flow Curves= 0
DXF OffsetX= 0
DXF OffsetY= 0
DXF ScaleX= 1
DXF ScaleY= 10

--- UNT05021 IN WICK.p01 (plan) ---

Plan Title=Multiple Run
Short Identifier=Multiple
Geom File=g01
Flow File=f01
Subcritical Flow
K Sum by GR= 0
Std Step Tol= 0.01
Critical Tol= 0.01
Num of Std Step Trials= 20
Max Error Tol= 0.3
Flow Tol Ratio= 0.001
Split Flow NTrial= 30
Split Flow Tol= 0.02
Split Flow Ratio= 0.02
Log Output Level= 0
Friction Slope Method= 1
Unsteady Friction Slope Method= 2
Unsteady Bridges Friction Slope Method= 1
Parabolic Critical Depth
Global Vel Dist=  1 , 1 , 1
Global Log Level= 0
CheckData=True
Encroach Param= -1, 0, 0, 0
BEGIN DESCRIPTION:
Multiple Run
END DESCRIPTION:

--- UNT05021 IN WICK.f01 (steady flow) ---

Flow Title=Multiple
Number of Profiles=7
Profile Names=10-year,25-year,50-year,1pct_min,100-year,1pct_plu,500-year
River Rch & RM= UNT05021 IN WICK,Reach-1,5991
     422     557     664     582     787    1065    1106
Boundary for River Rch & Prof#=UNT05021 IN WICK,Reach-1,1
Up Type=0
Dn Type=3
Dn Slope=0.005
Boundary for River Rch & Prof#=UNT05021 IN WICK,Reach-1,2
Up Type=0
Dn Type=3
Dn Slope=0.005
Boundary for River Rch & Prof#=UNT05021 IN WICK,Reach-1,3
Up Type=0
Dn Type=3
Dn Slope=0.005
Boundary for River Rch & Prof#=UNT05021 IN WICK,Reach-1,4
Up Type=0
Dn Type=3
Dn Slope=0.005
Boundary for River Rch & Prof#=UNT05021 IN WICK,Reach-1,5
Up Type=0
Dn Type=3
Dn Slope=0.005
Boundary for River Rch & Prof#=UNT05021 IN WICK,Reach-1,6
Up Type=0
Dn Type=3
Dn Slope=0.005
Boundary for River Rch & Prof#=UNT05021 IN WICK,Reach-1,7
Up Type=0
Dn Type=3
Dn Slope=0.005

--- UNT05021 IN WICK.g01 (geometry) ---

Geom Title=Existing Conditions
Program Version=4.10

River Reach=UNT05021 IN WICK,Reach-1
Reach XY= 30
        3627358.     10251773.54      3627150.34     10251846.71
      3627021.63     10251991.49      3627041.92     10252109.89
      3626869.56     10252125.48      3626979.68     10252306.43
      3626789.25      10252355.1      3626732.78     10252493.44
      3626768.62     10252573.62      3626383.61     10252743.44
      3626351.13     10252838.45      3626133.61     10252896.66
      3626077.95     10253023.69      3625903.57     10253074.39
      3625874.27     10253304.86      3625651.62     10253351.52
      3625576.12     10253642.62      3625323.49     10253753.64
      3625370.31     10253874.94      3625223.88     10253933.98
      3625216.89     10254006.84      3625364.68     10254138.56
      3625339.16     10254225.01        3625205.     10254289.88
      3625130.79     10254191.58      3625033.35     10254221.96
      3624953.44     10254134.66      3624806.78     10254442.01
      3624596.71     10254335.67      3624482.11     10254491.64

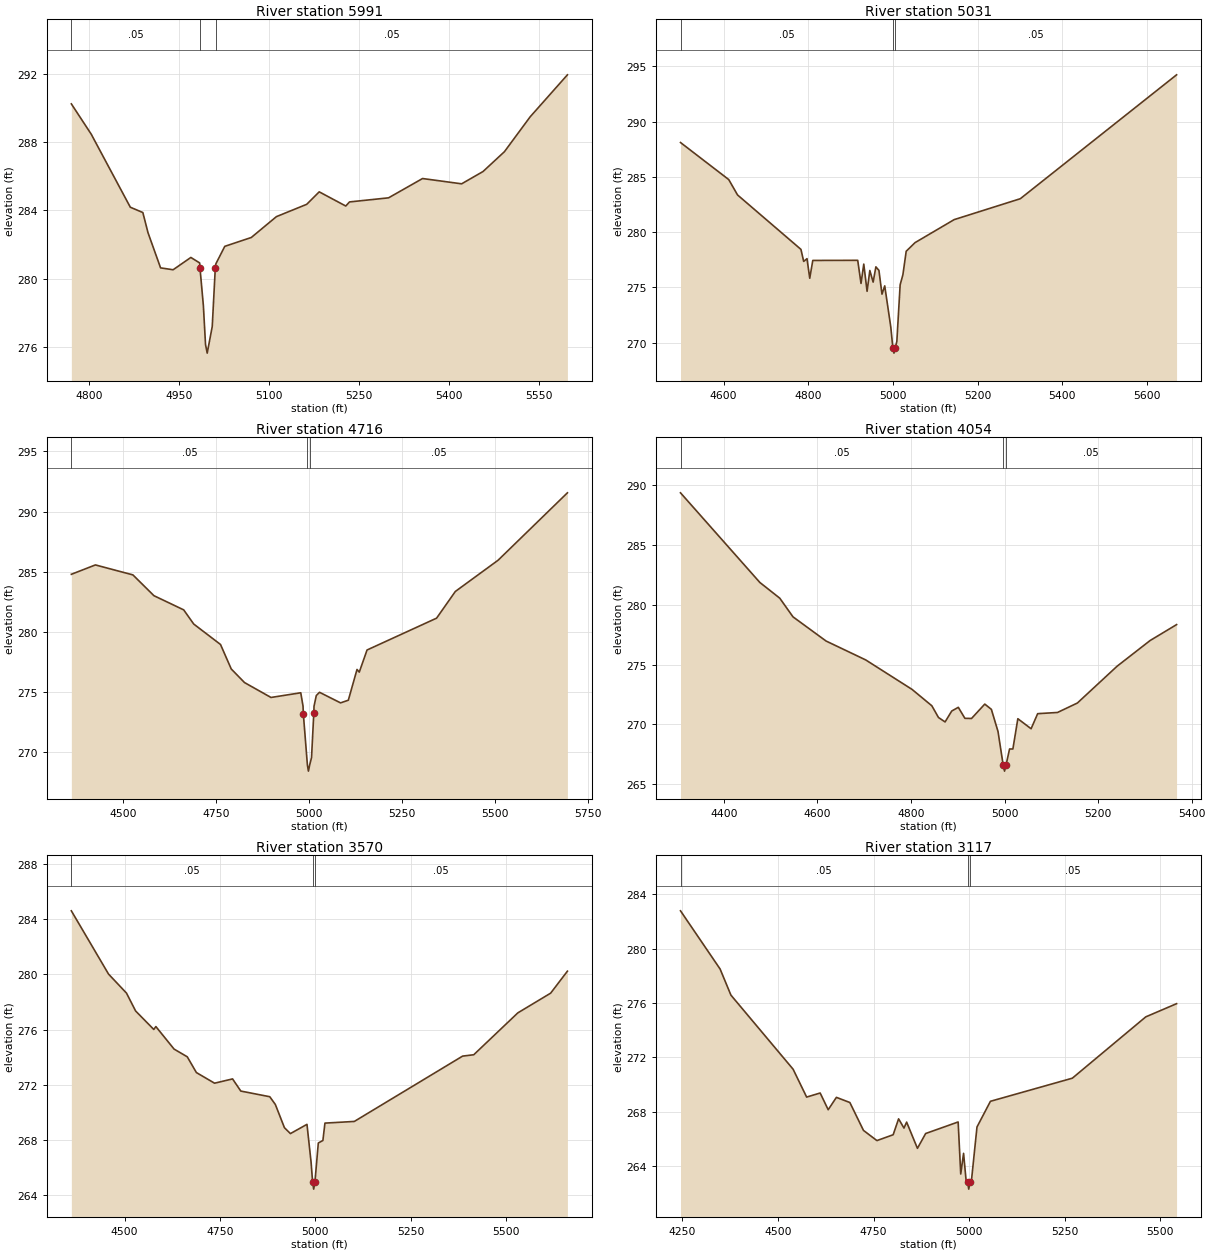
Type RM Length L Ch R = 1 ,5991    ,960,960,960
BEGIN DESCRIPTION:
UNT05021 IN WICK 8.0
END DESCRIPTION:
XS GIS Cut Line= 2
      3627190.42     10251606.23      3627667.69     10252282.47
#Sta/Elev= 30
  4770.3  290.23  4803.4  288.46  4868.7  284.18  4889.6  283.87  4898.2  282.69
  4919.2  280.63  4940.1  280.52  4969.7  281.24  4984.4  280.92 4984.88  280.65
  4990.6  278.42  4994.2  276.14    4997  275.64  5005.4   277.2 5010.46   280.6
  5011.5  280.87  5026.3  281.89  5070.6  282.41  5112.5  283.63    5163  284.35
  5183.9  285.08  5228.2  284.25  5234.4  284.49  5299.6  284.73  5356.3  285.86
  5421.5  285.55  5457.2  286.27  5492.9  287.43  5535.8  289.47    5598  291.93
#Mann= 3 ,-1 , 0
  4770.3     .05       0 4984.88     .03       0  5011.5     .05       0
Bank Sta=4984.88,5010.46
XS Rating Curve= 0 ,0
Exp/Cntr=0.3,0.1

Type RM Length L Ch R = 1 ,5031    ,315,315,315
BEGIN DESCRIPTION:
UNT05021 IN WICK 7.0
END DESCRIPTION:
XS GIS Cut Line= 3
      3626642.11     10251941.65      3626892.11     10252241.64
      3627492.09     10252741.63
#Sta/Elev= 30
  4498.3   288.1  4612.2  284.75    4633  283.36  4782.7  278.44  4789.2  277.35
    4797   277.6  4803.5  275.83  4810.7  277.44  4916.8  277.45  4924.6  275.36
  4931.1  277.11  4938.9  274.65  4945.4  276.53  4953.2  275.48  4959.7  276.86
  4966.9  276.54  4974.1  274.39  4980.6  275.14  4994.9  271.42  4999.7  269.56
  5002.4  269.06  5005.7  269.56  5009.2  270.12    5017  275.24  5023.5  276.15
  5031.3  278.27  5052.2  279.05  5144.6  281.13  5300.8  283.02  5669.8  294.22
#Mann= 3 , 0 , 0
  4498.3     .05       0  4999.7     .03       0  5005.7     .05       0
Bank Sta=4999.7,5005.7
XS Rating Curve= 0 ,0
Exp/Cntr=0.3,0.1

Type RM Length L Ch R = 1 ,4716    ,662,662,662
BEGIN DESCRIPTION:
UNT05021 IN WICK 6.0
END DESCRIPTION:
XS GIS Cut Line= 2
      3626264.24     10252069.23      3627354.48     10252840.04
#Sta/Elev= 30
  4359.7  284.78  4424.5  285.56  4525.4  284.73    4582     283  4662.1  281.82
  4689.1  280.64  4761.2  278.94  4790.1   276.9  4825.8  275.77  4897.1  274.53
  4977.2  274.92  4983.3  273.81 4984.08  273.19  4995.1   268.9  4997.8   268.4
  5001.1   268.9  5006.2  269.53 5012.28  273.22  5012.9   273.8    5019  274.69
  5027.7  274.96  5084.3  274.08  5105.2   274.3  5128.6  276.86  5134.7  276.64
  5155.6  278.48  5342.8  281.13  5393.2  283.35  5508.3  285.95  5694.9  291.56
#Mann= 3 ,-1 , 0
  4359.7     .05       0  4995.1     .03       0  5001.1     .05       0
Bank Sta=4984.08,5012.28
XS Rating Curve= 0 ,0
Exp/Cntr=0.3,0.1

Type RM Length L Ch R = 1 ,4054    ,484,484,484
BEGIN DESCRIPTION:
UNT05021 IN WICK 5.0
END DESCRIPTION:
XS GIS Cut Line= 3
      3625892.08     10252291.62      3626392.11     10252791.64
      3626642.11     10253041.64
#Sta/Elev= 30
  4307.1  289.35  4476.8  281.86  4519.3  280.55  4547.6  278.99  4618.3  276.97
  4703.1  275.39  4802.1  272.93  4844.5  271.56  4858.7  270.58  4872.8  270.21
    4887  271.12  4901.1  271.43  4915.2  270.51  4929.4   270.5  4957.7   271.7
  4971.8  271.26    4986  269.41  4997.1   266.6  4999.9   266.1  5003.1   266.6
  5010.7  267.95  5017.8  267.95  5028.4  270.48  5056.7  269.64  5070.8   270.9
  5113.2     271  5155.7  271.79  5240.5  274.86  5311.2  277.01  5367.8  278.34
#Mann= 3 ,-1 , 0
  4307.1     .05       0  4997.1     .03       0  5003.1     .05       0
Bank Sta=4997.1,5003.1
XS Rating Curve= 0 ,0
Exp/Cntr=0.3,0.1

Type RM Length L Ch R = 1 ,3570    ,453,453,453
BEGIN DESCRIPTION:
UNT05021 IN WICK 4.0
END DESCRIPTION:
XS GIS Cut Line= 3
      3625792.12     10252441.69      3626042.11     10253041.64
      3626642.15     10253291.66
#Sta/Elev= 30
  4360.5  284.61    4458  280.03  4505.1  278.65  4528.9  277.36  4576.6  276.02
    4582  276.23  4629.7   274.6  4664.3  274.04  4688.2   272.9  4735.8  272.13
    4783  272.44  4804.6  271.56  4880.5  271.15  4895.1  270.59  4918.9  268.91
  4934.6  268.48    4978  269.15  4988.8   266.4  4992.8  264.96  4995.6  264.46
  4998.8  264.96  5007.7   267.8  5019.7  267.98  5025.1  269.24    5102  269.36
  5385.8  274.09  5415.1  274.19  5530.5  277.22  5616.6  278.65  5660.5  280.24
#Mann= 3 ,-1 , 0
  4360.5     .05       0  4992.8     .03       0  4998.8     .05       0
Bank Sta=4992.8,4998.8
XS Rating Curve= 0 ,0
Exp/Cntr=0.3,0.1

Type RM Length L Ch R = 1 ,3117    ,699,699,699
BEGIN DESCRIPTION:
UNT05021 IN WICK 3.0
END DESCRIPTION:
XS GIS Cut Line= 3
      3625300.97     10252796.37      3626044.03     10253490.81
      3626321.77     10253532.48
#Sta/Elev= 30
  4244.9  282.78  4348.5   278.5  4376.8  276.58  4539.5  271.13  4574.9  269.08
  4610.3  269.38  4631.3  268.15  4652.8  269.06    4688  268.68  4723.6  266.63
  4758.8  265.88  4801.3  266.31  4815.5  267.48  4829.6   266.8  4836.5  267.24
  4864.8  265.31  4886.3   266.4  4971.3  267.25  4978.1  263.42  4985.5  264.94
  4992.3  262.89  4996.3  262.81    4999  262.31  5002.3  262.81  5006.5  263.04
  5020.6  266.88  5055.8  268.77  5270.1  270.47  5462.2  274.98  5542.8  275.95
#Mann= 3 ,-1 , 0
  4244.9     .05       0  4996.3     .03       0  5002.3     .05       0
Bank Sta=4996.3,5002.3
XS Rating Curve= 0 ,0
Exp/Cntr=0.3,0.1

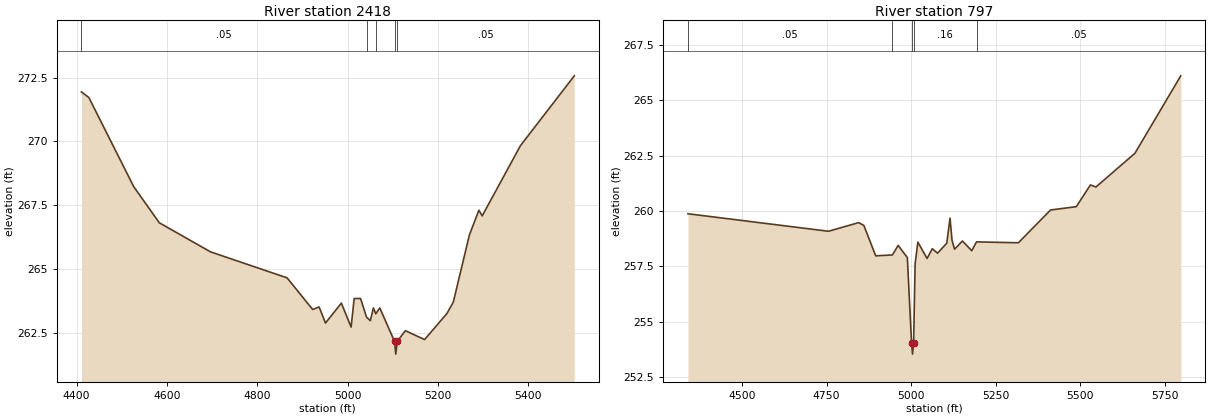
Type RM Length L Ch R = 1 ,2418    ,1621,1621,1621
BEGIN DESCRIPTION:
UNT05021 IN WICK 2.0
END DESCRIPTION:
XS GIS Cut Line= 2
      3625078.73     10253261.63      3625821.83     10254060.29
#Sta/Elev= 30
  4410.8  271.94  4427.2  271.72  4526.4  268.23  4583.1  266.81  4696.4  265.67
    4866  264.65  4922.6  263.41  4936.8  263.51    4951  262.88  4986.1  263.66
  5007.7  262.72  5014.5  263.84  5028.7  263.84  5041.8  263.11  5050.2  262.97
    5057  263.47  5062.2  263.24  5071.2  263.47  5103.8  262.16  5106.6  261.66
  5109.8  262.16  5127.8  262.58  5170.3  262.23  5219.7  263.25  5233.9   263.7
  5269.5  266.33  5290.5   267.3  5297.9  267.08  5382.4  269.83  5501.7  272.57
#Mann= 5 ,-1 , 0
  4410.8     .05       0  5041.8     .12       0  5062.2     .05       0
  5103.8     .03       0  5109.8     .05       0
Bank Sta=5103.8,5109.8
XS Rating Curve= 0 ,0
Exp/Cntr=0.3,0.1

Type RM Length L Ch R = 1 ,797     ,0,0,0
BEGIN DESCRIPTION:
UNT05021 IN WICK 1.0
END DESCRIPTION:
XS GIS Cut Line= 4
      3624606.09     10253719.34      3624706.61     10254116.06
      3625340.94     10254496.66      3625645.61     10254444.58
#Sta/Elev= 30
  4339.7  259.88  4755.6  259.09  4845.1  259.48  4860.3  259.35  4895.3  257.98
  4944.7  258.02  4961.7  258.45  4988.9   257.9  5001.4  254.04  5004.2  253.54
  5007.4  254.04  5011.9  257.62    5020   258.6  5047.2  257.86  5062.7   258.3
  5078.3   258.1  5105.5  258.55  5115.2  259.68  5121.1  258.68  5128.6  258.28
  5151.9  258.65  5179.4  258.21  5193.5  258.61  5317.4  258.57  5412.6  260.05
  5488.7   260.2  5530.5  261.18  5546.9  261.09  5662.1  262.61  5797.8  266.11
#Mann= 5 ,-1 , 0
  4339.7     .05       0  4944.7     .16       0  5001.4     .07       0
  5007.4     .16       0  5193.5     .05       0
Bank Sta=5001.4,5007.4
XS Rating Curve= 0 ,0
Exp/Cntr=0.3,0.1

Chan Stop Cuts=-1
Use User Specified Reach Order=0
Composite Channel Slope=5