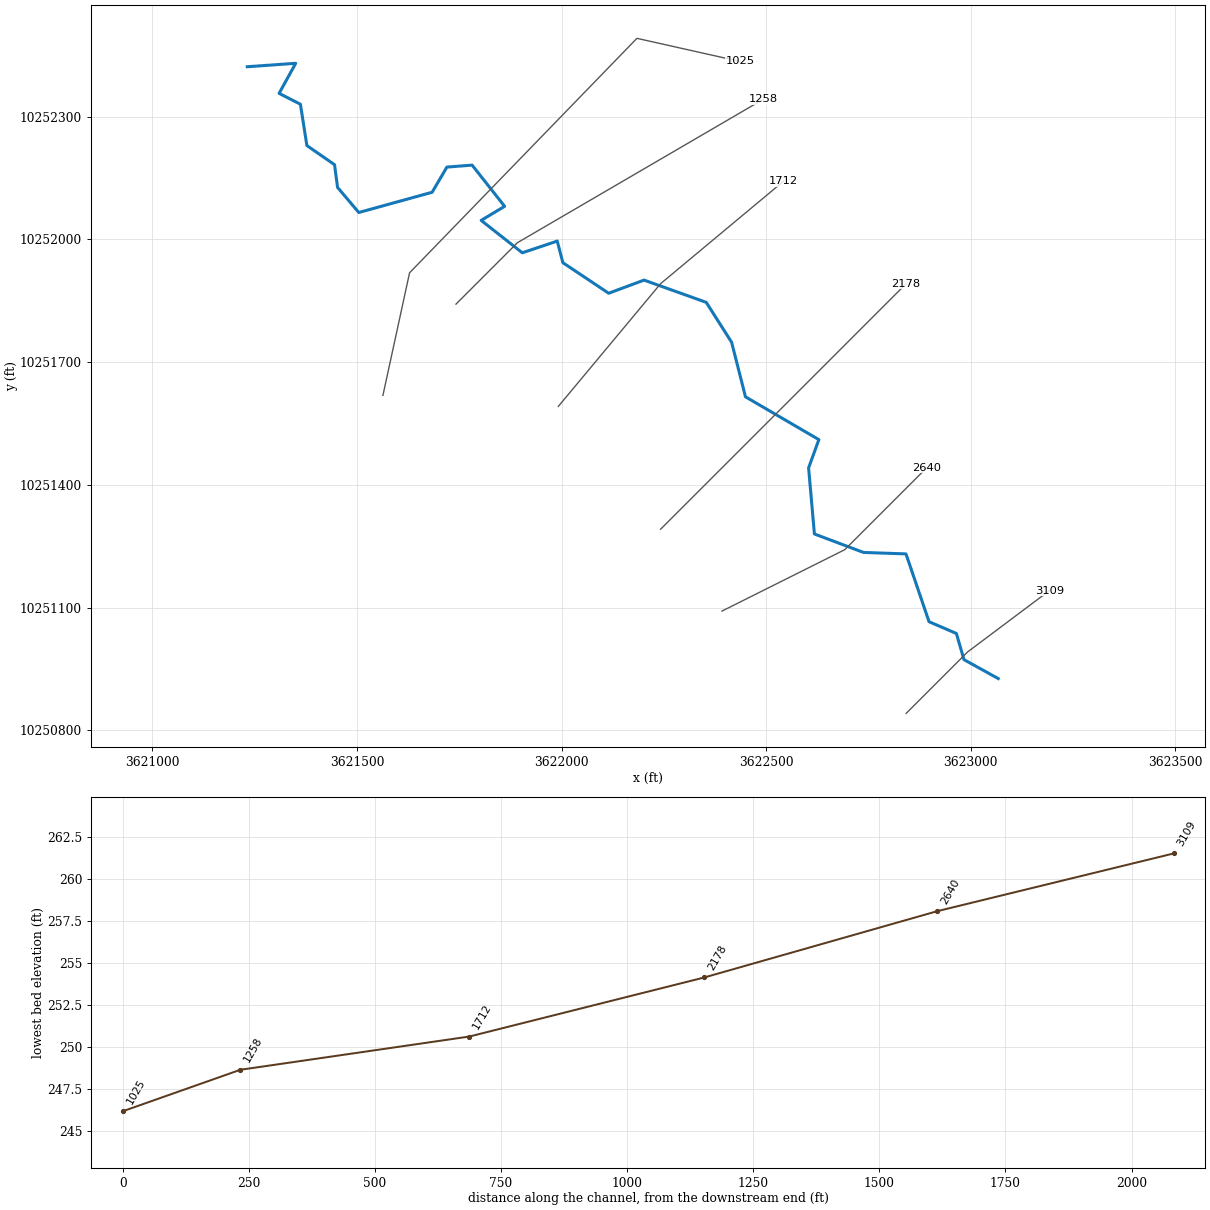
--- UNT05025 IN WICK.prj (project) ---

Proj Title=UNT05025 IN WICK Base Level Engineering
Current Plan=p01
Default Exp/Contr=0.3,0.1
English Units
Geom File=g01
Flow File=f01
Plan File=p01
BEGIN DESCRIPTION:
UNT05025 IN WICK
END DESCRIPTION:

--- UNT05025 IN WICK.p01 (plan) ---

Plan Title=Multiple Run
Short Identifier=Multiple
Geom File=g01
Flow File=f01
Subcritical Flow
K Sum by GR= 0
Std Step Tol= 0.01
Critical Tol= 0.01
Num of Std Step Trials= 20
Max Error Tol= 0.3
Flow Tol Ratio= 0.001
Split Flow NTrial= 30
Split Flow Tol= 0.02
Split Flow Ratio= 0.02
Log Output Level= 0
Friction Slope Method= 1
Unsteady Friction Slope Method= 2
Unsteady Bridges Friction Slope Method= 1
Parabolic Critical Depth
Global Vel Dist=  1 , 1 , 1
Global Log Level= 0
CheckData=True
Encroach Param= -1, 0, 0, 0
BEGIN DESCRIPTION:
Multiple Run
END DESCRIPTION:

--- UNT05025 IN WICK.f01 (steady flow) ---

Flow Title=Multiple
Number of Profiles=7
Profile Names=10-year,25-year,50-year,1pct_min,100-year,1pct_plu,500-year
River Rch & RM= UNT05025 IN WICK,Reach-1,3109
     304     393     464     403     545     737     750
Boundary for River Rch & Prof#=UNT05025 IN WICK,Reach-1,1
Up Type=0
Dn Type=3
Dn Slope=0.005
Boundary for River Rch & Prof#=UNT05025 IN WICK,Reach-1,2
Up Type=0
Dn Type=3
Dn Slope=0.005
Boundary for River Rch & Prof#=UNT05025 IN WICK,Reach-1,3
Up Type=0
Dn Type=3
Dn Slope=0.005
Boundary for River Rch & Prof#=UNT05025 IN WICK,Reach-1,4
Up Type=0
Dn Type=3
Dn Slope=0.005
Boundary for River Rch & Prof#=UNT05025 IN WICK,Reach-1,5
Up Type=0
Dn Type=3
Dn Slope=0.005
Boundary for River Rch & Prof#=UNT05025 IN WICK,Reach-1,6
Up Type=0
Dn Type=3
Dn Slope=0.005
Boundary for River Rch & Prof#=UNT05025 IN WICK,Reach-1,7
Up Type=0
Dn Type=3
Dn Slope=0.005

--- UNT05025 IN WICK.g01 (geometry) ---

Geom Title=Existing Conditions

River Reach=UNT05025 IN WICK,Reach-1
Reach XY= 30
      3623067.11     10250926.64      3622983.34     10250972.92
      3622964.76     10251036.83      3622897.94     10251065.65
      3622841.62     10251231.28      3622737.78     10251234.87
      3622617.87     10251280.01      3622603.69     10251441.50
      3622628.80     10251510.53      3622449.44     10251615.15
      3622415.58     10251748.44      3622353.65     10251845.87
      3622201.61     10251900.31      3622115.18     10251868.18
      3622003.26     10251942.85      3621989.50     10251995.66
      3621904.14     10251967.03      3621803.62     10252046.20
      3621860.91     10252080.57      3621781.52     10252181.24
      3621719.85     10252176.46      3621683.86     10252114.94
      3621504.62     10252065.47      3621452.70     10252126.83
      3621445.30     10252182.33      3621377.77     10252229.05
      3621361.95     10252330.05      3621309.87     10252356.62
      3621350.49     10252430.05      3621232.11     10252421.64

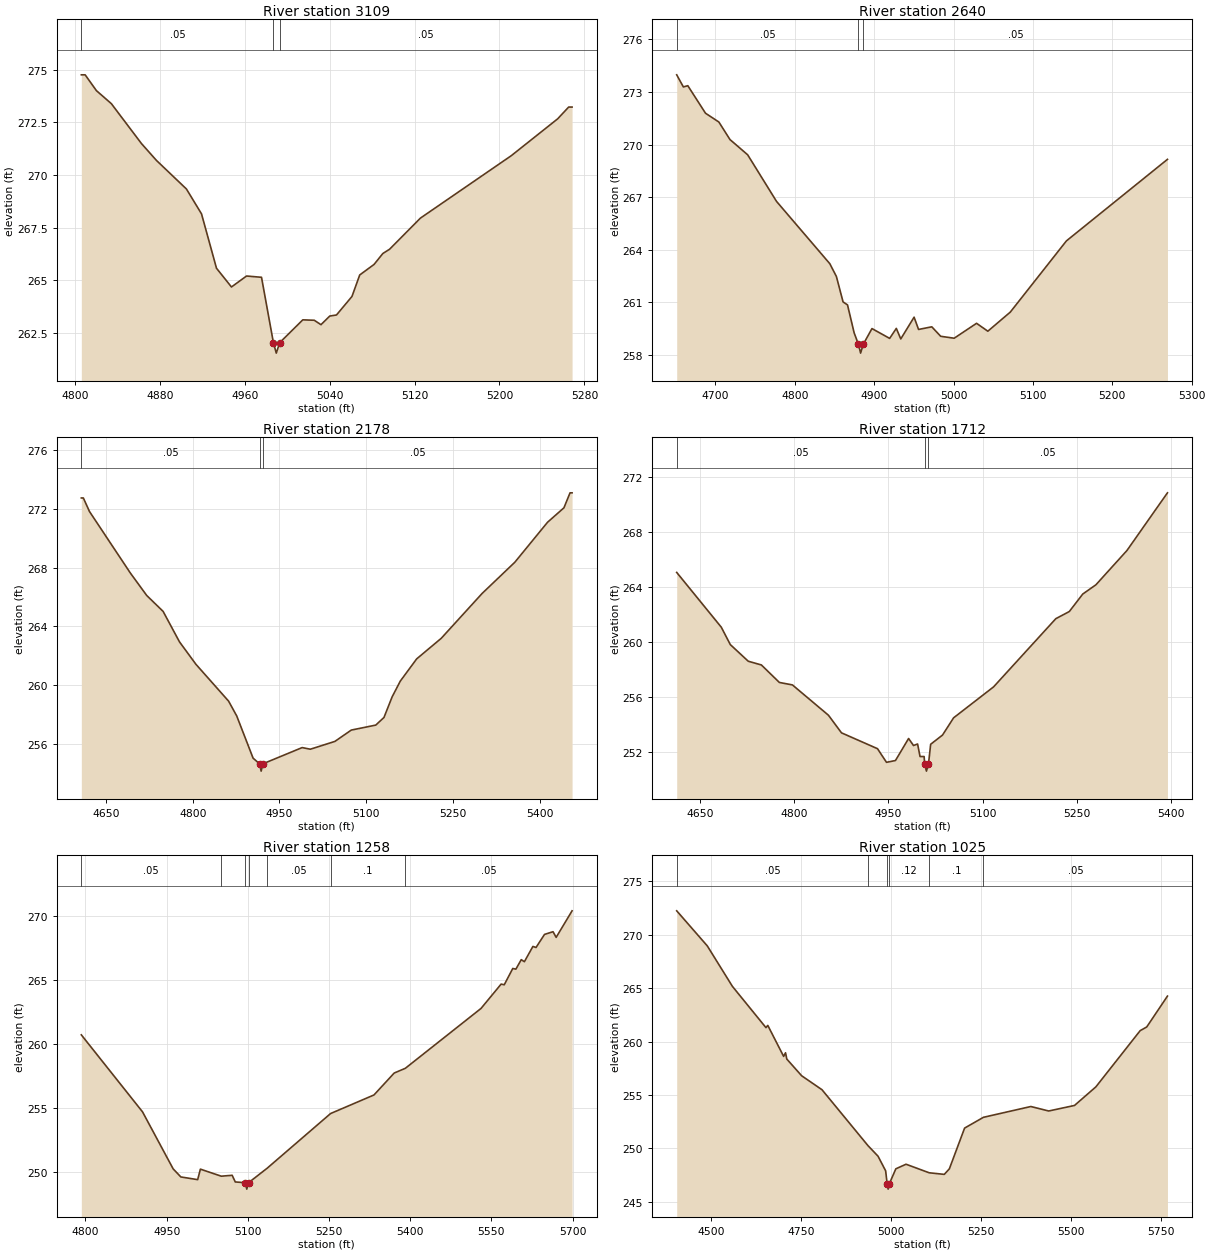
Type RM Length L Ch R = 1,3109,469,469,469
BEGIN DESCRIPTION:
UNT05025 IN WICK 6.0
END DESCRIPTION:
XS GIS Cut Line= 3
      3622842.09     10250841.63      3622992.11     10250991.64
      3623192.14     10251141.67
#Sta/Elev= 30
  4806.2  274.76  4809.8  274.76  4820.4  274.01  4834.5  273.39  4862.8  271.50
  4876.9  270.70  4905.2  269.34  4919.4  268.16  4933.5  265.58  4947.6  264.69
  4961.8  265.21  4975.9  265.15  4987.1  262.05  4989.8  261.55  4993.1  262.05
  5014.8  263.13  5025.6  263.11  5031.9  262.90  5040.2  263.31  5046.5  263.36
  5061.1  264.24  5068.4  265.26  5081.9  265.76  5090.2  266.28  5096.5  266.48
  5125.6  267.96  5211.1  270.92  5254.8  272.67  5265.2  273.23  5268.4  273.23
#Mann=3,-1,0
  4806.2    0.05       0  4987.1    0.03       0  4993.1    0.05       0
Bank Sta=4987.1,4993.1
Exp/Cntr=0.3,0.1

Type RM Length L Ch R = 1,2640,462,462,462
BEGIN DESCRIPTION:
UNT05025 IN WICK 5.0
END DESCRIPTION:
XS GIS Cut Line= 3
      3622392.11     10251091.64      3622692.11     10251241.64
      3622892.14     10251441.68
#Sta/Elev= 30
  4651.2  273.98  4659.6  273.29  4665.2  273.36  4687.5  271.79  4704.3  271.29
  4718.3  270.29  4740.6  269.42  4777.0  266.76  4844.1  263.21  4852.4  262.48
  4860.8  261.03  4866.4  260.86  4874.8  259.26  4880.2  258.61  4882.9  258.11
  4886.2  258.61  4897.2  259.51  4919.5  258.95  4927.9  259.52  4933.5  258.92
  4950.3  260.16  4955.9  259.46  4972.6  259.61  4983.8  259.07  5000.8  258.96
  5029.0  259.81  5043.2  259.36  5071.5  260.45  5142.2  264.51  5269.5  269.16
#Mann=3,-1,0
  4651.2    0.05       0  4880.2    0.03       0  4886.2    0.05       0
Bank Sta=4880.2,4886.2
Exp/Cntr=0.3,0.1

Type RM Length L Ch R = 1,2178,466,466,466
BEGIN DESCRIPTION:
UNT05025 IN WICK 4.0
END DESCRIPTION:
XS GIS Cut Line= 3
      3622242.10     10251291.64      3622542.11     10251591.64
      3622842.08     10251891.62
#Sta/Elev= 30
  4607.4  272.73  4610.9  272.73  4621.5  271.81  4692.3  267.62  4720.5  266.10
  4748.8  265.02  4777.1  262.95  4805.4  261.43  4862.0  258.92  4876.1  257.91
  4904.4  255.04  4915.5  254.66  4918.3  254.16  4921.5  254.66  4989.2  255.76
  5003.4  255.65  5045.8  256.18  5074.1  256.95  5116.5  257.29  5130.7  257.81
  5144.8  259.21  5158.9  260.28  5187.2  261.79  5229.7  263.19  5300.4  266.24
  5356.9  268.36  5413.5  271.08  5441.8  272.06  5452.4  273.08  5455.9  273.08
#Mann=3,-1,0
  4607.4    0.05       0  4915.5    0.03       0  4921.5    0.05       0
Bank Sta=4915.5,4921.5
Exp/Cntr=0.3,0.1

Type RM Length L Ch R = 1,1712,454,454,454
BEGIN DESCRIPTION:
UNT05025 IN WICK 3.0
END DESCRIPTION:
XS GIS Cut Line= 3
      3621992.08     10251591.62      3622242.11     10251891.64
      3622542.14     10252141.67
#Sta/Elev= 30
  4613.1  265.07  4684.1  261.09  4698.4  259.83  4727.0  258.62  4747.9  258.35
  4776.5  257.08  4797.3  256.90  4854.6  254.70  4875.4  253.42  4932.7  252.27
  4947.0  251.28  4961.3  251.41  4982.2  253.01  4990.0  252.50  4996.5  252.61
  5000.4  251.70  5006.9  251.70  5007.8  251.14  5010.6  250.64  5013.8  251.14
  5017.3  252.59  5036.2  253.26  5053.8  254.51  5117.5  256.76  5216.5  261.71
  5238.0  262.23  5259.4  263.50  5280.3  264.17  5329.7  266.66  5394.2  270.85
#Mann=3,-1,0
  4613.1    0.05       0  5007.8    0.03       0  5013.8    0.05       0
Bank Sta=5007.8,5013.8
Exp/Cntr=0.3,0.1

Type RM Length L Ch R = 1,1258,233,233,233
BEGIN DESCRIPTION:
UNT05025 IN WICK 2.0
END DESCRIPTION:
XS GIS Cut Line= 3
      3621742.10     10251841.64      3621892.11     10251991.64
      3622492.14     10252341.66
#Sta/Elev= 30
  4792.3  260.70  4905.4  254.69  4962.0  250.24  4976.2  249.61  5007.3  249.40
  5012.3  250.22  5050.9  249.67  5071.0  249.74  5076.8  249.22  5095.3  249.16
  5098.0  248.66  5101.3  249.16  5135.9  250.30  5252.9  254.56  5333.1  256.01
  5370.4  257.72  5391.0  258.09  5530.8  262.76  5568.0  264.66  5573.8  264.61
  5589.5  265.88  5595.3  265.83  5605.2  266.57  5611.0  266.41  5626.7  267.60
  5632.5  267.52  5648.2  268.54  5663.9  268.75  5669.7  268.31  5699.1  270.38
#Mann=7,-1,0
  4792.3    0.05       0  5050.9    0.12       0  5095.3    0.03       0
  5101.3    0.12       0  5135.9    0.05       0  5252.9     0.1       0
  5391.0    0.05       0
Bank Sta=5095.3,5101.3
Exp/Cntr=0.3,0.1

Type RM Length L Ch R = 1,1025,0,0,0
BEGIN DESCRIPTION:
UNT05025 IN WICK 1.0
END DESCRIPTION:
XS GIS Cut Line= 4
      3621563.56     10251618.65      3621628.66     10251918.13
      3622184.22     10252491.05      3622435.95     10252434.62
#Sta/Elev= 30
  4404.8  272.23  4489.7  268.95  4559.5  265.16  4652.6  261.30  4657.7  261.51
  4701.7  258.61  4706.9  258.95  4710.5  258.36  4751.6  256.80  4808.2  255.49
  4936.1  250.25  4963.8  249.27  4984.9  247.90  4989.1  246.69  4991.8  246.19
  4995.1  246.69  5013.2  248.09  5041.5  248.52  5105.7  247.72  5147.7  247.57
  5161.8  248.09  5204.1  251.90  5256.4  252.91  5388.0  253.92  5437.6  253.50
  5509.3  254.02  5568.6  255.76  5691.6  261.02  5709.7  261.36  5767.3  264.25
#Mann=6,-1,0
  4404.8    0.05       0  4936.1    0.12       0  4989.1    0.07       0
  4995.1    0.12       0  5105.7     0.1       0  5256.4    0.05       0
Bank Sta=4989.1,4995.1
Exp/Cntr=0.3,0.1

Chan Stop Cuts=-1