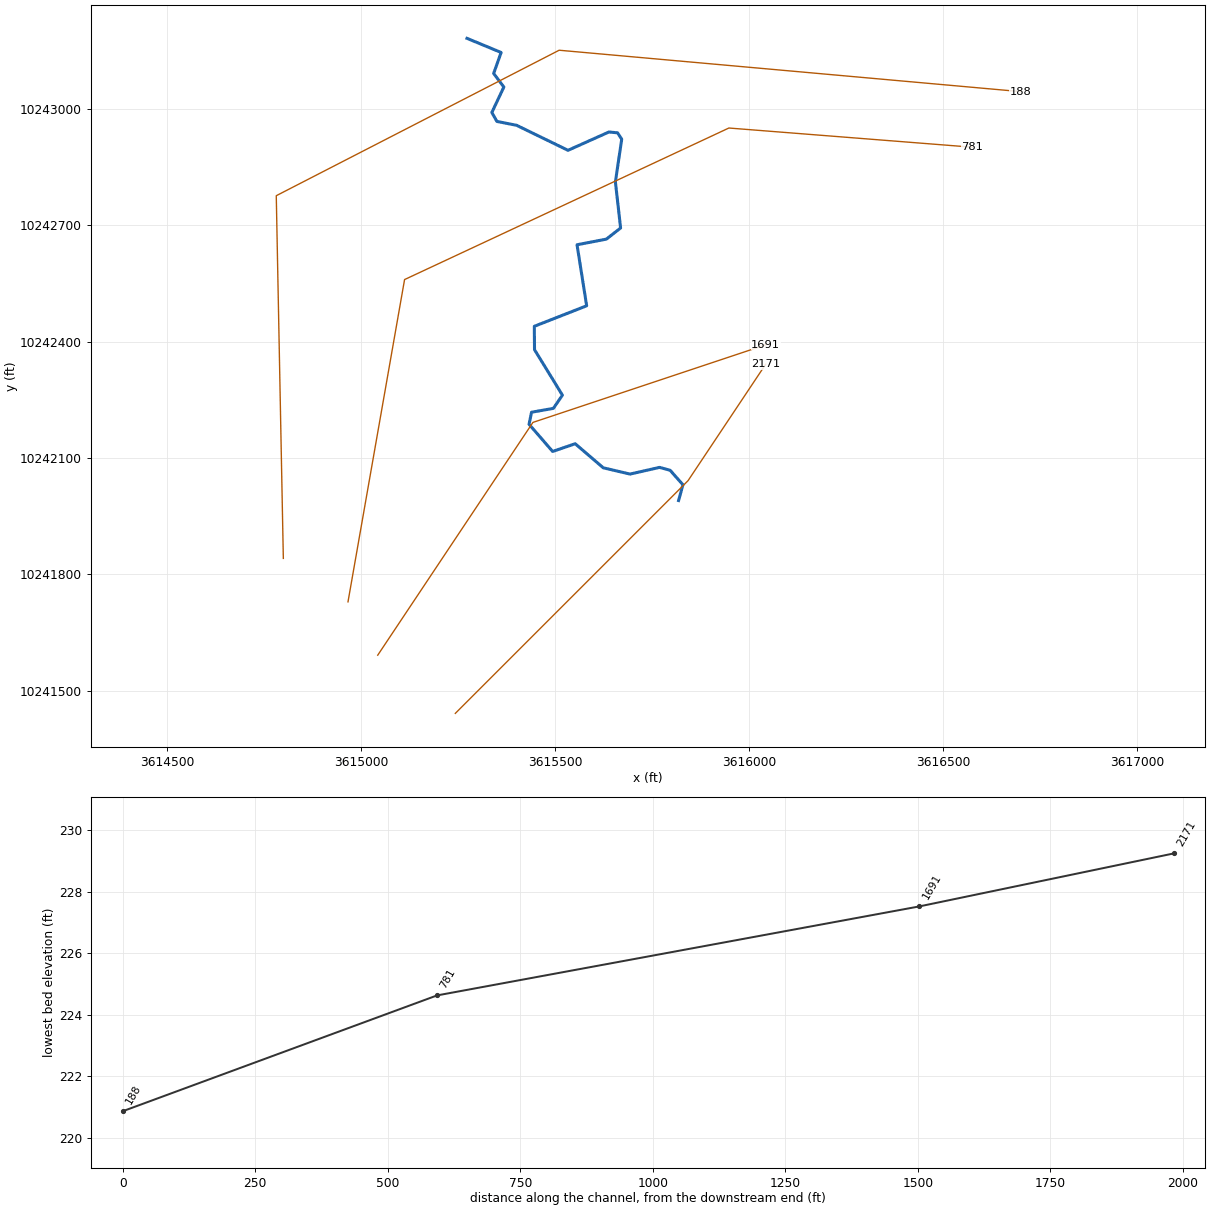
--- UNT05058 IN WICK.prj (project) ---

Proj Title=UNT05058 IN WICK Base Level Engineering
Current Plan=p01
Default Exp/Contr=0.3,0.1
English Units
Geom File=g01
Flow File=f01
Plan File=p01
BEGIN DESCRIPTION:
UNT05058 IN WICK
END DESCRIPTION:

--- UNT05058 IN WICK.p01 (plan) ---

Plan Title=Multiple Run
Short Identifier=Multiple
Geom File=g01
Flow File=f01
Subcritical Flow
K Sum by GR= 0
Std Step Tol= 0.01
Critical Tol= 0.01
Num of Std Step Trials= 20
Max Error Tol= 0.3
Flow Tol Ratio= 0.001
Split Flow NTrial= 30
Split Flow Tol= 0.02
Split Flow Ratio= 0.02
Log Output Level= 0
Friction Slope Method= 1
Unsteady Friction Slope Method= 2
Unsteady Bridges Friction Slope Method= 1
Parabolic Critical Depth
Global Vel Dist=  1 , 1 , 1
Global Log Level= 0
CheckData=True
Encroach Param= -1, 0, 0, 0
BEGIN DESCRIPTION:
Multiple Run
END DESCRIPTION:

--- UNT05058 IN WICK.f01 (steady flow) ---

Flow Title=Multiple
Number of Profiles=7
Profile Names=10-year,25-year,50-year,1pct_min,100-year,1pct_plu,500-year
River Rch & RM= UNT05058 IN WICK,Reach-1,2171
     490     654     787     695     939    1271    1341
Boundary for River Rch & Prof#=UNT05058 IN WICK,Reach-1,1
Up Type=0
Dn Type=3
Dn Slope=0.005
Boundary for River Rch & Prof#=UNT05058 IN WICK,Reach-1,2
Up Type=0
Dn Type=3
Dn Slope=0.005
Boundary for River Rch & Prof#=UNT05058 IN WICK,Reach-1,3
Up Type=0
Dn Type=3
Dn Slope=0.005
Boundary for River Rch & Prof#=UNT05058 IN WICK,Reach-1,4
Up Type=0
Dn Type=3
Dn Slope=0.005
Boundary for River Rch & Prof#=UNT05058 IN WICK,Reach-1,5
Up Type=0
Dn Type=3
Dn Slope=0.005
Boundary for River Rch & Prof#=UNT05058 IN WICK,Reach-1,6
Up Type=0
Dn Type=3
Dn Slope=0.005
Boundary for River Rch & Prof#=UNT05058 IN WICK,Reach-1,7
Up Type=0
Dn Type=3
Dn Slope=0.005

--- UNT05058 IN WICK.g01 (geometry) ---

Geom Title=Existing Conditions

River Reach=UNT05058 IN WICK,Reach-1
Reach XY= 30
      3615817.58     10241990.25      3615828.79     10242030.91
      3615795.81     10242068.25      3615768.56     10242075.72
      3615692.47     10242058.45      3615623.38     10242074.66
      3615551.05     10242136.65      3615492.91     10242116.78
      3615432.16     10242186.92      3615438.59     10242217.87
      3615494.82     10242227.83      3615518.19     10242261.89
      3615446.25     10242379.04      3615445.69     10242439.36
      3615580.63     10242492.23      3615555.82     10242649.53
      3615631.48     10242664.09      3615668.11     10242692.74
      3615654.72     10242811.60      3615671.03     10242921.76
      3615660.20     10242938.12      3615637.91     10242940.16
      3615532.59     10242893.01      3615400.11     10242957.45
      3615349.28     10242967.44      3615336.21     10242990.48
      3615367.20     10243056.11      3615340.86     10243091.08
      3615360.14     10243145.19      3615272.11     10243181.64

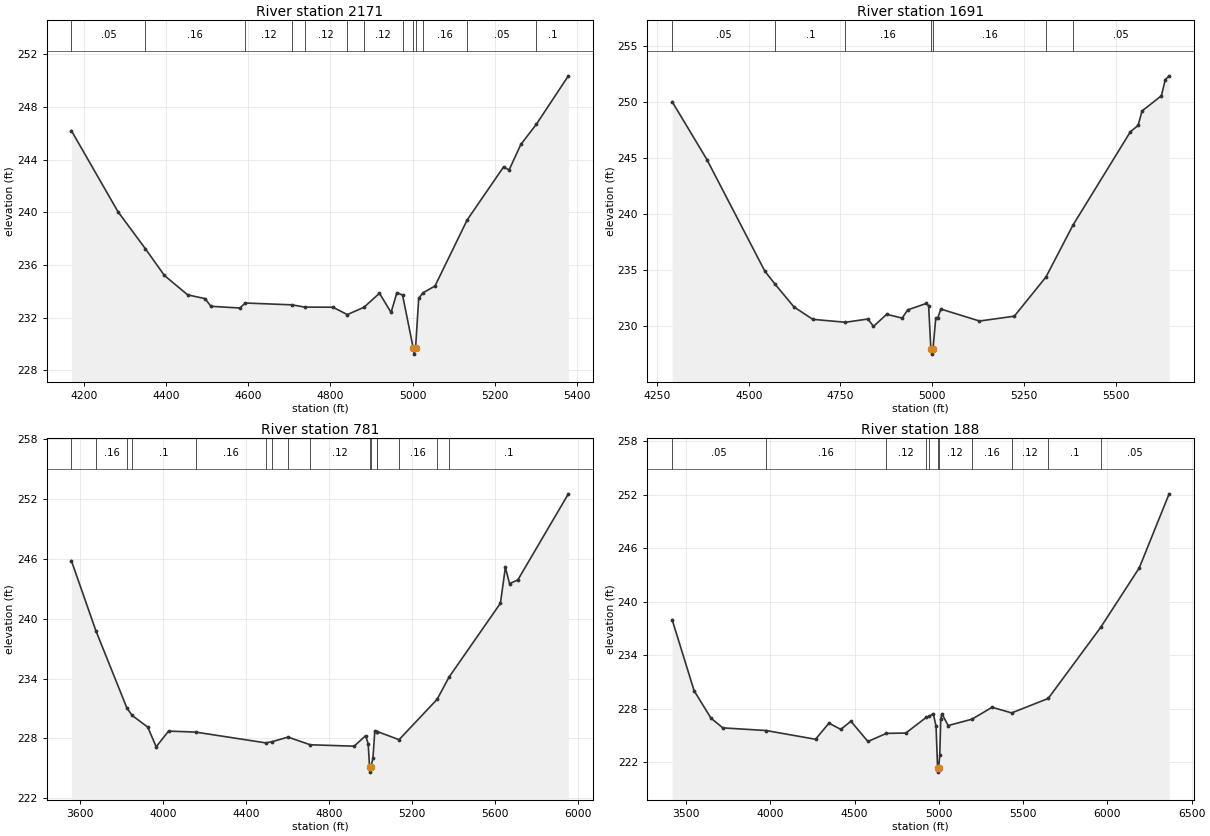
Type RM Length L Ch R = 1,2171,480,480,480
BEGIN DESCRIPTION:
UNT05058 IN WICK 3.0
END DESCRIPTION:
XS GIS Cut Line= 3
      3615242.11     10241441.65      3615842.11     10242041.64
      3616042.12     10242341.67
#Sta/Elev= 30
  4169.8  246.20  4282.9  240.06  4349.8  237.24  4396.1  235.21  4452.6  233.74
  4495.1  233.45  4509.2  232.87  4579.9  232.74  4592.6  233.12  4706.7  232.98
  4737.2  232.81  4806.2  232.80  4841.1  232.24  4881.8  232.80  4919.3  233.86
  4947.6  232.40  4961.7  233.91  4975.5  233.72  5001.2  229.74  5003.9  229.24
  5007.2  229.74  5014.8  233.48  5025.1  233.89  5054.4  234.41  5132.8  239.43
  5221.1  243.44  5234.7  243.22  5263.2  245.15  5300.9  246.68  5378.9  250.36
#Mann=13,-1,0
  4169.8    0.05       0  4349.8    0.16       0  4592.6    0.12       0
  4706.7    0.16       0  4737.2    0.12       0  4841.1    0.16       0
  4881.8    0.12       0  4975.5    0.05       0  5001.2    0.04       0
  5007.2    0.05       0  5025.1    0.16       0  5132.8    0.05       0
  5300.9     0.1       0
Bank Sta=5001.2,5007.2
Exp/Cntr=0.3,0.1

Type RM Length L Ch R = 1,1691,910,910,910
BEGIN DESCRIPTION:
UNT05058 IN WICK 2.0
END DESCRIPTION:
XS GIS Cut Line= 3
      3615042.10     10241591.64      3615442.11     10242191.64
      3616042.13     10242391.65
#Sta/Elev= 30
  4291.5  250.02  4386.2  244.86  4543.9  234.92  4572.4  233.73  4623.5  231.72
  4674.6  230.62  4763.5  230.36  4824.8  230.65  4839.8  229.99  4875.9  231.07
  4918.0  230.73  4933.0  231.46  4984.1  232.04  4990.1  231.84  4996.1  228.02
  4998.8  227.52  5002.1  228.02  5009.6  230.76  5015.3  230.76  5023.2  231.54
  5128.6  230.47  5223.4  230.90  5309.8  234.40  5383.1  239.01  5539.7  247.34
  5560.7  247.90  5571.3  249.19  5624.0  250.54  5634.5  251.96  5645.1  252.32
#Mann=7,-1,0
  4291.5    0.05       0  4572.4     0.1       0  4763.5    0.16       0
  4996.1    0.07       0  5002.1    0.16       0  5309.8    0.16       0
  5383.1    0.05       0
Bank Sta=4996.1,5002.1
Exp/Cntr=0.3,0.1

Type RM Length L Ch R = 1,781,593,593,593
BEGIN DESCRIPTION:
Mapping XS f8132c47
END DESCRIPTION:
XS GIS Cut Line= 4
      3614965.45     10241729.10      3615111.29     10242559.84
      3615947.23     10242950.47      3616574.83     10242900.99
#Sta/Elev= 30
  3556.6  245.81  3674.7  238.79  3824.3  231.05  3849.5  230.31  3924.7  229.14
  3965.3  227.17  4025.0  228.74  4156.0  228.64  4493.9  227.56  4524.1  227.68
  4600.9  228.14  4708.0  227.37  4919.7  227.23  4974.9  228.28  4987.2  227.48
  4994.0  225.13  4996.7  224.63  5000.0  225.13  5010.1  226.01  5019.1  228.72
  5029.3  228.67  5030.7  228.70  5136.1  227.88  5319.8  231.93  5376.5  234.13
  5624.7  241.55  5648.6  245.14  5668.7  243.51  5708.8  243.89  5952.3  252.51
#Mann=16,-1,0
  3556.6    0.05       0  3674.7    0.16       0  3824.3    0.05       0
  3849.5     0.1       0  4156.0    0.16       0  4493.9    0.12       0
  4524.1    0.07       0  4600.9    0.16       0  4708.0    0.12       0
  4994.0    0.07       0  5000.0    0.12       0  5029.3    0.16       0
  5030.7    0.12       0  5136.1    0.16       0  5319.8    0.12       0
  5376.5     0.1       0
Bank Sta=4994,5000
Exp/Cntr=0.3,0.1

Type RM Length L Ch R = 1,188,0,0,0
BEGIN DESCRIPTION:
UNT05058 IN WICK 1.0
END DESCRIPTION:
XS GIS Cut Line= 4
      3614798.79     10241841.10      3614780.56     10242775.99
      3615509.73     10243150.99      3616698.44     10243044.34
#Sta/Elev= 30
  3417.8  237.99  3548.4  230.00  3648.4  226.93  3718.4  225.84  3975.6  225.54
  4268.5  224.56  4348.2  226.37  4418.2  225.67  4478.3  226.58  4579.5  224.31
  4688.5  225.22  4804.4  225.26  4926.1  227.03  4943.2  227.14  4967.0  227.44
  4983.5  226.03  4992.6  221.37  4995.3  220.87  4998.6  221.37  5005.7  222.76
  5011.3  226.83  5018.1  227.42  5055.7  226.10  5196.0  226.81  5315.8  228.15
  5432.2  227.52  5648.9  229.14  5960.9  237.14  6189.3  243.81  6366.3  252.12
#Mann=11,-1,0
  3417.8    0.05       0  3975.6    0.16       0  4688.5    0.12       0
  4926.1    0.16       0  4943.2    0.12       0  4992.6    0.07       0
  4998.6    0.12       0  5196.0    0.16       0  5432.2    0.12       0
  5648.9     0.1       0  5960.9    0.05       0
Bank Sta=4992.6,4998.6
Exp/Cntr=0.3,0.1

Chan Stop Cuts=-1