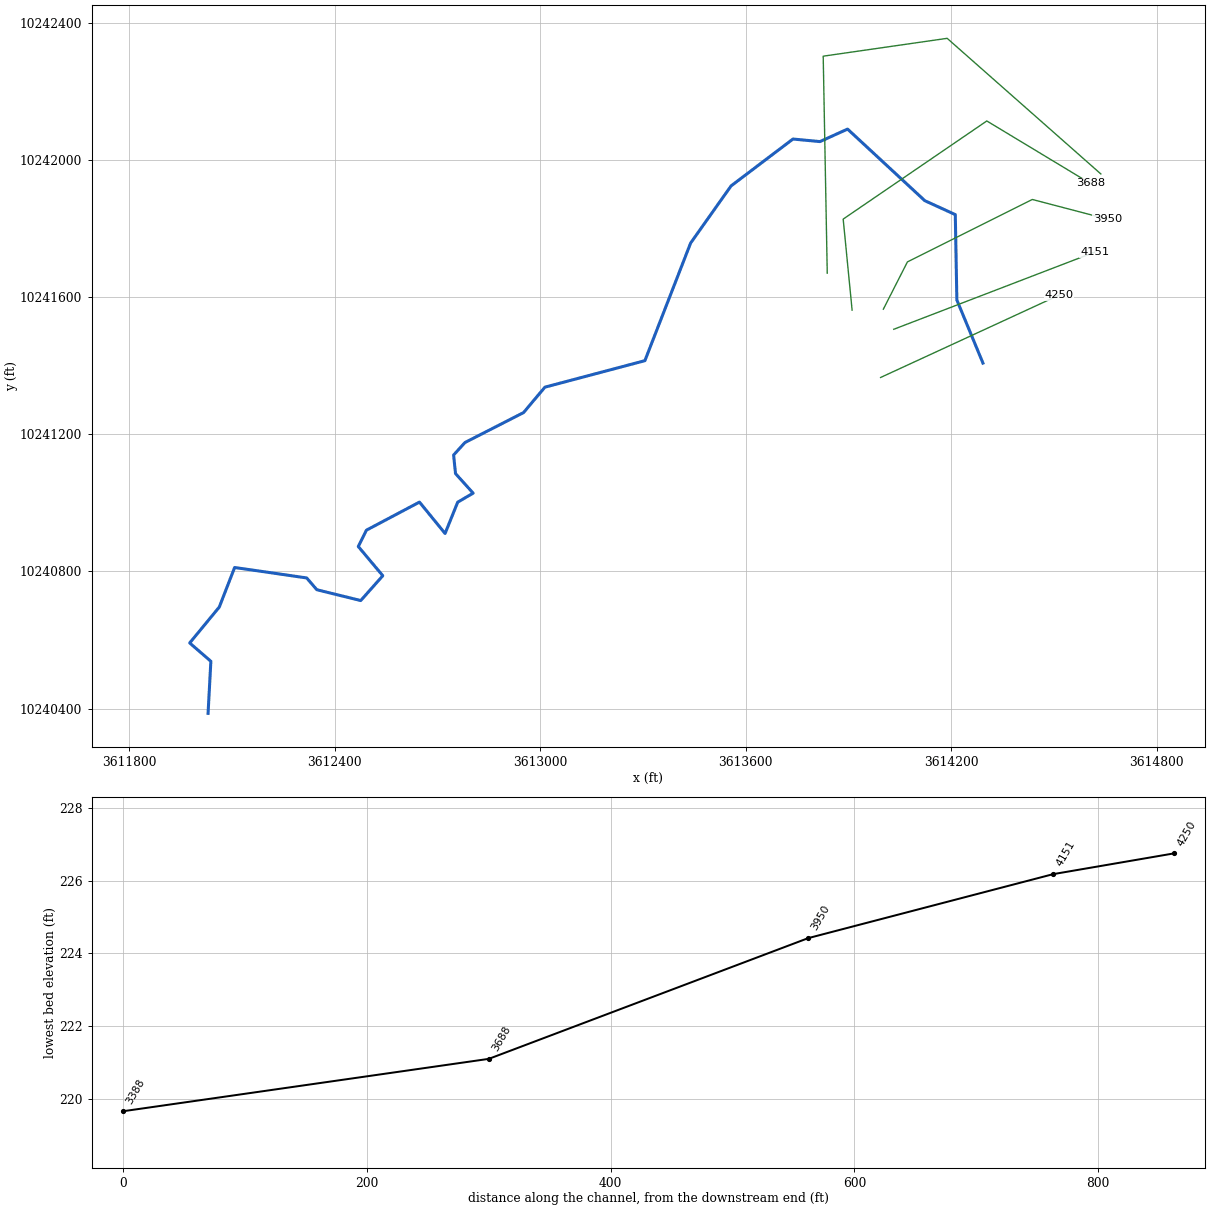
--- UNT05062 IN WICK.prj (project) ---

Proj Title=UNT05062 IN WICK Base Level Engineering
Current Plan=p01
Default Exp/Contr=0.3,0.1
English Units
Geom File=g01
Flow File=f01
Plan File=p01
Y Axis Title=Elevation
X Axis Title(PF)=Main Channel Distance
X Axis Title(XS)=Station
BEGIN DESCRIPTION:
UNT05062 IN WICK
END DESCRIPTION:
DSS Export Rating Curves= 0
DSS Export Rating Curve Sorted= 0
DSS Export Volume Flow Curves= 0
DXF OffsetX= 0
DXF OffsetY= 0
DXF ScaleX= 1
DXF ScaleY= 10

--- UNT05062 IN WICK.p01 (plan) ---

Plan Title=Multiple Run
Short Identifier=Multiple
Geom File=g01
Flow File=f01
Subcritical Flow
K Sum by GR= 0
Std Step Tol= 0.01
Critical Tol= 0.01
Num of Std Step Trials= 20
Max Error Tol= 0.3
Flow Tol Ratio= 0.001
Split Flow NTrial= 30
Split Flow Tol= 0.02
Split Flow Ratio= 0.02
Log Output Level= 0
Friction Slope Method= 1
Unsteady Friction Slope Method= 2
Unsteady Bridges Friction Slope Method= 1
Parabolic Critical Depth
Global Vel Dist=  1 , 1 , 1
Global Log Level= 0
CheckData=True
Encroach Param= -1, 0, 0, 0
BEGIN DESCRIPTION:
Multiple Run
END DESCRIPTION:

--- UNT05062 IN WICK.f01 (steady flow) ---

Flow Title=Multiple
Program Version=4.10
Number of Profiles= 7
Profile Names=10-year,25-year,50-year,1pct_min,100-year,1pct_plu,500-year
River Rch & RM=UNT05062 IN WICK,Reach-1         ,4250
     284     366     430     372     502     680     686
Boundary for River Rch & Prof#=UNT05062 IN WICK,Reach-1         , 1
Up Type= 0
Dn Type= 3
Dn Slope=0.0128
Boundary for River Rch & Prof#=UNT05062 IN WICK,Reach-1         , 2
Up Type= 0
Dn Type= 3
Dn Slope=0.0128
Boundary for River Rch & Prof#=UNT05062 IN WICK,Reach-1         , 3
Up Type= 0
Dn Type= 3
Dn Slope=0.0128
Boundary for River Rch & Prof#=UNT05062 IN WICK,Reach-1         , 4
Up Type= 0
Dn Type= 3
Dn Slope=0.0128
Boundary for River Rch & Prof#=UNT05062 IN WICK,Reach-1         , 5
Up Type= 0
Dn Type= 3
Dn Slope=0.0128
Boundary for River Rch & Prof#=UNT05062 IN WICK,Reach-1         , 6
Up Type= 0
Dn Type= 3
Dn Slope=0.0128
Boundary for River Rch & Prof#=UNT05062 IN WICK,Reach-1         , 7
Up Type= 0
Dn Type= 3
Dn Slope=0.0128
DSS Import GetInterval= 0
DSS Import GetPeak= 0
DSS Import FillOption= 0

--- UNT05062 IN WICK.g01 (geometry) ---

Geom Title=Existing Conditions
Program Version=4.10

River Reach=UNT05062 IN WICK,Reach-1
Reach XY= 30
      3614292.19     10241408.25      3614216.03     10241592.29
      3614211.43     10241841.69      3614122.39     10241882.39
      3613897.04     10242091.32      3613816.38     10242054.84
      3613737.61     10242062.29      3613556.83     10241925.32
      3613438.92     10241758.73      3613305.39     10241415.33
      3613013.51     10241337.95      3612951.17     10241263.78
      3612780.09     10241176.32      3612747.04     10241139.91
      3612752.61     10241085.73      3612804.06      10241028.6
      3612759.02     10241002.32      3612722.12     10240910.87
      3612647.41     10241002.53      3612492.48     10240920.48
      3612468.78     10240872.81      3612540.34     10240787.63
      3612475.92     10240715.11      3612347.74     10240746.78
      3612318.19     10240781.16      3612107.87     10240811.58
      3612062.98     10240696.05      3611976.66     10240591.32
      3612038.47     10240537.85      3612030.29     10240385.79

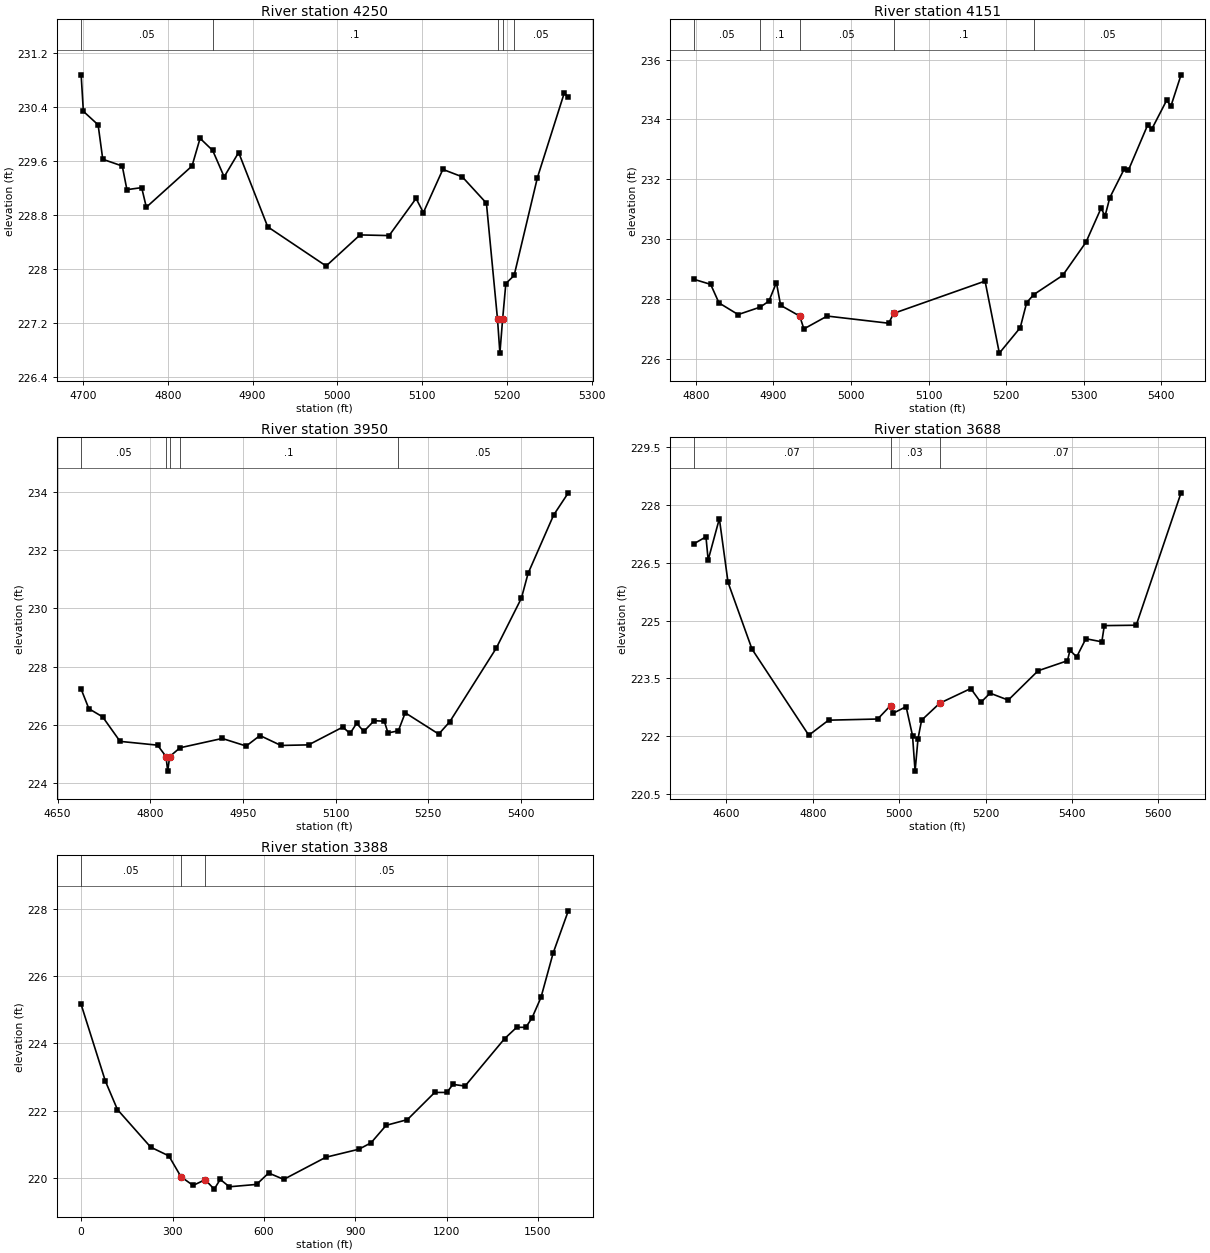
Type RM Length L Ch R = 1 ,4250    ,99,99,99
BEGIN DESCRIPTION:
UNT05062 IN WICK 6.0
END DESCRIPTION:
XS GIS Cut Line= 2
      3613993.35     10241366.21       3614515.2     10241606.95
#Sta/Elev= 30
  4697.8  230.87  4700.4  230.33  4717.8  230.13  4723.3  229.62  4746.3  229.52
  4751.8  229.17  4769.2   229.2  4774.7  228.91  4828.6  229.52  4838.1  229.93
    4853  229.75  4866.5  229.36  4883.6  229.72  4917.9  228.62  4986.8  228.04
  5026.8   228.5  5061.1  228.49  5092.9  229.04  5101.5  228.83  5124.5  229.47
  5147.4  229.36  5175.9  228.97    5189  227.25  5191.8  226.75    5195  227.25
  5198.8  227.78  5208.6   227.9  5236.1  229.35  5267.7   230.6  5272.5  230.54
#Mann= 5 ,-1 , 0
  4697.8     .05       0    4853      .1       0    5189     .07       0
    5195      .1       0  5208.6     .05       0
Bank Sta=5189,5195
XS Rating Curve= 0 ,0
Exp/Cntr=0.3,0.1

Type RM Length L Ch R = 1 ,4151    ,201,201,201
BEGIN DESCRIPTION:
Mapping XS f28853d5
END DESCRIPTION:
XS GIS Cut Line= 2
      3614031.93     10241506.98      3614617.82     10241731.95
#Sta/Elev= 30
  4797.7  228.65  4819.3  228.48    4830  227.86  4854.7  227.47  4883.2  227.72
  4894.3  227.92    4904  228.54  4909.4  227.78    4934  227.42  4939.4  226.99
  4969.4  227.42  5048.7  227.18    5055  227.51  5172.8  228.59  5191.2  226.18
  5218.1  227.03  5226.4  227.87  5235.6  228.14  5272.8  228.78  5302.8  229.89
  5322.1  231.02  5327.5  230.78  5333.5  231.38  5352.1  232.34  5357.5   232.3
  5382.1   233.8  5387.5  233.67  5406.8  234.64  5412.2  234.44  5425.3  235.49
#Mann= 5 ,-1 , 0
  4797.7     .05       0  4883.2      .1       0    4934     .05       0
    5055      .1       0  5235.6     .05       0
Bank Sta=4934,5055
XS Rating Curve= 0 ,0
Exp/Cntr=0.3,0.1

Type RM Length L Ch R = 1 ,3950    ,262,262,262
BEGIN DESCRIPTION:
Mapping XS 0b355405
END DESCRIPTION:
XS GIS Cut Line= 4
      3614001.37     10241565.54       3614071.7     10241703.59
      3614436.28     10241885.89      3614655.06     10241828.59
#Sta/Elev= 30
    4688  227.23  4700.5  226.56  4722.8  226.28    4751  225.44  4811.7  225.31
  4825.4  224.92  4828.1  224.42  4831.4  224.92    4848  225.22  4916.4  225.54
  4955.2  225.28  4977.5  225.64  5011.5   225.3  5056.2  225.32  5111.7  225.93
  5123.3  225.71  5134.1  226.06  5145.6  225.78  5162.4  226.15  5178.8  226.13
  5184.8  225.73  5201.5   225.8  5212.7  226.42  5266.9  225.69  5284.7  226.11
  5359.9  228.63  5400.8  230.35  5411.6   231.2    5453   233.2  5476.7  233.96
#Mann= 5 ,-1 , 0
    4688     .05       0  4825.4     .07       0  4831.4     .05       0
    4848      .1       0  5201.5     .05       0
Bank Sta=4825.4,4831.4
XS Rating Curve= 0 ,0
Exp/Cntr=0.3,0.1

Type RM Length L Ch R = 1 ,3688    ,300,300,300
BEGIN DESCRIPTION:
UNT05062 IN WICK 1.0
END DESCRIPTION:
XS GIS Cut Line= 4
      3613910.24     10241562.99       3613884.2     10241828.59
      3614303.47     10242115.05      3614605.57     10241932.75
#Sta/Elev= 30
  4524.9  226.99  4552.8  227.17  4557.9  226.57  4583.8  227.64  4603.9  225.99
  4659.4  224.26  4790.8  222.03  4836.6  222.42  4950.3  222.45  4980.1   222.8
  4986.2   222.6    5016  222.77  5030.9  222.02  5036.8   221.1  5043.6  221.94
  5051.9  222.42  5093.9  222.86  5165.7  223.24  5188.9  222.88  5210.4  223.12
  5252.4  222.94  5321.5   223.7  5389.4  223.96  5395.3  224.23  5410.8  224.06
  5432.1  224.53    5469  224.45  5474.8  224.87  5548.6  224.88  5652.4  228.31
#Mann= 3 , 0 , 0
  4524.9     .07       0  4980.1     .03       0  5093.9     .07       0
Bank Sta=4980.1,5093.9
XS Rating Curve= 0 ,0
Exp/Cntr=0.3,0.1

Type RM Length L Ch R = 1 ,3388    ,0,0,0
XS GIS Cut Line= 4
     3613837.697    10241670.813     3613825.891    10242304.146
     3614187.697    10242356.229     3614636.308    10241960.396
#Sta/Elev= 30
       0  225.16   79.44  222.88  119.16  222.03   228.4  220.91  287.98  220.65
   327.7  220.03  367.42  219.77  407.14  219.94  436.93  219.66  456.79  219.95
  486.59  219.73  575.96   219.8  615.68  220.14  665.21  219.95  803.67  220.61
  912.46  220.85  952.02  221.04 1001.47  221.56 1071.26  221.73    1161  222.54
 1200.88  222.54 1220.82  222.78  1260.7  222.73 1390.31  224.14 1430.19  224.48
  1460.1  224.48 1480.05  224.75 1509.96  225.37 1549.84  226.69 1599.69  227.95
#Mann= 3 , 0 , 0
       0     .05       0   327.7     .03       0  407.14     .05       0
Bank Sta=327.7,407.14
XS Rating Curve= 0 ,0
Exp/Cntr=0.3,0.1

Chan Stop Cuts=-1
Use User Specified Reach Order=0
Composite Channel Slope=5