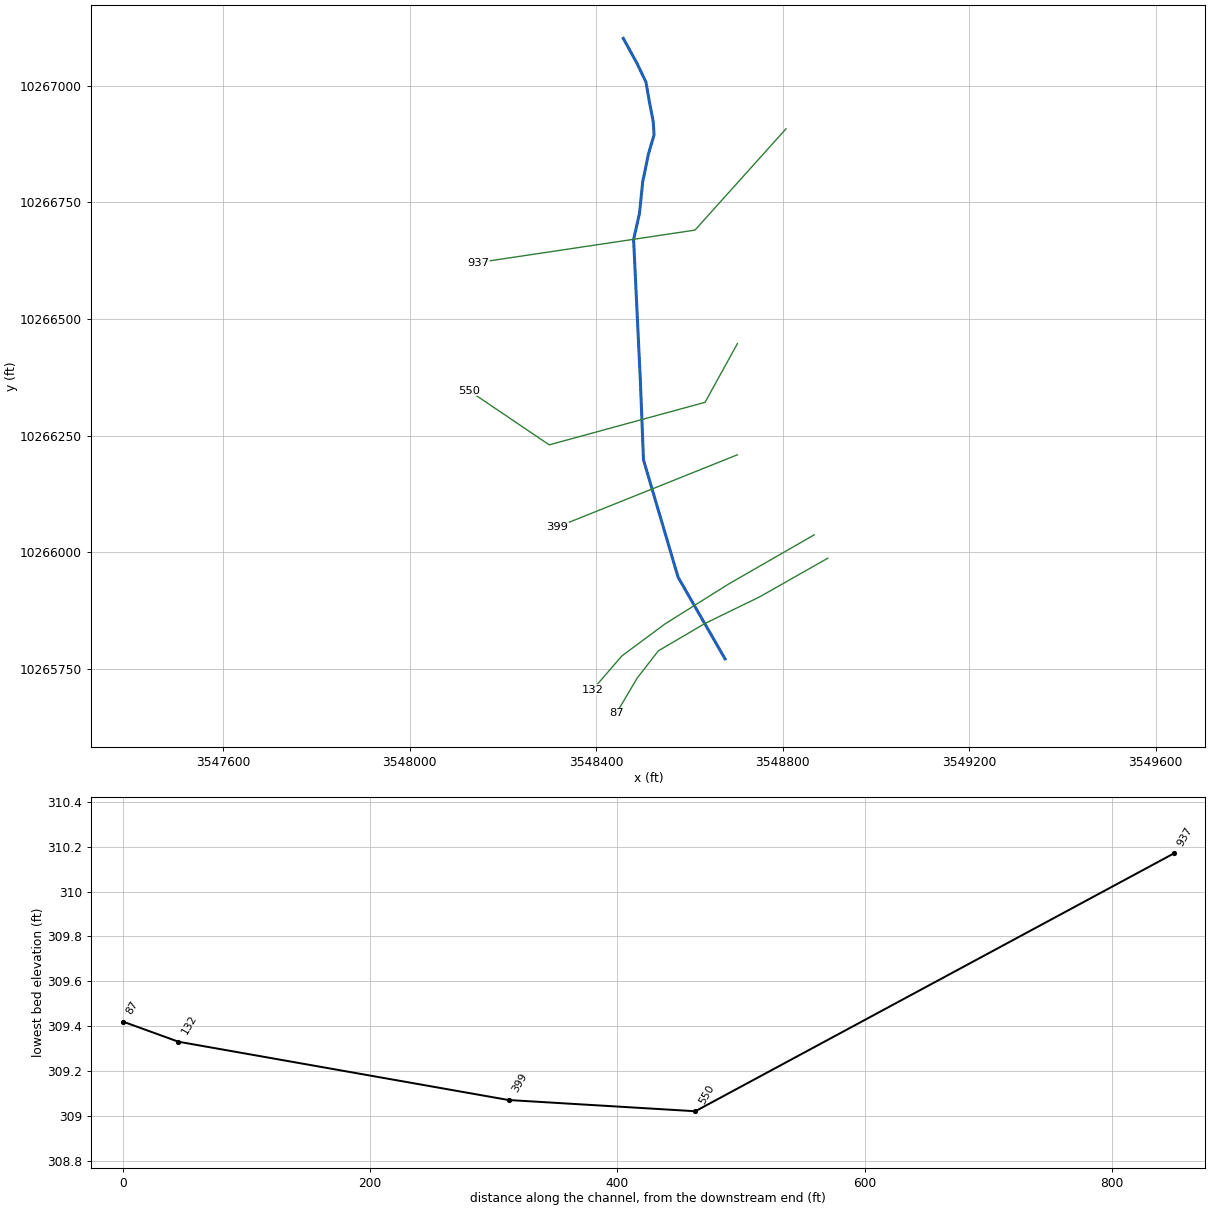
--- UNT05132 IN WICK.prj (project) ---

Proj Title=UNT05132 IN WICK Base Level Engineering
Current Plan=p01
Default Exp/Contr=0.3,0.1
English Units
Geom File=g01
Flow File=f01
Plan File=p01
Y Axis Title=Elevation
X Axis Title(PF)=Main Channel Distance
X Axis Title(XS)=Station
BEGIN DESCRIPTION:
UNT05132 IN WICK
END DESCRIPTION:
DSS Export Rating Curves= 0
DSS Export Rating Curve Sorted= 0
DSS Export Volume Flow Curves= 0
DXF OffsetX= 0
DXF OffsetY= 0
DXF ScaleX= 1
DXF ScaleY= 10

--- UNT05132 IN WICK.p01 (plan) ---

Plan Title=Multiple Run
Short Identifier=Multiple
Geom File=g01
Flow File=f01
Subcritical Flow
K Sum by GR= 0
Std Step Tol= 0.01
Critical Tol= 0.01
Num of Std Step Trials= 20
Max Error Tol= 0.3
Flow Tol Ratio= 0.001
Split Flow NTrial= 30
Split Flow Tol= 0.02
Split Flow Ratio= 0.02
Log Output Level= 0
Friction Slope Method= 1
Unsteady Friction Slope Method= 2
Unsteady Bridges Friction Slope Method= 1
Parabolic Critical Depth
Global Vel Dist=  1 , 1 , 1
Global Log Level= 0
CheckData=True
Encroach Param= -1, 0, 0, 0
BEGIN DESCRIPTION:
Multiple Run
END DESCRIPTION:

--- UNT05132 IN WICK.f01 (steady flow) ---

Flow Title=Multiple
Program Version=4.10
Number of Profiles= 7
Profile Names=10-year,25-year,50-year,1pct_min,100-year,1pct_plu,500-year
River Rch & RM=UNT05132 IN WICK,Reach-1         ,937
     128     157     178     149     202     273     258
Boundary for River Rch & Prof#=UNT05132 IN WICK,Reach-1         , 1
Up Type= 0
Dn Type= 3
Dn Slope=0.005
Boundary for River Rch & Prof#=UNT05132 IN WICK,Reach-1         , 2
Up Type= 0
Dn Type= 3
Dn Slope=0.005
Boundary for River Rch & Prof#=UNT05132 IN WICK,Reach-1         , 3
Up Type= 0
Dn Type= 3
Dn Slope=0.005
Boundary for River Rch & Prof#=UNT05132 IN WICK,Reach-1         , 4
Up Type= 0
Dn Type= 3
Dn Slope=0.005
Boundary for River Rch & Prof#=UNT05132 IN WICK,Reach-1         , 5
Up Type= 0
Dn Type= 3
Dn Slope=0.005
Boundary for River Rch & Prof#=UNT05132 IN WICK,Reach-1         , 6
Up Type= 0
Dn Type= 3
Dn Slope=0.005
Boundary for River Rch & Prof#=UNT05132 IN WICK,Reach-1         , 7
Up Type= 0
Dn Type= 3
Dn Slope=0.005
DSS Import GetInterval= 0
DSS Import GetPeak= 0
DSS Import FillOption= 0

--- UNT05132 IN WICK.g01 (geometry) ---

Geom Title=Existing Conditions
Program Version=4.10

River Reach=UNT05132 IN WICK,Reach-1
Reach XY= 14
      3548458.28     10267101.26      3548487.79     10267047.44
      3548506.89     10267007.51      3548513.83     10266967.58
      3548522.51     10266922.44      3548524.25     10266894.66
       3548512.1     10266852.99      3548499.94     10266793.97
        3548493.     10266726.26      3548480.37     10266670.06
      3548495.08     10266363.36      3548501.59       10266198.
      3548575.81      10265946.7       3548676.5     10265771.71

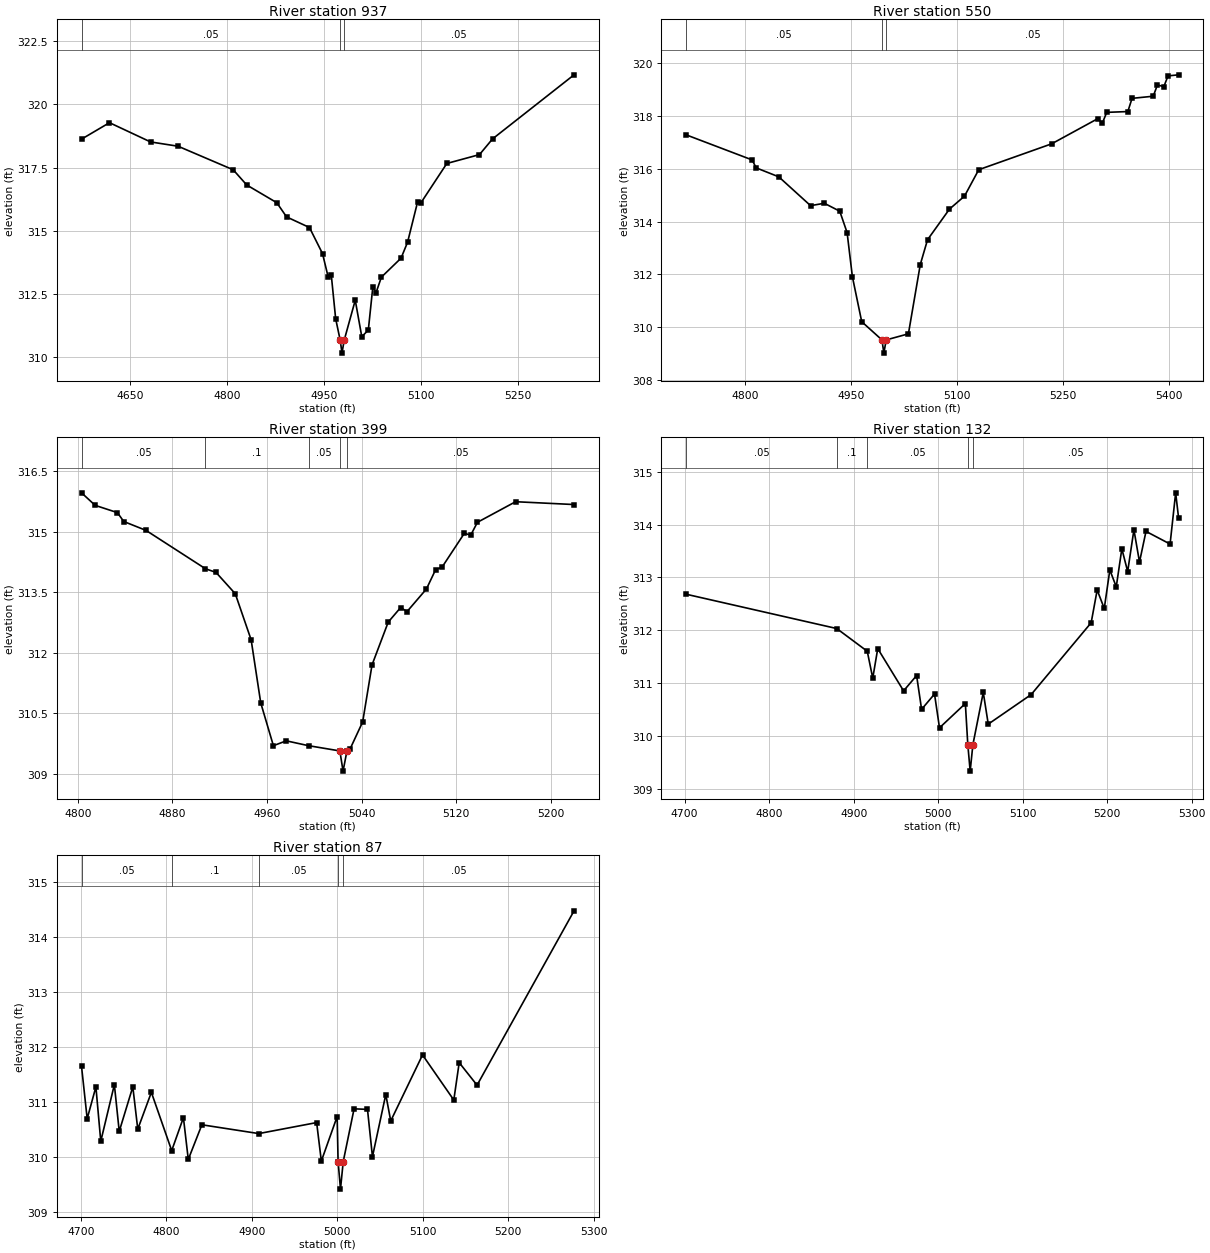
Type RM Length L Ch R = 1 ,937     ,387,387,387
BEGIN DESCRIPTION:
Mapping XS 3d08a231
END DESCRIPTION:
XS GIS Cut Line= 3
      3548807.22     10266907.35      3548611.92     10266690.36
      3548147.52     10266620.91
#Sta/Elev= 30
  4575.2  318.62  4618.4  319.27  4681.9  318.51  4724.5  318.34  4809.7  317.41
  4830.6  316.81  4877.1  316.11  4892.2  315.55  4927.6  315.13  4947.8   314.1
  4956.4  313.19  4961.4  313.24  4968.1  311.53  4975.2  310.67  4977.9  310.17
  4981.2  310.67  4998.4  312.26  5008.5  310.82  5018.6  311.08  5025.6  312.79
  5030.6  312.56  5038.8  313.17  5069.2  313.92  5079.3  314.55  5094.8  316.14
  5099.8   316.1    5140  317.66  5190.5  318.01  5210.7  318.63  5336.7  321.16
#Mann= 3 ,-1 , 0
  4575.2     .05       0  4975.2     .03       0  4981.2     .05       0
Bank Sta=4975.2,4981.2
XS Rating Curve= 0 ,0
Exp/Cntr=0.3,0.1

Type RM Length L Ch R = 1 ,550     ,151,151,151
BEGIN DESCRIPTION:
Mapping XS 110ef0f8
END DESCRIPTION:
XS GIS Cut Line= 4
      3548703.05     10266447.27      3548633.62     10266321.43
      3548299.42     10266230.29      3548127.04     10266346.65
#Sta/Elev= 30
  4715.9  317.28  4809.5  316.33  4815.2  316.03  4847.3  315.69  4892.3   314.6
  4911.8  314.69  4933.7  314.39  4944.1  313.58  4951.6  311.91  4964.8  310.21
  4993.5  309.52  4996.2  309.02  4999.5  309.52    5031  309.75  5047.8  312.37
  5058.1  313.31  5089.2  314.47  5110.5  314.96  5130.7  315.96  5234.1  316.94
  5299.3  317.89    5306  317.73  5312.1  318.13    5342  318.16    5348  318.66
    5378  318.74    5384  319.17    5393   319.1    5399  319.51    5414  319.55
#Mann= 3 ,-1 , 0
  4715.9     .05       0  4993.5     .03       0  4999.5     .05       0
Bank Sta=4993.5,4999.5
XS Rating Curve= 0 ,0
Exp/Cntr=0.3,0.1

Type RM Length L Ch R = 1 ,399     ,267,267,267
BEGIN DESCRIPTION:
Mapping XS 90de3017
END DESCRIPTION:
XS GIS Cut Line= 2
      3548702.77     10266208.91      3548316.23     10266054.07
#Sta/Elev= 30
  4803.1  315.96  4814.6  315.65  4833.4  315.47  4838.8  315.25  4857.6  315.03
  4907.9  314.08  4916.8  313.99  4933.1  313.46  4946.5  312.32  4954.6  310.76
  4965.3   309.7  4976.2  309.82    4995   309.7  5021.5  309.57  5024.2  309.07
  5027.5  309.57    5030  309.61  5040.8  310.29  5048.7   311.7  5062.4  312.76
  5072.9  313.12  5078.3  313.02  5094.7  313.58  5102.5  314.06  5107.9  314.12
  5126.8  314.96  5132.1  314.91  5137.8  315.23  5170.1  315.74  5219.5  315.67
#Mann= 5 ,-1 , 0
  4803.1     .05       0  4907.9      .1       0    4995     .05       0
  5021.5    .035       0  5027.5     .05       0
Bank Sta=5021.5,5027.5
XS Rating Curve= 0 ,0
Exp/Cntr=0.3,0.1

Type RM Length L Ch R = 1 ,132     ,45,45,45
BEGIN DESCRIPTION:
Mapping XS 2448bec0
END DESCRIPTION:
XS GIS Cut Line= 5
      3548867.67     10266037.45      3548684.31     10265932.21
      3548547.59     10265846.49      3548455.36     10265778.13
      3548392.98     10265706.07
#Sta/Elev= 30
  4701.7  312.68    4880  312.03  4916.1   311.6  4922.6  311.09  4928.5  311.65
  4959.1  310.85  4974.5  311.14  4980.4   310.5  4995.7  310.79  5001.6  310.15
  5032.2  310.61  5035.1  309.83  5037.9  309.33  5041.1  309.83  5053.4  310.82
  5059.3  310.22  5110.1  310.78  5181.1  312.14  5188.2  312.76  5196.6  312.41
  5203.2  313.14  5210.8  312.82  5217.4  313.54  5224.3  313.11  5231.7   313.9
  5238.3  313.29    5246  313.87  5274.5  313.63  5281.1   314.6  5284.6  314.12
#Mann= 5 ,-1 , 0
  4701.7     .05       0    4880      .1       0  4916.1     .05       0
  5035.1     .04       0  5041.1     .05       0
Bank Sta=5035.1,5041.1
XS Rating Curve= 0 ,0
Exp/Cntr=0.3,0.1

Type RM Length L Ch R = 1 ,87      ,0,0,0
BEGIN DESCRIPTION:
UNT05132 IN WICK 1.0
END DESCRIPTION:
XS GIS Cut Line= 6
      3548897.01     10265987.56      3548751.58     10265905.08
      3548632.98     10265847.35      3548533.48     10265788.98
      3548487.91     10265730.39       3548443.3     10265654.97
#Sta/Elev= 30
  4700.9  311.65  4707.5   310.7  4717.7  311.28  4723.4  310.29  4739.3  311.32
    4745  310.47  4760.9  311.28  4766.7  310.51  4782.6  311.18  4806.4  310.12
  4820.1  310.72  4825.8  309.96  4841.7  310.59  4908.3  310.43    4976  310.63
  4981.5  309.93    5000  310.74  5001.1  309.92  5003.9  309.42  5007.1  309.92
  5019.8  310.88  5035.5  310.87  5041.3  310.01  5056.9  311.14  5062.7  310.66
  5099.9  311.86  5136.5  311.04  5142.8  311.72  5163.7  311.31  5277.2  314.48
#Mann= 5 ,-1 , 0
  4700.9     .05       0  4806.4      .1       0  4908.3     .05       0
  5001.1     .04       0  5007.1     .05       0
Bank Sta=5001.1,5007.1
XS Rating Curve= 0 ,0
Exp/Cntr=0.3,0.1

Chan Stop Cuts=-1
Use User Specified Reach Order=0
Composite Channel Slope=5