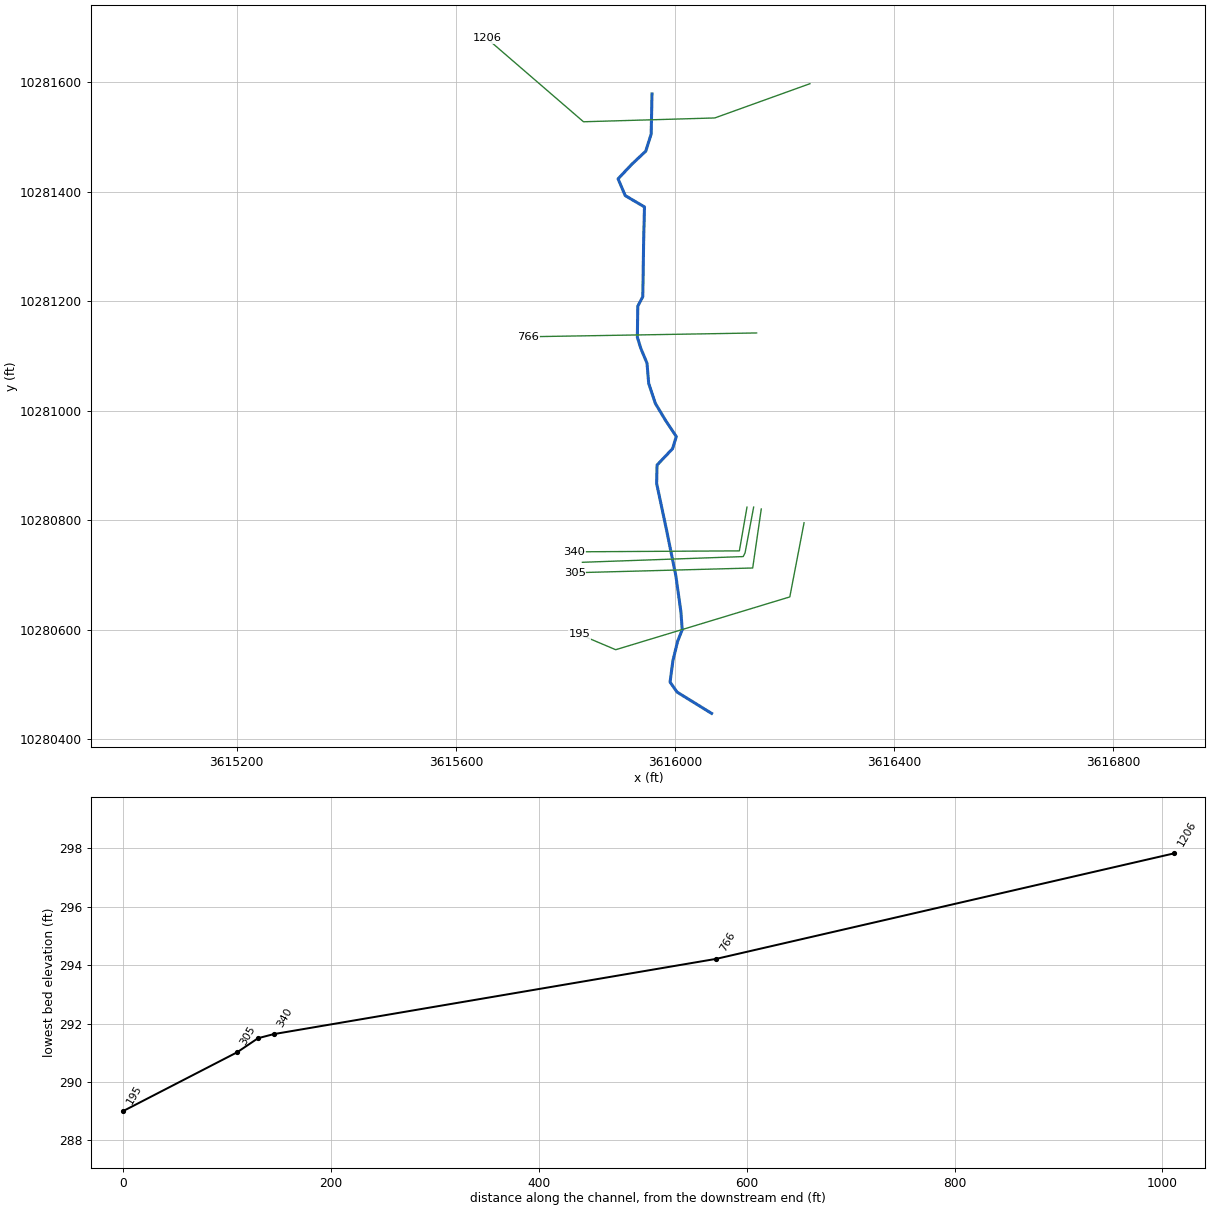
--- UNT102 IN WICK.prj (project) ---

Proj Title=UNT102 IN WICK Base Level Engineering
Current Plan=p01
Default Exp/Contr=0.3,0.1
English Units
Geom File=g01
Flow File=f01
Plan File=p01
BEGIN DESCRIPTION:
UNT102 IN WICK
END DESCRIPTION:

--- UNT102 IN WICK.p01 (plan) ---

Plan Title=Multiple Run
Short Identifier=Multiple
Geom File=g01
Flow File=f01
Subcritical Flow
K Sum by GR= 0
Std Step Tol= 0.01
Critical Tol= 0.01
Num of Std Step Trials= 20
Max Error Tol= 0.3
Flow Tol Ratio= 0.001
Split Flow NTrial= 30
Split Flow Tol= 0.02
Split Flow Ratio= 0.02
Log Output Level= 0
Friction Slope Method= 1
Unsteady Friction Slope Method= 2
Unsteady Bridges Friction Slope Method= 1
Parabolic Critical Depth
Global Vel Dist=  1 , 1 , 1
Global Log Level= 0
CheckData=True
Encroach Param= -1, 0, 0, 0
BEGIN DESCRIPTION:
Multiple Run
END DESCRIPTION:

--- UNT102 IN WICK.f01 (steady flow) ---

Flow Title=Multiple
Number of Profiles=7
Profile Names=10-year,25-year,50-year,1pct_min,100-year,1pct_plu,500-year
River Rch & RM= UNT102 IN WICK,Reach-1,1206
     102     121     134     111     150     202     184
Boundary for River Rch & Prof#=UNT102 IN WICK,Reach-1,1
Up Type=0
Dn Type=3
Dn Slope=0.005
Boundary for River Rch & Prof#=UNT102 IN WICK,Reach-1,2
Up Type=0
Dn Type=3
Dn Slope=0.005
Boundary for River Rch & Prof#=UNT102 IN WICK,Reach-1,3
Up Type=0
Dn Type=3
Dn Slope=0.005
Boundary for River Rch & Prof#=UNT102 IN WICK,Reach-1,4
Up Type=0
Dn Type=3
Dn Slope=0.005
Boundary for River Rch & Prof#=UNT102 IN WICK,Reach-1,5
Up Type=0
Dn Type=3
Dn Slope=0.005
Boundary for River Rch & Prof#=UNT102 IN WICK,Reach-1,6
Up Type=0
Dn Type=3
Dn Slope=0.005
Boundary for River Rch & Prof#=UNT102 IN WICK,Reach-1,7
Up Type=0
Dn Type=3
Dn Slope=0.005

--- UNT102 IN WICK.g01 (geometry) ---

Geom Title=Existing Conditions

River Reach=UNT102 IN WICK,Reach-1
Reach XY= 29
      3615957.97     10281578.02      3615956.46     10281504.97
      3615946.52     10281473.61      3615921.29     10281449.91
      3615896.05     10281423.14      3615909.05     10281392.55
      3615944.23     10281371.90      3615942.70     10281309.19
      3615941.17     10281208.25      3615931.99     10281190.66
      3615931.23     10281134.07      3615937.35     10281114.19
      3615948.82     10281086.66      3615951.88     10281049.95
      3615964.11     10281013.24      3615982.47     10280982.65
      3616002.35     10280952.83      3615995.47     10280930.65
      3615967.17     10280900.82      3615966.41     10280867.18
      3615984.00     10280784.58      3616001.58     10280698.17
      3616010.76     10280632.40      3616013.06     10280600.28
      3616004.64     10280578.87      3615996.23     10280544.46
      3615990.88     10280504.69      3616003.88     10280486.34
      3616066.64     10280447.63

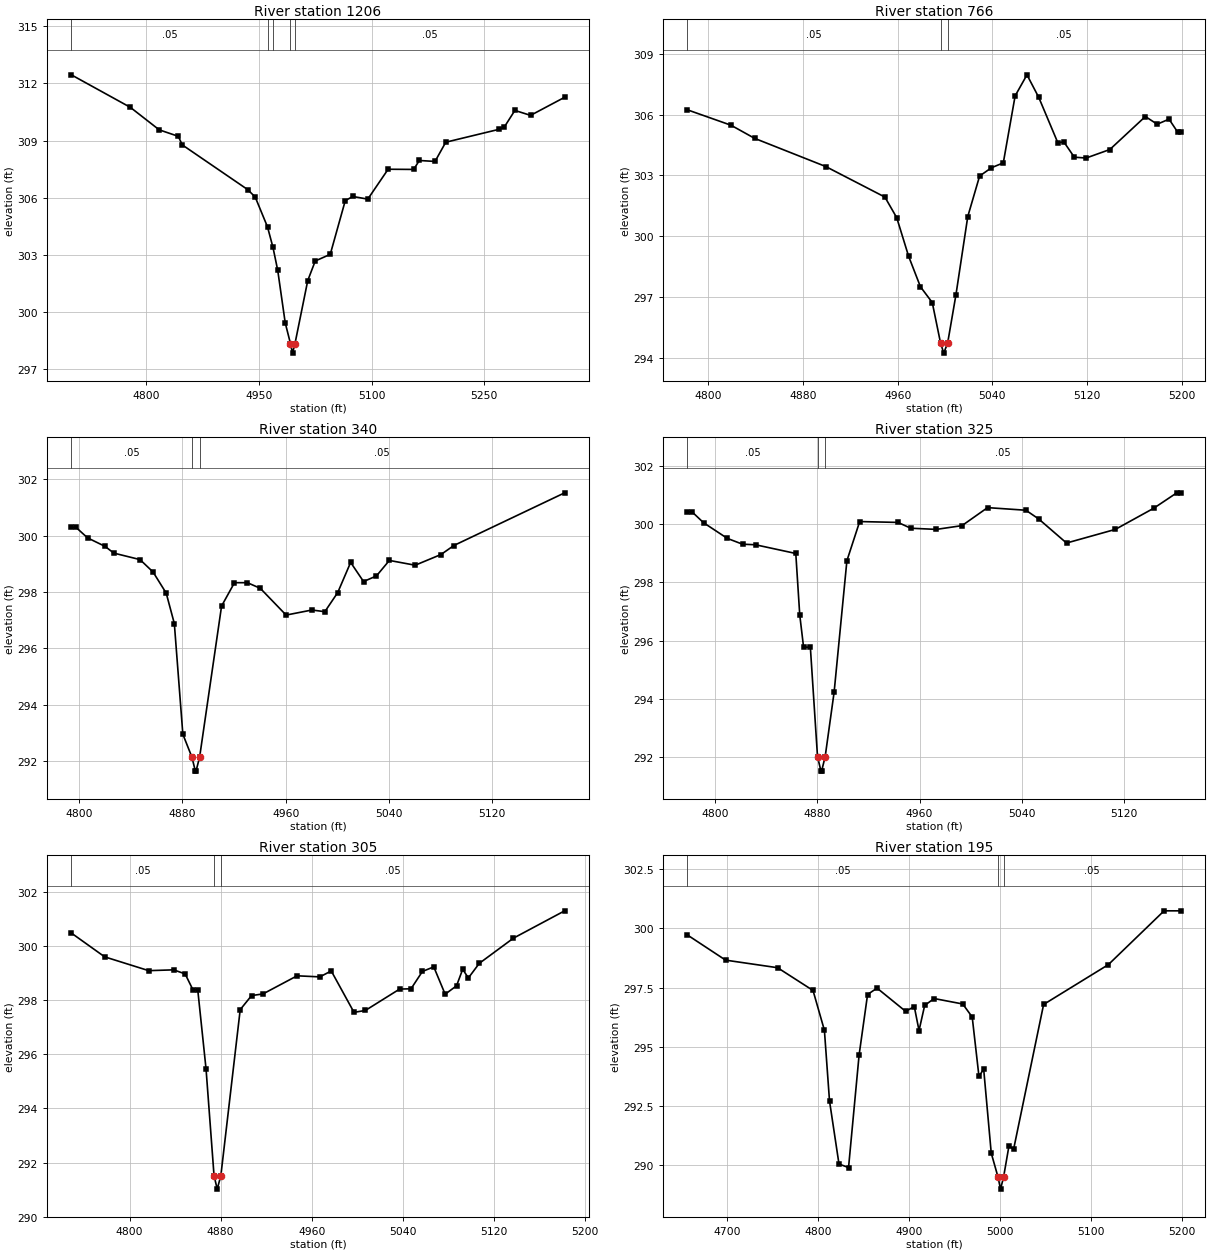
Type RM Length L Ch R = 1,1206,440,440,440
BEGIN DESCRIPTION:
UNT102 IN WICK 3.0
END DESCRIPTION:
XS GIS Cut Line= 4
      3616246.14     10281596.74      3616072.51     10281534.24
      3615832.92     10281527.29      3615656.45     10281679.54
#Sta/Elev= 30
  4699.9  312.45  4778.6  310.74  4817.0  309.56  4842.4  309.22  4847.7  308.77
  4934.9  306.42  4944.9  306.03  4961.3  304.46  4968.6  303.38  4974.9  302.18
  4984.9  299.42  4991.9  298.33  4994.6  297.83  4997.9  298.33  5014.9  301.64
  5024.9  302.67  5044.9  303.02  5064.9  305.84  5074.9  306.06  5094.9  305.92
  5122.0  307.49  5156.0  307.48  5163.6  307.95  5184.5  307.90  5198.8  308.91
  5270.1  309.59  5276.7  309.70  5290.9  310.58  5311.8  310.32  5357.2  311.27
#Mann=5,-1,0
  4699.9    0.05       0  4961.3    0.12       0  4968.6    0.05       0
  4991.9    0.03       0  4997.9    0.05       0
Bank Sta=4991.9,4997.9
Exp/Cntr=0.3,0.1

Type RM Length L Ch R = 1,766,426,426,426
BEGIN DESCRIPTION:
UNT102 IN WICK 2.0
END DESCRIPTION:
XS GIS Cut Line= 2
      3616148.85     10281141.87      3615732.21     10281134.93
#Sta/Elev= 30
  4782.4  306.24  4819.2  305.48  4839.2  304.83  4899.2  303.44  4949.2  301.93
  4959.2  300.91  4969.2  299.01  4979.2  297.50  4989.2  296.72  4996.2  294.72
  4998.9  294.22  5002.2  294.72  5009.2  297.10  5019.2  300.97  5029.2  302.97
  5039.2  303.38  5049.2  303.62  5059.2  306.93  5069.2  307.97  5079.2  306.85
  5095.3  304.61  5100.3  304.66  5109.2  303.90  5119.2  303.86  5139.2  304.28
  5169.2  305.91  5179.2  305.53  5189.2  305.78  5196.6  305.13  5199.1  305.13
#Mann=3,-1,0
  4782.4    0.05       0  4996.2    0.03       0  5002.2    0.05       0
Bank Sta=4996.2,5002.2
Exp/Cntr=0.3,0.1

Type RM Length L Ch R = 1,340,15,15,15
BEGIN DESCRIPTION:
Mapping XS 4c8fa1fc
END DESCRIPTION:
XS GIS Cut Line= 3
      3616131.30     10280824.04      3616117.41     10280744.19
      3615816.27     10280742.46
#Sta/Elev= 30
  4793.9  300.29  4797.6  300.29  4806.5  299.92  4820.0  299.62  4826.8  299.38
  4847.1  299.15  4857.2  298.71  4867.4  297.96  4873.7  296.88  4880.3  292.95
  4887.3  292.14  4890.0  291.64  4890.5  291.64  4893.3  292.14  4910.3  297.50
  4920.3  298.33  4930.3  298.33  4940.3  298.13  4960.3  297.18  4980.3  297.36
  4990.3  297.30  5000.3  297.98  5010.3  299.05  5020.3  298.37  5030.3  298.57
  5040.3  299.12  5060.3  298.95  5080.3  299.33  5090.3  299.65  5176.1  301.52
#Mann=3,-1,0
  4793.9    0.05       0  4887.3    0.03       0  4893.3    0.05       0
Bank Sta=4887.3,4893.3
Exp/Cntr=0.3,0.1

Type RM Length L Ch R = 1,325,20,20,20
BEGIN DESCRIPTION:
Mapping XS 8f8591af
END DESCRIPTION:
XS GIS Cut Line= 4
      3616143.45     10280824.03      3616127.83     10280740.72
      3616124.36     10280733.77      3615830.97     10280723.36
#Sta/Elev= 29
  4778.3  300.43  4782.0  300.43  4790.9  300.06  4809.5  299.52  4821.4  299.32
  4831.6  299.30  4863.1  299.00  4866.2  296.88  4869.2  295.77  4874.5  295.77
  4880.1  292.00  4882.8  291.50  4883.3  291.50  4886.1  292.00  4893.1  294.22
  4903.1  298.75  4913.1  300.10  4943.1  300.07  4953.1  299.87  4973.1  299.83
  4993.2  299.96  5013.2  300.58  5043.2  300.49  5053.2  300.19  5075.0  299.36
  5113.2  299.83  5143.3  300.56  5161.3  301.09  5164.4  301.09
#Mann=3,-1,0
  4778.3    0.05       0  4880.1    0.03       0  4886.1    0.05       0
Bank Sta=4880.1,4886.1
Exp/Cntr=0.3,0.1

Type RM Length L Ch R = 1,305,110,110,110
BEGIN DESCRIPTION:
Mapping XS c9843263
END DESCRIPTION:
XS GIS Cut Line= 3
      3616157.35     10280820.59      3616141.72     10280712.94
      3615817.12     10280704.26
#Sta/Elev= 30
  4748.8  300.48  4778.1  299.60  4816.8  299.09  4838.7  299.12  4848.8  298.97
  4855.7  298.38  4859.9  298.38  4867.2  295.45  4874.2  291.52  4877.0  291.02
  4880.2  291.52  4897.2  297.65  4907.2  298.17  4917.2  298.23  4947.2  298.90
  4967.2  298.86  4977.2  299.08  4997.2  297.55  5007.2  297.62  5037.3  298.41
  5047.3  298.42  5057.3  299.06  5067.3  299.23  5077.3  298.22  5087.3  298.53
  5092.7  299.14  5097.7  298.82  5107.3  299.36  5137.3  300.29  5182.3  301.30
#Mann=3,-1,0
  4748.8    0.05       0  4874.2    0.03       0  4880.2    0.05       0
Bank Sta=4874.2,4880.2
Exp/Cntr=0.3,0.1

Type RM Length L Ch R = 1,195,0,0,0
BEGIN DESCRIPTION:
UNT102 IN WICK 1.0
END DESCRIPTION:
XS GIS Cut Line= 4
      3616235.47     10280795.55      3616209.43     10280660.16
      3615891.72     10280563.81      3615825.57     10280591.80
#Sta/Elev= 30
  4656.9  299.72  4698.8  298.66  4755.9  298.34  4794.8  297.38  4807.3  295.70
  4812.9  292.72  4823.3  290.06  4833.8  289.91  4845.4  294.66  4854.7  297.21
  4865.1  297.48  4896.5  296.50  4906.0  296.70  4911.2  295.69  4917.4  296.75
  4927.8  297.04  4959.2  296.81  4969.6  296.26  4977.0  293.76  4982.2  294.06
  4990.5  290.52  4998.0  289.50  5000.7  289.00  5004.0  289.50  5009.9  290.81
  5015.1  290.69  5048.0  296.79  5119.1  298.47  5180.3  300.74  5198.6  300.74
#Mann=3,-1,0
  4656.9    0.05       0  4998.0    0.03       0  5004.0    0.05       0
Bank Sta=4998,5004
Exp/Cntr=0.3,0.1

Chan Stop Cuts=-1