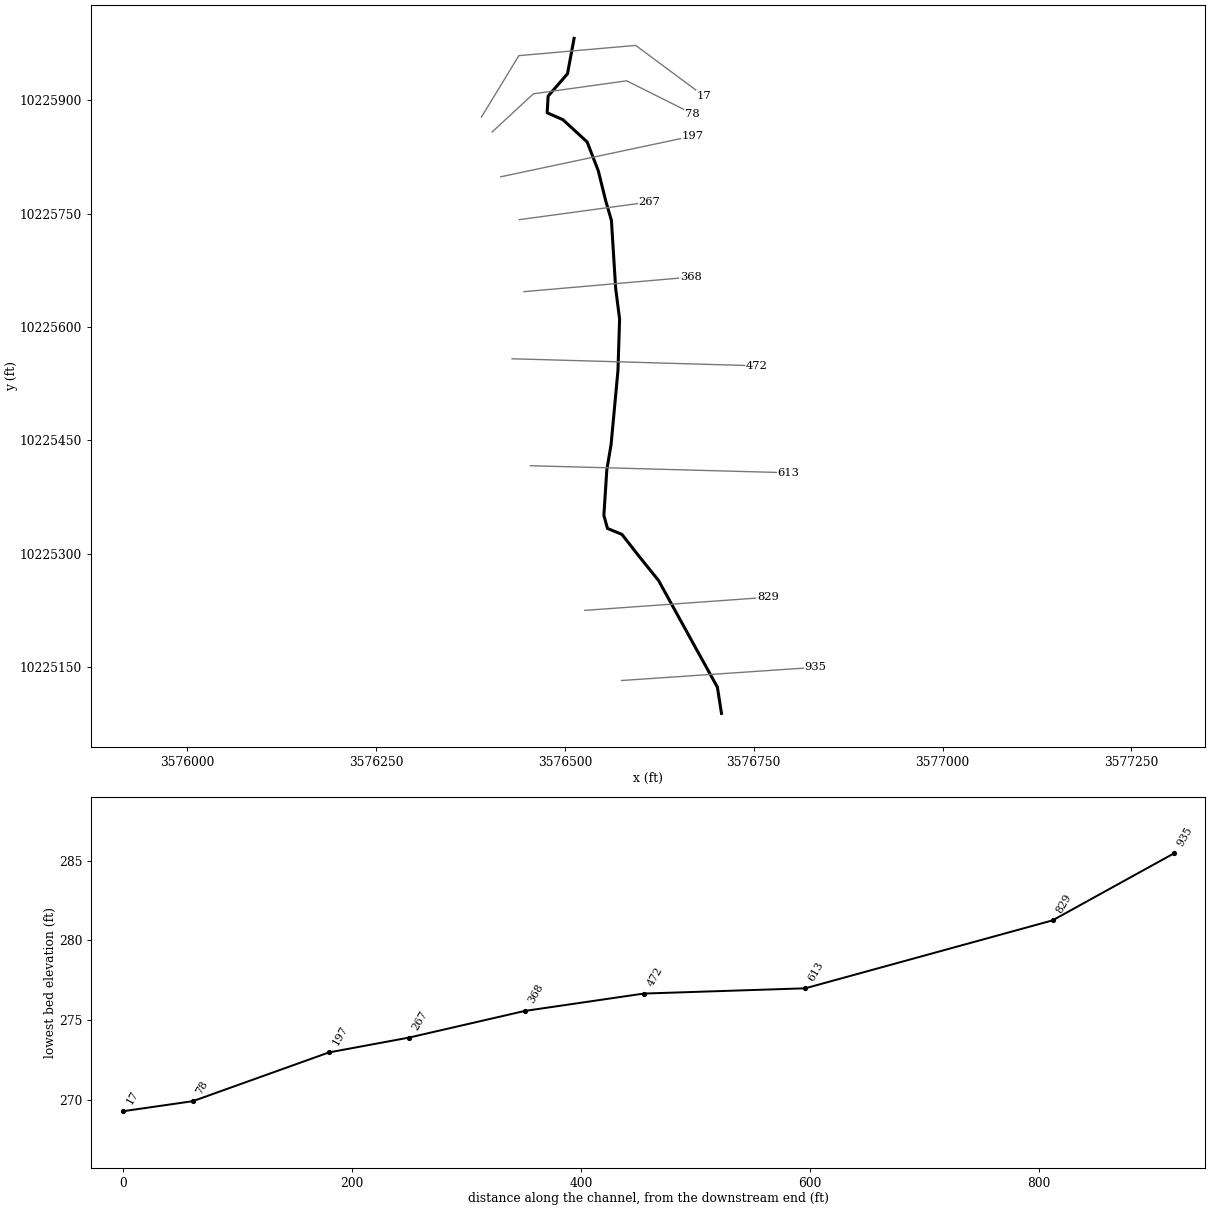
--- UNT114 IN WICK.prj (project) ---

Proj Title=UNT114 IN WICK Base Level Engineering
Current Plan=p01
Default Exp/Contr=0.3,0.1
English Units
Geom File=g01
Flow File=f01
Plan File=p01
Y Axis Title=Elevation
X Axis Title(PF)=Main Channel Distance
X Axis Title(XS)=Station
BEGIN DESCRIPTION:
UNT114 IN WICK
END DESCRIPTION:
DSS Export Rating Curves= 0
DSS Export Rating Curve Sorted= 0
DSS Export Volume Flow Curves= 0
DXF OffsetX= 0
DXF OffsetY= 0
DXF ScaleX= 1
DXF ScaleY= 10

--- UNT114 IN WICK.p01 (plan) ---

Plan Title=Multiple Run
Short Identifier=Multiple
Geom File=g01
Flow File=f01
Subcritical Flow
K Sum by GR= 0
Std Step Tol= 0.01
Critical Tol= 0.01
Num of Std Step Trials= 20
Max Error Tol= 0.3
Flow Tol Ratio= 0.001
Split Flow NTrial= 30
Split Flow Tol= 0.02
Split Flow Ratio= 0.02
Log Output Level= 0
Friction Slope Method= 1
Unsteady Friction Slope Method= 2
Unsteady Bridges Friction Slope Method= 1
Parabolic Critical Depth
Global Vel Dist=  1 , 1 , 1
Global Log Level= 0
CheckData=True
Encroach Param= -1, 0, 0, 0
BEGIN DESCRIPTION:
Multiple Run
END DESCRIPTION:

--- UNT114 IN WICK.f01 (steady flow) ---

Flow Title=Multiple
Program Version=4.10
Number of Profiles= 7
Profile Names=10-year,25-year,50-year,1pct_min,100-year,1pct_plu,500-year
River Rch & RM=UNT114 IN WICK,Reach-1         ,935
      66      76      83      68      92     124     110
Boundary for River Rch & Prof#=UNT114 IN WICK,Reach-1         , 1
Up Type= 0
Dn Type= 3
Dn Slope=0.018
Boundary for River Rch & Prof#=UNT114 IN WICK,Reach-1         , 2
Up Type= 0
Dn Type= 3
Dn Slope=0.018
Boundary for River Rch & Prof#=UNT114 IN WICK,Reach-1         , 3
Up Type= 0
Dn Type= 3
Dn Slope=0.018
Boundary for River Rch & Prof#=UNT114 IN WICK,Reach-1         , 4
Up Type= 0
Dn Type= 3
Dn Slope=0.018
Boundary for River Rch & Prof#=UNT114 IN WICK,Reach-1         , 5
Up Type= 0
Dn Type= 3
Dn Slope=0.018
Boundary for River Rch & Prof#=UNT114 IN WICK,Reach-1         , 6
Up Type= 0
Dn Type= 3
Dn Slope=0.018
Boundary for River Rch & Prof#=UNT114 IN WICK,Reach-1         , 7
Up Type= 0
Dn Type= 3
Dn Slope=0.018
DSS Import GetInterval= 0
DSS Import GetPeak= 0
DSS Import FillOption= 0

--- UNT114 IN WICK.g01 (geometry) ---

Geom Title=Existing Conditions
Program Version=4.10

River Reach=UNT114 IN WICK  ,Reach-1
Reach XY= 22
      3576707.24     10225088.44      3576701.81     10225123.16
       3576673.6     10225174.16        3576624.     10225264.25
      3576598.83      10225295.5      3576575.39     10225325.45
       3576556.3     10225333.26      3576551.52     10225350.62
      3576555.43     10225410.95      3576561.07     10225444.37
      3576570.18     10225542.46      3576572.35      10225610.6
      3576567.15     10225650.97       3576561.5     10225741.24
      3576554.12     10225766.42      3576544.14     10225806.78
      3576529.39     10225844.98      3576497.27     10225874.49
      3576476.43     10225883.61      3576477.74     10225905.74
      3576503.34     10225935.25       3576512.1     10225982.18

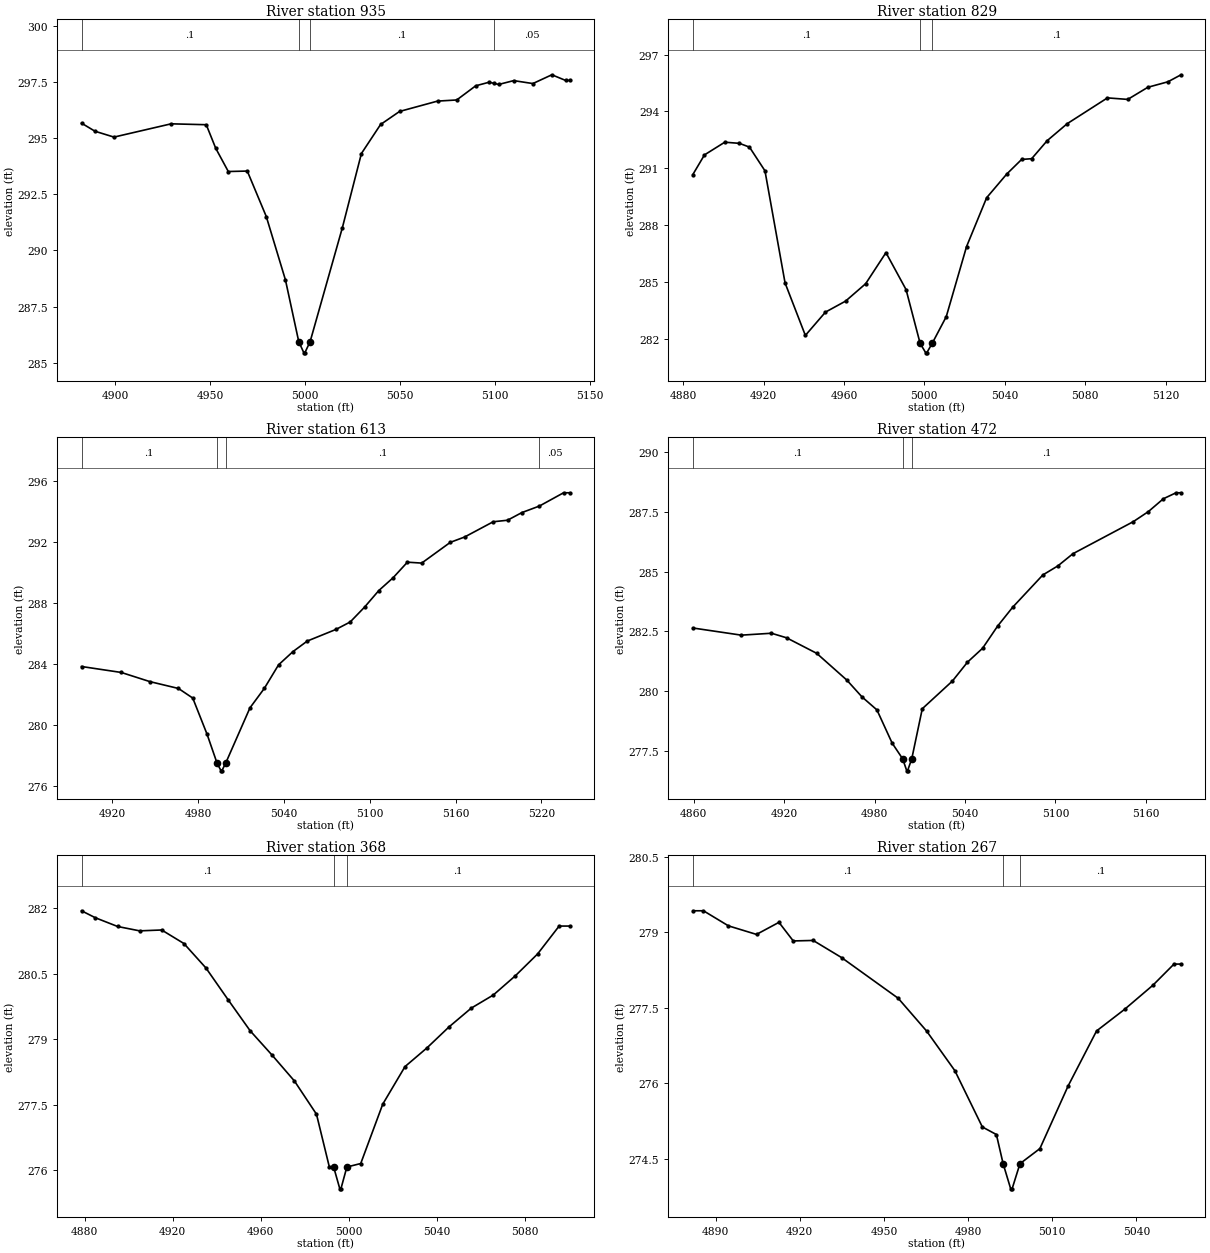
Type RM Length L Ch R = 1 ,935     ,106,106,106
BEGIN DESCRIPTION:
UNT114 IN WICK 8.0
END DESCRIPTION:
XS GIS Cut Line= 2
        3576575.     10225131.96      3576831.51     10225149.38
#Sta/Elev= 29
  4882.2  295.66  4889.3   295.3  4899.3  295.04  4929.4  295.63  4947.9  295.59
  4952.9  294.54  4959.5  293.51  4969.5  293.53  4979.5  291.51  4989.6  288.69
  4996.6  285.95  4999.3  285.45  4999.8  285.45  5002.6  285.95  5019.6  291.02
  5029.6  294.31  5039.7   295.6  5049.7  296.18  5069.7  296.64  5079.8  296.69
  5089.8  297.32  5096.9  297.48  5099.3  297.43  5101.9  297.38  5109.8  297.55
  5119.9  297.42  5129.9  297.81  5137.1  297.56  5139.3  297.56
#Mann= 4 ,-1 , 0
  4882.2      .1       0  4996.6     .07       0  5002.6      .1       0
  5099.3     .05       0
Bank Sta=4996.6,5002.6
XS Rating Curve= 0 ,0
Exp/Cntr=0.3,0.1

Type RM Length L Ch R = 1 ,829     ,216,216,216
BEGIN DESCRIPTION:
Mapping XS d7789f08
END DESCRIPTION:
XS GIS Cut Line= 2
      3576526.28     10225224.82      3576768.56     10225242.13
#Sta/Elev= 30
  4884.8  290.66  4890.6   291.7  4900.7  292.37    4908  292.31    4913  292.11
  4920.7  290.86  4930.7  284.94  4940.8  282.17  4950.8   283.4  4960.8  283.98
  4970.8   284.9  4980.9  286.54  4990.9  284.59  4997.9  281.75  5000.7  281.25
  5001.2  281.25  5003.9  281.75  5010.9  283.16    5021  286.86    5031  289.44
    5041  290.69  5048.4  291.46  5053.4   291.5  5061.1  292.45  5071.1  293.35
  5091.1  294.71  5101.2  294.63  5111.2  295.27  5121.2  295.56  5127.7  295.93
#Mann= 3 ,-1 , 0
  4884.8      .1       0  4997.9     .07       0  5003.9      .1       0
Bank Sta=4997.9,5003.9
XS Rating Curve= 0 ,0
Exp/Cntr=0.3,0.1

Type RM Length L Ch R = 1 ,613     ,141,141,141
BEGIN DESCRIPTION:
Mapping XS d2b6a47b
END DESCRIPTION:
XS GIS Cut Line= 2
      3576454.31     10225416.34      3576795.58     10225407.05
#Sta/Elev= 30
  4898.4  283.83  4926.2  283.44  4946.2  282.84  4966.2  282.39  4976.2  281.76
  4986.2  279.39  4993.2  277.49    4996  276.99  4996.5  276.99  4999.2  277.49
  5016.2  281.12  5026.2  282.39  5036.2  283.94  5046.3  284.81  5056.3   285.5
  5076.3  286.26  5086.3  286.75  5096.3  287.72  5106.3  288.81  5116.3  289.65
  5126.3  290.67  5136.3  290.61  5156.3  291.97  5166.3  292.32  5186.3  293.32
  5196.3  293.42  5206.3  293.92  5218.6  294.35  5235.5  295.22  5239.8  295.22
#Mann= 4 ,-1 , 0
  4898.4      .1       0  4993.2     .07       0  4999.2      .1       0
  5218.6     .05       0
Bank Sta=4993.2,4999.2
XS Rating Curve= 0 ,0
Exp/Cntr=0.3,0.1

Type RM Length L Ch R = 1 ,472     ,104,104,104
BEGIN DESCRIPTION:
Mapping XS f38948ad
END DESCRIPTION:
XS GIS Cut Line= 2
      3576429.91     10225557.94      3576753.77     10225548.66
#Sta/Elev= 27
  4859.3  282.64  4891.5  282.34  4911.5  282.42  4921.5  282.23  4941.5  281.58
  4961.5  280.46  4971.5  279.76  4981.5  279.21  4991.6  277.82  4998.6  277.16
  5001.3  276.66  5001.8  276.66  5004.6  277.16  5011.6  279.26  5031.6  280.42
  5041.6  281.21  5051.6  281.79  5061.6  282.72  5071.6  283.51  5091.6  284.86
  5101.6  285.24  5111.6  285.75  5151.6  287.09  5161.6  287.51  5171.6  288.05
    5180   288.3  5183.3   288.3
#Mann= 3 ,-1 , 0
  4859.3      .1       0  4998.6     .07       0  5004.6      .1       0
Bank Sta=4998.6,5004.6
XS Rating Curve= 0 ,0
Exp/Cntr=0.3,0.1

Type RM Length L Ch R = 1 ,368     ,101,101,101
BEGIN DESCRIPTION:
Mapping XS 751dd9d3
END DESCRIPTION:
XS GIS Cut Line= 2
      3576445.81     10225646.79      3576666.67     10225666.07
#Sta/Elev= 28
  4878.6  281.94  4884.9  281.78    4895  281.58    4905  281.48    4915   281.5
  4925.1  281.19  4935.1  280.63  4945.2   279.9  4955.2  279.19  4965.2  278.63
  4975.3  278.04  4985.3  277.28  4991.1  276.08  4993.1  276.07  4995.9  275.57
  4996.4  275.57  4999.1  276.07  5005.4  276.15  5015.4  277.51  5025.5  278.37
  5035.5   278.8  5045.5  279.28  5055.6  279.71  5065.6  280.01  5075.6  280.45
  5085.7  280.95  5095.5  281.59  5100.3  281.59
#Mann= 3 ,-1 , 0
  4878.6      .1       0  4993.1     .07       0  4999.1      .1       0
Bank Sta=4993.1,4999.1
XS Rating Curve= 0 ,0
Exp/Cntr=0.3,0.1

Type RM Length L Ch R = 1 ,267     ,70,70,70
BEGIN DESCRIPTION:
Mapping XS b9c47e4c
END DESCRIPTION:
XS GIS Cut Line= 2
      3576439.56     10225742.11      3576611.98     10225765.55
#Sta/Elev= 24
  4881.9  279.43  4885.7  279.43  4894.6  279.13  4904.6  278.96  4912.6   279.2
  4917.7  278.83  4924.8  278.84  4934.9   278.5  4955.1  277.69  4965.2  277.04
  4975.3  276.25  4985.1  275.13  4990.1  274.98  4992.5   274.4  4995.2   273.9
  4995.7   273.9  4998.5   274.4  5005.6   274.7  5015.7  275.95  5025.8  277.04
  5035.8  277.47  5045.9  277.95  5053.4  278.37  5055.9  278.37
#Mann= 3 ,-1 , 0
  4881.9      .1       0  4992.5     .07       0  4998.5      .1       0
Bank Sta=4992.5,4998.5
XS Rating Curve= 0 ,0
Exp/Cntr=0.3,0.1

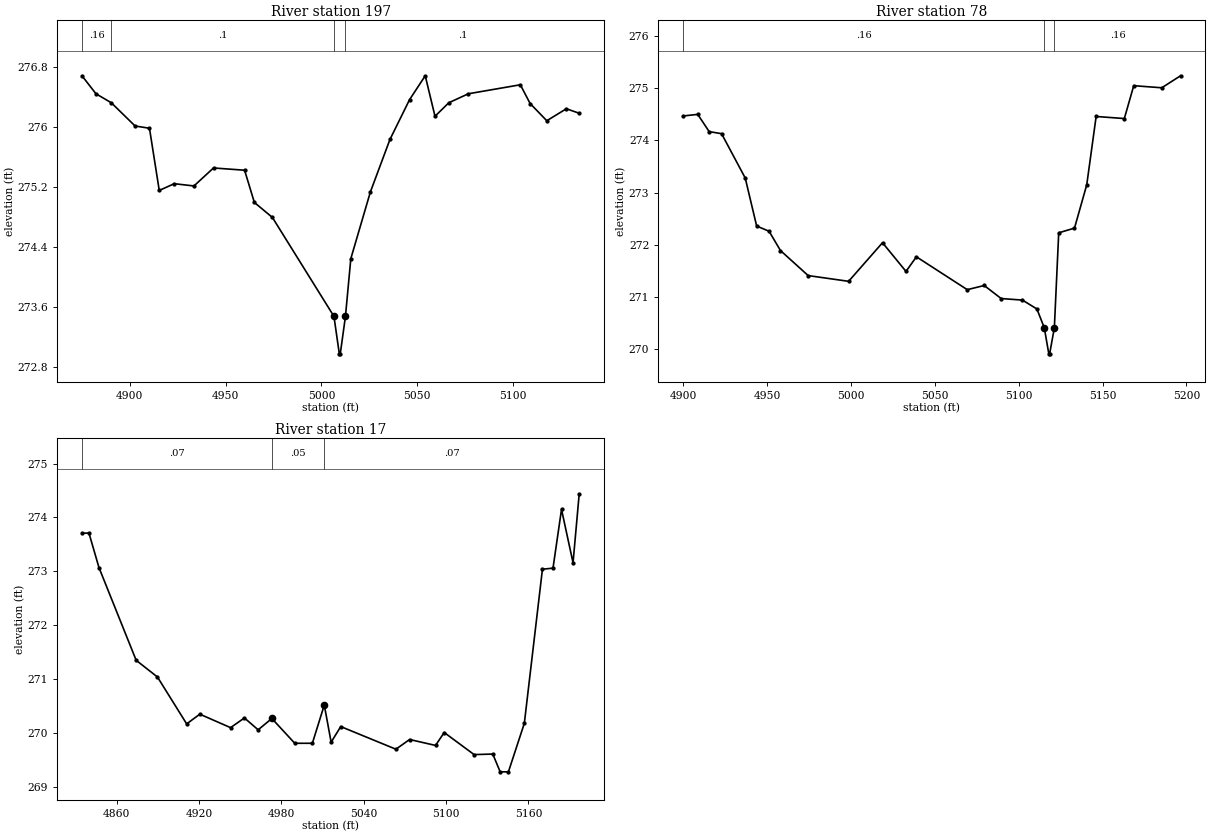
Type RM Length L Ch R = 1 ,197     ,119,119,119
BEGIN DESCRIPTION:
Mapping XS 5ba4e240
END DESCRIPTION:
XS GIS Cut Line= 2
      3576415.01     10225798.85      3576668.66     10225852.69
#Sta/Elev= 29
  4875.1  276.68  4882.4  276.44  4890.4  276.32  4902.8  276.01  4910.3  275.98
  4915.4  275.15  4923.2  275.24  4933.5  275.21  4943.7  275.45  4959.9  275.42
    4965  274.99  4974.4  274.79  5006.5  273.47  5009.3  272.97  5009.8  272.97
  5012.5  273.47  5015.3  274.24  5025.5  275.13  5035.7  275.83  5045.9  276.36
  5054.1  276.68  5059.2  276.14  5066.4  276.32  5076.6  276.44  5103.7  276.56
  5108.8  276.31  5117.5  276.08  5127.7  276.24  5134.4  276.18
#Mann= 4 ,-1 , 0
  4875.1     .16       0  4890.4      .1       0  5006.5     .07       0
  5012.5      .1       0
Bank Sta=5006.5,5012.5
XS Rating Curve= 0 ,0
Exp/Cntr=0.3,0.1

Type RM Length L Ch R = 1 ,78      ,61,61,61
BEGIN DESCRIPTION:
Mapping XS fde1f15e
END DESCRIPTION:
XS GIS Cut Line= 4
      3576403.58     10225858.25      3576458.25     10225908.75
      3576581.69     10225925.94      3576668.67     10225882.45
#Sta/Elev= 30
  4900.2  274.47  4908.8   274.5  4915.6  274.17    4923  274.13  4937.1  273.28
  4943.9  272.36  4951.3  272.26  4958.1  271.89  4974.6  271.41  4998.7   271.3
  5018.9  272.04  5032.9  271.49  5039.1  271.77  5069.4  271.14  5079.5  271.22
  5089.6  270.97  5102.3  270.94  5110.9  270.77  5115.3  270.41    5118  269.91
  5118.5  269.91  5121.3  270.41  5123.9  272.23  5133.3  272.32  5140.6  273.15
  5146.2  274.46    5163  274.42  5168.6  275.05  5185.3  275.01  5196.5  275.24
#Mann= 3 ,-1 , 0
  4900.2     .16       0  5115.3     .07       0  5121.3     .16       0
Bank Sta=5115.3,5121.3
XS Rating Curve= 0 ,0
Exp/Cntr=0.3,0.1

Type RM Length L Ch R = 1 ,17      ,0,0,0
BEGIN DESCRIPTION:
UNT114 IN WICK 1.0
END DESCRIPTION:
XS GIS Cut Line= 4
      3576389.49     10225878.01      3576438.98     10225959.27
      3576593.67     10225972.81      3576683.62     10225906.13
#Sta/Elev= 30
  4834.6  273.71  4839.7  273.71    4847  273.07  4874.1  271.35  4889.6  271.04
  4910.9  270.17  4920.5  270.35  4942.9   270.1    4953  270.28    4963  270.06
    4973  270.27 4989.69  269.81 5002.52  269.81  5011.2  270.52  5016.2  269.83
  5023.2  270.12  5063.4   269.7  5073.4  269.88  5092.3  269.77  5098.6  270.01
  5120.4   269.6    5134  269.61  5139.4  269.28  5145.4  269.28    5157  270.18
  5170.2  273.04  5177.9  273.06  5184.1  274.15  5192.5  273.16    5197  274.44
#Mann= 3 , 0 , 0
  4834.6     .07       0    4973     .05       0  5011.2     .07       0
Bank Sta=4973,5011.2
XS Rating Curve= 0 ,0
Exp/Cntr=0.3,0.1

Chan Stop Cuts=-1
Use User Specified Reach Order=0
Composite Channel Slope=5