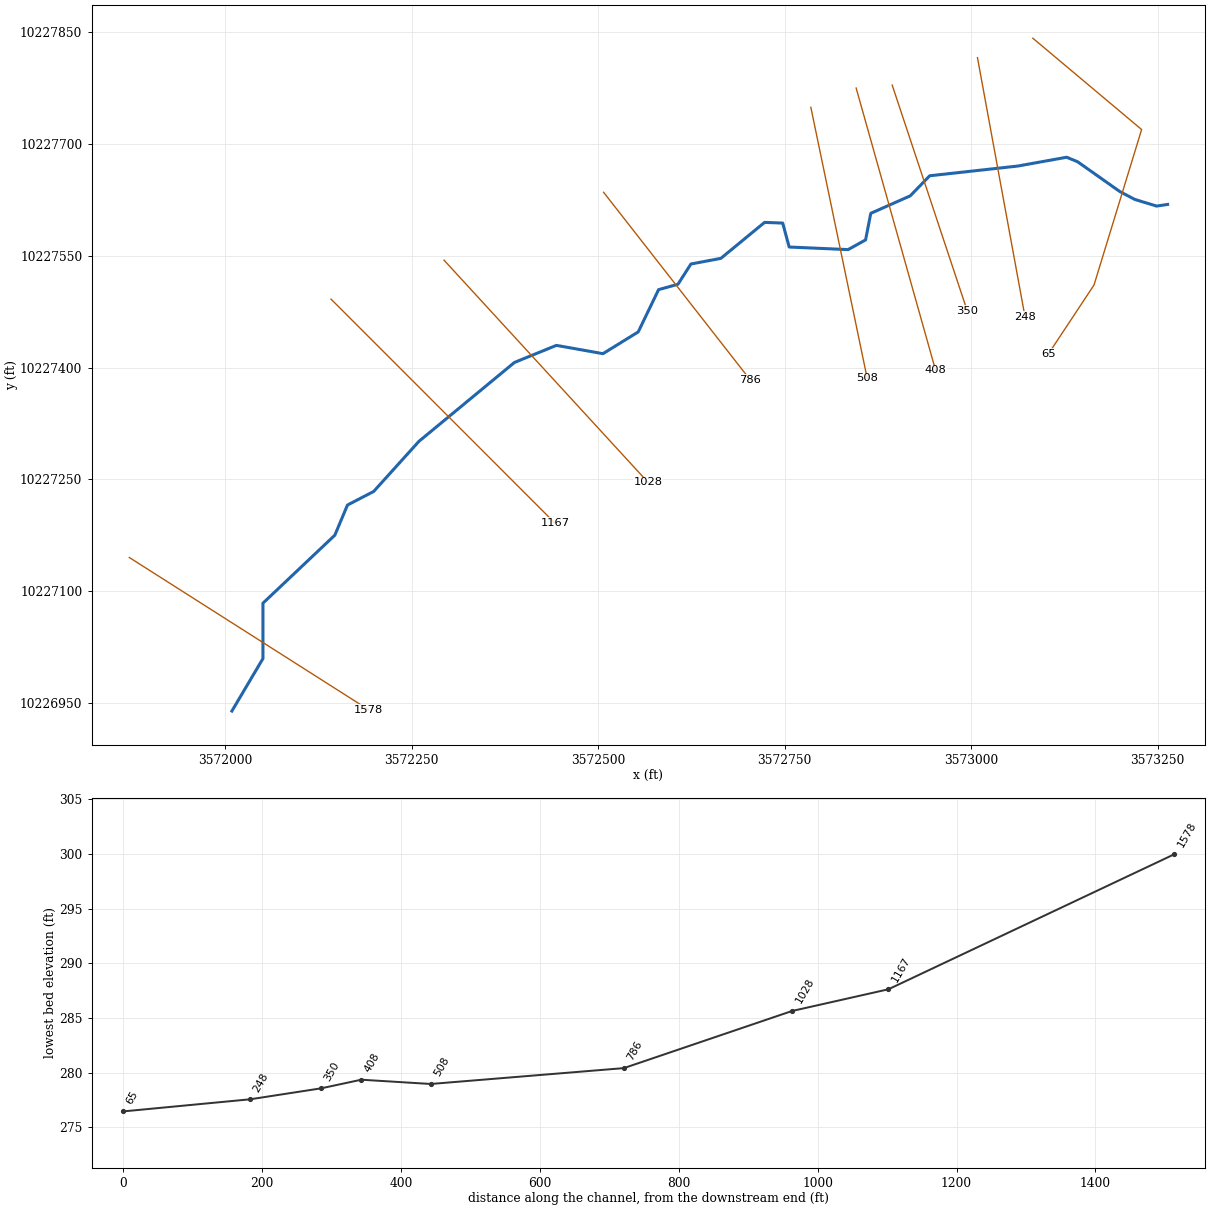
--- UNT115 IN WICK.prj (project) ---

Proj Title=UNT115 IN WICK Base Level Engineering
Current Plan=p01
Default Exp/Contr=0.3,0.1
English Units
Geom File=g01
Flow File=f01
Plan File=p01
Y Axis Title=Elevation
X Axis Title(PF)=Main Channel Distance
X Axis Title(XS)=Station
BEGIN DESCRIPTION:
UNT115 IN WICK
END DESCRIPTION:
DSS Export Rating Curves= 0
DSS Export Rating Curve Sorted= 0
DSS Export Volume Flow Curves= 0
DXF OffsetX= 0
DXF OffsetY= 0
DXF ScaleX= 1
DXF ScaleY= 10

--- UNT115 IN WICK.p01 (plan) ---

Plan Title=Multiple Run
Short Identifier=Multiple
Geom File=g01
Flow File=f01
Subcritical Flow
K Sum by GR= 0
Std Step Tol= 0.01
Critical Tol= 0.01
Num of Std Step Trials= 20
Max Error Tol= 0.3
Flow Tol Ratio= 0.001
Split Flow NTrial= 30
Split Flow Tol= 0.02
Split Flow Ratio= 0.02
Log Output Level= 0
Friction Slope Method= 1
Unsteady Friction Slope Method= 2
Unsteady Bridges Friction Slope Method= 1
Parabolic Critical Depth
Global Vel Dist=  1 , 1 , 1
Global Log Level= 0
CheckData=True
Encroach Param= -1, 0, 0, 0
BEGIN DESCRIPTION:
Multiple Run
END DESCRIPTION:

--- UNT115 IN WICK.f01 (steady flow) ---

Flow Title=Multiple
Program Version=4.10
Number of Profiles= 7
Profile Names=10-year,25-year,50-year,1pct_min,100-year,1pct_plu,500-year
River Rch & RM=UNT115 IN WICK,Reach-1         ,1578
     126     155     176     148     200     270     257
Boundary for River Rch & Prof#=UNT115 IN WICK,Reach-1         , 1
Up Type= 0
Dn Type= 3
Dn Slope=0.0055
Boundary for River Rch & Prof#=UNT115 IN WICK,Reach-1         , 2
Up Type= 0
Dn Type= 3
Dn Slope=0.0055
Boundary for River Rch & Prof#=UNT115 IN WICK,Reach-1         , 3
Up Type= 0
Dn Type= 3
Dn Slope=0.0055
Boundary for River Rch & Prof#=UNT115 IN WICK,Reach-1         , 4
Up Type= 0
Dn Type= 3
Dn Slope=0.0055
Boundary for River Rch & Prof#=UNT115 IN WICK,Reach-1         , 5
Up Type= 0
Dn Type= 3
Dn Slope=0.0055
Boundary for River Rch & Prof#=UNT115 IN WICK,Reach-1         , 6
Up Type= 0
Dn Type= 3
Dn Slope=0.0055
Boundary for River Rch & Prof#=UNT115 IN WICK,Reach-1         , 7
Up Type= 0
Dn Type= 3
Dn Slope=0.0055
DSS Import GetInterval= 0
DSS Import GetPeak= 0
DSS Import FillOption= 0

--- UNT115 IN WICK.g01 (geometry) ---

Geom Title=Existing Conditions
Program Version=4.10

River Reach=UNT115 IN WICK  ,Reach-1
Reach XY= 30
      3572009.12     10226939.71      3572050.78     10227010.03
      3572050.78     10227084.24      3572147.14     10227175.39
      3572164.06     10227215.76      3572199.22     10227233.98
      3572259.86     10227301.13      3572387.86     10227406.82
      3572444.11     10227429.73      3572506.61     10227418.62
      3572553.83     10227447.79      3572581.12     10227504.42
      3572607.09     10227511.63      3572624.45     10227538.76
       3572664.6     10227546.35      3572723.19     10227594.53
      3572747.49     10227593.66      3572756.18     10227561.55
      3572835.17     10227558.07      3572858.61     10227571.09
      3572865.55     10227606.68       3572918.5     10227630.12
      3572944.54     10227657.03       3573062.6     10227670.05
      3573128.14     10227681.86      3573142.76     10227675.85
      3573199.42     10227635.89       3573219.4     10227625.36
      3573248.73     10227616.41       3573263.5     10227618.63

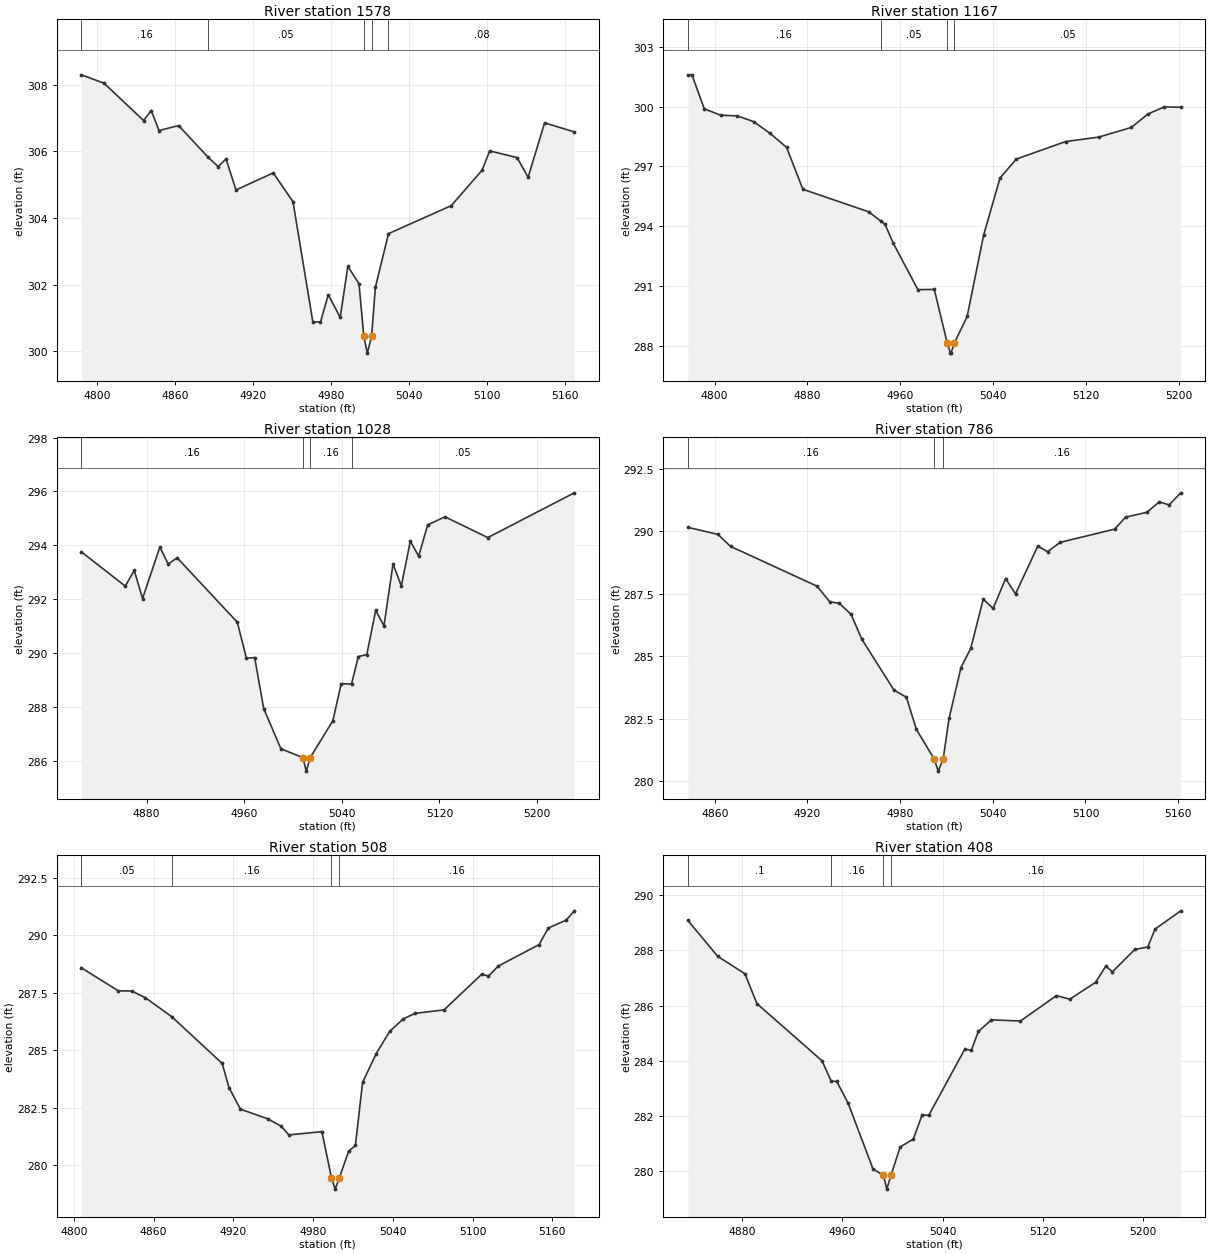
Type RM Length L Ch R = 1 ,1578    ,411,411,411
BEGIN DESCRIPTION:
UNT115 IN WICK 3.0
END DESCRIPTION:
XS GIS Cut Line= 2
      3571871.64     10227145.45      3572192.12     10226941.63
#Sta/Elev= 30
  4787.7  308.29  4805.1  308.04  4835.6  306.92  4841.5  307.22  4847.5  306.62
  4862.6  306.77  4885.3  305.82  4893.1  305.54  4899.1  305.77  4906.8  304.84
  4935.5  305.35  4950.7  304.49    4966  300.89  4971.9  300.88  4977.9   301.7
  4987.1  301.02    4993  302.55  5001.6  302.03  5005.3  300.45    5008  299.95
  5011.3  300.45  5014.2  301.92  5024.3  303.53  5072.7  304.37  5096.4  305.43
  5102.3  306.01  5123.4  305.81  5131.9  305.22  5144.6  306.85  5167.5  306.58
#Mann= 5 ,-1 , 0
  4787.7     .16       0  4885.3     .05       0  5005.3     .04       0
  5011.3     .05       0  5024.3     .08       0
Bank Sta=5005.3,5011.3
XS Rating Curve= 0 ,0
Exp/Cntr=0.3,0.1

Type RM Length L Ch R = 1 ,1167    ,139,139,139
BEGIN DESCRIPTION:
UNT115 IN WICK 2.0
END DESCRIPTION:
XS GIS Cut Line= 2
       3572142.1     10227491.65      3572442.13     10227191.62
#Sta/Elev= 29
  4777.1   301.6  4780.6   301.6  4791.2  299.89  4805.4  299.57  4819.5  299.54
  4833.7  299.25  4847.8  298.66    4862  297.96  4876.1  295.85  4932.7  294.72
    4943  294.26  4946.8  294.09  4953.9  293.14  4975.1  290.81  4989.2  290.82
  5000.4  288.12  5003.1  287.62  5003.6  287.62  5006.4  288.12  5017.5  289.46
  5031.7  293.55  5045.8  296.42  5059.9  297.37  5102.4  298.25  5130.7  298.47
  5158.9  298.96  5173.1  299.63  5187.2  299.99  5201.4  299.97
#Mann= 4 ,-1 , 0
  4777.1     .16       0    4943     .05       0  5000.4     .04       0
  5006.4     .05       0
Bank Sta=5000.4,5006.4
XS Rating Curve= 0 ,0
Exp/Cntr=0.3,0.1

Type RM Length L Ch R = 1 ,1028    ,242,242,242
BEGIN DESCRIPTION:
Mapping XS e8e1b0f5
END DESCRIPTION:
XS GIS Cut Line= 2
      3572293.54     10227543.89      3572566.82     10227246.34
#Sta/Elev= 30
  4826.6  293.76  4862.5  292.49  4869.9  293.07  4876.7  292.03  4890.9  293.94
  4897.7  293.31  4905.1  293.54  4954.4  291.15  4961.8  289.82  4968.6  289.84
    4976  287.95  4990.1  286.46  5008.1  286.13  5010.9  285.63  5014.1  286.13
  5032.7   287.5  5039.5  288.87    5048  288.86  5053.6  289.88  5060.5  289.95
  5067.8  291.59  5074.6  291.02    5082  293.31  5088.8   292.5  5096.2  294.16
    5103   293.6  5110.4  294.76  5124.6  295.06  5159.7  294.29  5230.6  295.95
#Mann= 4 ,-1 , 0
  4826.6     .16       0  5008.1     .07       0  5014.1     .16       0
    5048     .05       0
Bank Sta=5008.1,5014.1
XS Rating Curve= 0 ,0
Exp/Cntr=0.3,0.1

Type RM Length L Ch R = 1 ,786     ,278,278,278
BEGIN DESCRIPTION:
Mapping XS 7f33ae50
END DESCRIPTION:
XS GIS Cut Line= 2
      3572507.42     10227634.88      3572703.95     10227383.48
#Sta/Elev= 30
  4842.6  290.15    4862  289.87  4870.2  289.39  4926.2   287.8  4934.4  287.18
  4940.7  287.11  4948.3  286.67  4955.2  285.68    4976  283.65  4984.1  283.36
  4990.5  282.08  5001.9  280.91  5004.7  280.41  5007.9  280.91  5011.7  282.52
  5019.4  284.55  5025.7  285.31  5033.8  287.28  5040.2  286.91  5048.3   288.1
  5054.7  287.49  5069.1   289.4  5075.5  289.18  5083.6  289.55  5118.9  290.08
    5126  290.56  5139.7  290.75  5147.8  291.17  5154.1  291.05  5161.7  291.53
#Mann= 3 ,-1 , 0
  4842.6     .16       0  5001.9     .07       0  5007.9     .16       0
Bank Sta=5001.9,5007.9
XS Rating Curve= 0 ,0
Exp/Cntr=0.3,0.1

Type RM Length L Ch R = 1 ,508     ,100,100,100
BEGIN DESCRIPTION:
Mapping XS 63439fd4
END DESCRIPTION:
XS GIS Cut Line= 2
      3572785.21     10227748.76      3572860.73     10227385.73
#Sta/Elev= 30
  4805.7  288.59  4833.4  287.59  4843.6  287.58  4853.8  287.29  4873.7  286.46
  4911.6  284.43  4916.7  283.38  4925.3  282.44  4945.8  282.02    4956   281.7
  4961.7  281.32  4986.6  281.46  4993.8  279.46  4996.6  278.96  4999.8  279.46
  5006.7  280.61  5011.8  280.86  5017.2   283.6  5027.5  284.86  5037.7  285.83
  5047.9  286.37  5056.8  286.61  5078.5  286.76  5106.8  288.31  5111.9  288.23
  5119.4  288.67    5150   289.6  5156.9  290.32  5170.5  290.67  5176.5  291.07
#Mann= 4 ,-1 , 0
  4805.7     .05       0  4873.7     .16       0  4993.8     .07       0
  4999.8     .16       0
Bank Sta=4993.8,4999.8
XS Rating Curve= 0 ,0
Exp/Cntr=0.3,0.1

Type RM Length L Ch R = 1 ,408     ,58,58,58
BEGIN DESCRIPTION:
Mapping XS 0ea2a5da
END DESCRIPTION:
XS GIS Cut Line= 2
      3572845.95     10227774.57      3572952.46     10227396.28
#Sta/Elev= 30
  4836.9  289.08  4860.7  287.78  4882.4  287.15  4891.9  286.07  4943.8     284
  4951.2  283.26  4955.6  283.25  4964.6  282.47  4984.5  280.08  4992.8  279.85
  4995.5  279.35  4998.8  279.85  5006.2  280.88  5016.6  281.16  5023.7  282.04
  5028.9  282.02  5057.7  284.42  5062.9  284.38  5068.5  285.06  5078.9  285.48
  5102.1  285.44  5130.8  286.36  5141.4  286.23    5162  286.84  5170.2  287.43
  5175.4  287.22  5193.2  288.03  5203.6  288.12  5209.4  288.77  5229.9  289.43
#Mann= 4 ,-1 , 0
  4836.9      .1       0  4951.2     .16       0  4992.8     .07       0
  4998.8     .16       0
Bank Sta=4992.8,4998.8
XS Rating Curve= 0 ,0
Exp/Cntr=0.3,0.1

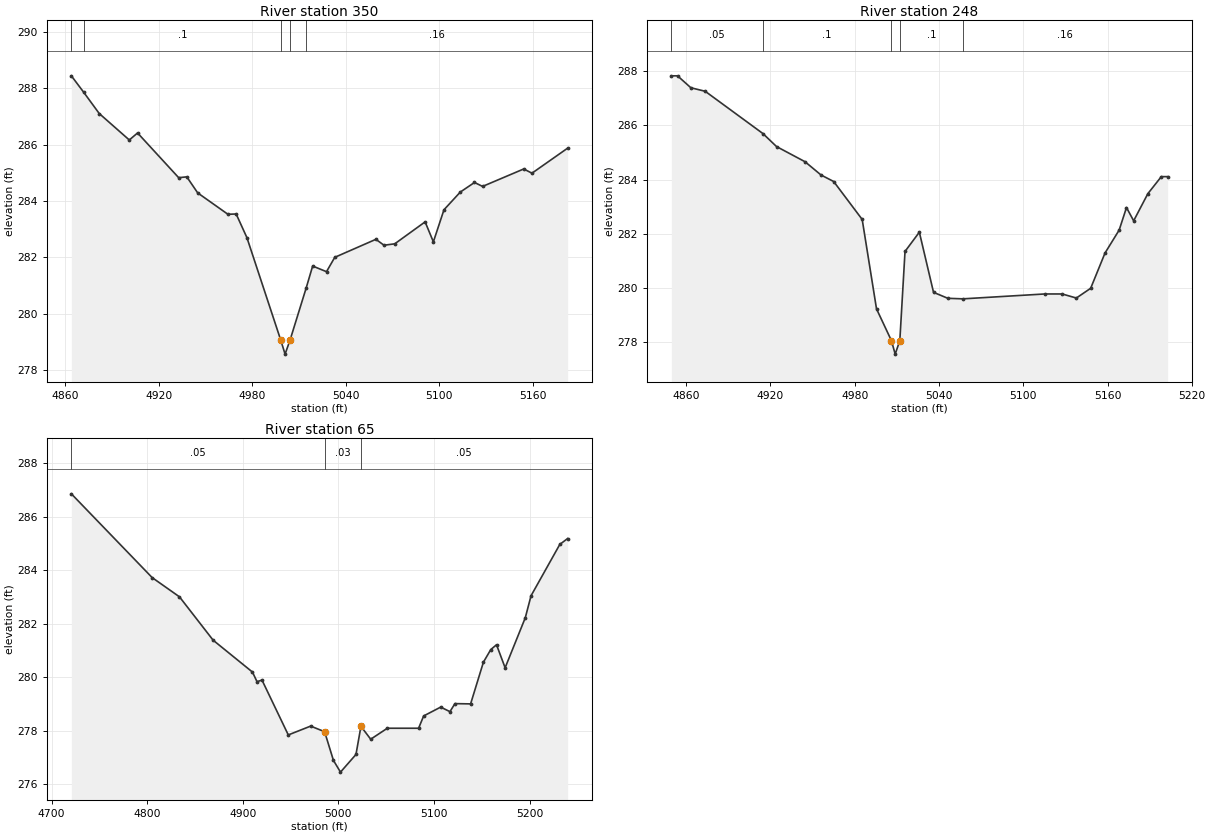
Type RM Length L Ch R = 1 ,350     ,102,102,102
BEGIN DESCRIPTION:
Mapping XS d29c6ba3
END DESCRIPTION:
XS GIS Cut Line= 2
      3572894.25     10227778.59      3572994.79     10227476.27
#Sta/Elev= 30
  4863.9  288.45  4871.9  287.86  4881.8  287.11  4901.1  286.17  4906.4  286.42
  4932.8  284.83    4938  284.86    4945  284.29  4964.4  283.53  4969.7  283.54
  4976.6   282.7  4998.3  279.06  5001.1  278.56  5004.3  279.06  5014.7  280.92
  5018.8  281.69  5027.7  281.49    5033     282  5059.4  282.64  5064.6  282.43
  5071.5  282.48    5091  283.26  5096.3  282.55  5103.1  283.69  5113.6  284.32
  5122.7  284.66  5127.9  284.52  5154.3  285.14  5159.6  284.99  5182.5  285.88
#Mann= 5 ,-1 , 0
  4863.9     .05       0  4871.9      .1       0  4998.3     .07       0
  5004.3      .1       0  5014.7     .16       0
Bank Sta=4998.3,5004.3
XS Rating Curve= 0 ,0
Exp/Cntr=0.3,0.1

Type RM Length L Ch R = 1 ,248     ,183,183,183
BEGIN DESCRIPTION:
Mapping XS 7f19e1f1
END DESCRIPTION:
XS GIS Cut Line= 2
      3573008.58     10227815.32      3573072.37     10227467.73
#Sta/Elev= 30
  4849.4  287.83  4853.8  287.83  4863.3  287.39  4873.5  287.26  4914.6   285.7
  4924.3  285.22  4944.6  284.66    4956  284.17    4965  283.93  4985.3  282.53
  4995.5  279.23  5006.1  278.06  5008.8  277.56  5012.1  278.06  5015.8  281.35
    5026  282.06  5036.1  279.84  5046.3  279.62    5057   279.6  5115.3  279.78
  5127.7  279.78  5137.8  279.63    5148  279.99  5158.2  281.29  5168.3  282.14
  5173.5  282.97  5178.6  282.48  5188.7  283.48  5198.3  284.11  5202.8  284.11
#Mann= 5 ,-1 , 0
  4849.4     .05       0  4914.6      .1       0  5006.1     .07       0
  5012.1      .1       0    5057     .16       0
Bank Sta=5006.1,5012.1
XS Rating Curve= 0 ,0
Exp/Cntr=0.3,0.1

Type RM Length L Ch R = 1 ,65      ,0,0,0
BEGIN DESCRIPTION:
UNT115 IN WICK 1.0
END DESCRIPTION:
XS GIS Cut Line= 4
      3573082.82     10227841.36      3573228.63     10227718.99
      3573164.83     10227510.65      3573103.63     10227418.21
#Sta/Elev= 30
  4720.7  286.85  4805.2  283.72  4833.8     283    4869  281.38  4910.1  280.19
  4914.9  279.83  4920.1  279.89  4947.6  277.84    4971  278.17  4985.6  277.96
 4994.81  276.89  5002.2  276.45  5018.4  277.11  5023.6  278.16  5033.8  277.68
  5051.2  278.09  5083.9  278.09  5089.2  278.55    5107  278.88  5116.7  278.71
  5121.9  279.01  5138.3     279  5151.7  280.56  5159.4  281.03  5165.4  281.21
  5174.4  280.35  5195.5  282.22  5201.5  283.04  5231.6  284.96  5239.8  285.18
#Mann= 3 , 0 , 0
  4720.7     .05       0  4985.6     .03       0  5023.6     .05       0
Bank Sta=4985.6,5023.6
XS Rating Curve= 0 ,0
Exp/Cntr=0.3,0.1

Chan Stop Cuts=-1
Use User Specified Reach Order=0
Composite Channel Slope=5