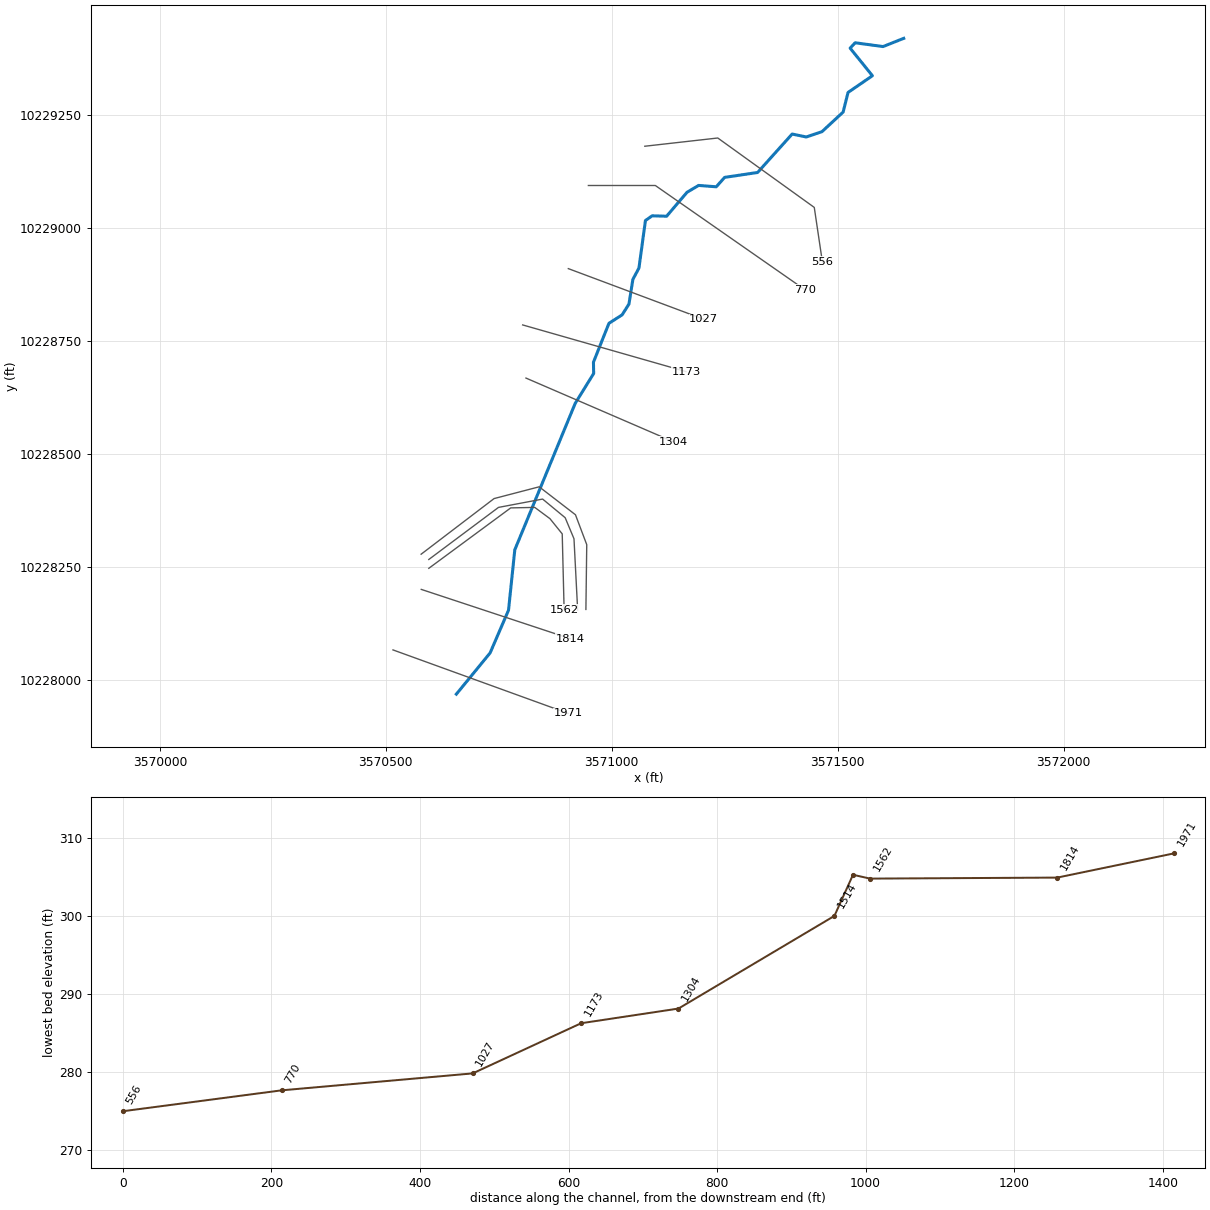
--- UNT117 IN WICK.prj (project) ---

Proj Title=UNT117 IN WICK Base Level Engineering
Current Plan=p01
Default Exp/Contr=0.3,0.1
English Units
Geom File=g01
Flow File=f01
Plan File=p01
BEGIN DESCRIPTION:
UNT117 IN WICK
END DESCRIPTION:

--- UNT117 IN WICK.p01 (plan) ---

Plan Title=Multiple Run
Short Identifier=Multiple
Geom File=g01
Flow File=f01
Subcritical Flow
K Sum by GR= 0
Std Step Tol= 0.01
Critical Tol= 0.01
Num of Std Step Trials= 20
Max Error Tol= 0.3
Flow Tol Ratio= 0.001
Split Flow NTrial= 30
Split Flow Tol= 0.02
Split Flow Ratio= 0.02
Log Output Level= 0
Friction Slope Method= 1
Unsteady Friction Slope Method= 2
Unsteady Bridges Friction Slope Method= 1
Parabolic Critical Depth
Global Vel Dist=  1 , 1 , 1
Global Log Level= 0
CheckData=True
Encroach Param= -1, 0, 0, 0
BEGIN DESCRIPTION:
Multiple Run
END DESCRIPTION:

--- UNT117 IN WICK.f01 (steady flow) ---

Flow Title=Multiple
Number of Profiles=7
Profile Names=10-year,25-year,50-year,1pct_min,100-year,1pct_plu,500-year
River Rch & RM= UNT117 IN WICK,Reach-1,1971
      86     101     113      93     125     170     154
Boundary for River Rch & Prof#=UNT117 IN WICK,Reach-1,1
Up Type=0
Dn Type=3
Dn Slope=0.005
Boundary for River Rch & Prof#=UNT117 IN WICK,Reach-1,2
Up Type=0
Dn Type=3
Dn Slope=0.005
Boundary for River Rch & Prof#=UNT117 IN WICK,Reach-1,3
Up Type=0
Dn Type=3
Dn Slope=0.005
Boundary for River Rch & Prof#=UNT117 IN WICK,Reach-1,4
Up Type=0
Dn Type=3
Dn Slope=0.005
Boundary for River Rch & Prof#=UNT117 IN WICK,Reach-1,5
Up Type=0
Dn Type=3
Dn Slope=0.005
Boundary for River Rch & Prof#=UNT117 IN WICK,Reach-1,6
Up Type=0
Dn Type=3
Dn Slope=0.005
Boundary for River Rch & Prof#=UNT117 IN WICK,Reach-1,7
Up Type=0
Dn Type=3
Dn Slope=0.005

--- UNT117 IN WICK.g01 (geometry) ---

Geom Title=Existing Conditions

River Reach=UNT117 IN WICK,Reach-1
Reach XY= 30
      3570656.20     10227968.99      3570730.85     10228060.13
      3570771.65     10228154.75      3570785.54     10228288.43
      3570919.26     10228612.57      3570960.06     10228678.54
      3570959.62     10228703.71      3570993.91     10228789.65
      3571022.99     10228808.31      3571038.18     10228832.18
      3571046.86     10228886.87      3571060.32     10228912.05
      3571074.64     10229017.08      3571089.40     10229027.50
      3571121.51     10229026.63      3571166.65     10229079.58
      3571192.26     10229094.77      3571231.32     10229091.73
      3571249.99     10229112.57      3571322.90     10229123.42
      3571399.29     10229208.49      3571430.54     10229201.98
      3571465.26     10229213.69      3571512.14     10229257.10
      3571522.99     10229300.50      3571576.90     10229337.48
      3571527.59     10229398.59      3571538.70     10229410.40
      3571600.51     10229402.06      3571646.22     10229420.26

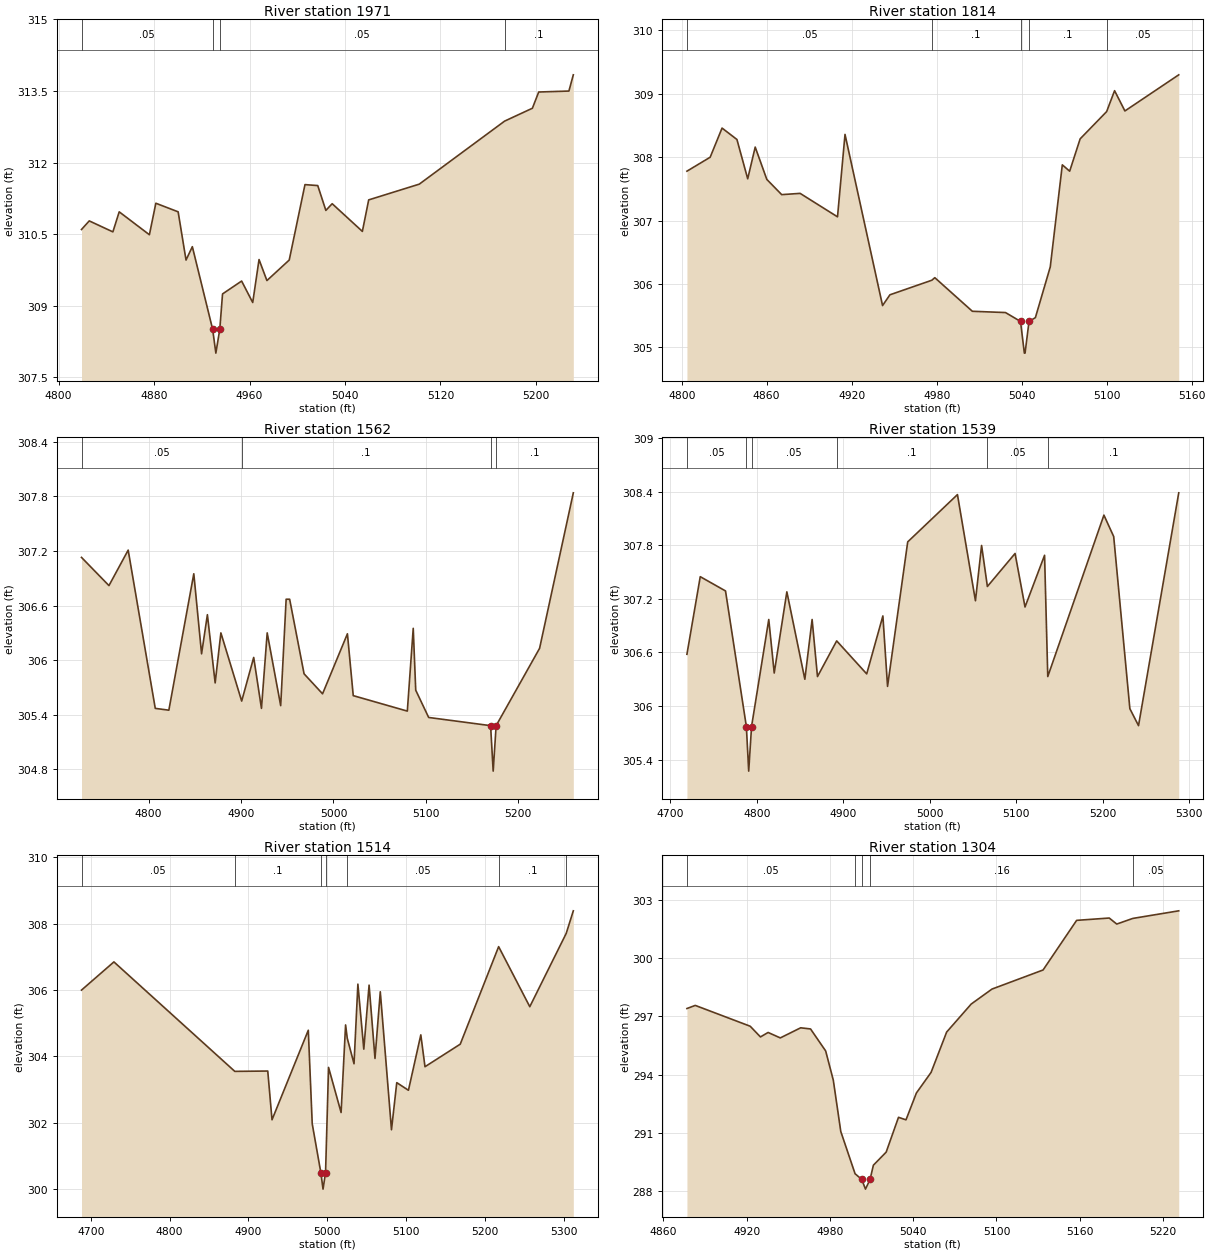
Type RM Length L Ch R = 1,1971,157,157,157
BEGIN DESCRIPTION:
UNT117 IN WICK 4.0
END DESCRIPTION:
XS GIS Cut Line= 2
      3570515.97     10228066.91      3570903.50     10227926.46
#Sta/Elev= 30
  4819.2  310.60  4825.7  310.78  4845.5  310.55  4850.8  310.97  4876.1  310.49
  4881.5  311.15  4900.2  310.97  4906.8  309.96  4912.1  310.24  4929.1  308.51
  4931.8  308.01  4935.1  308.51  4937.4  309.25  4953.4  309.52  4962.7  309.07
  4968.0  309.97  4974.6  309.53  4993.3  309.96  5006.5  311.54  5017.2  311.52
  5024.0  311.00  5029.3  311.14  5054.6  310.56  5059.9  311.22  5102.3  311.55
  5173.8  312.87  5197.1  313.14  5202.4  313.48  5227.7  313.50  5231.4  313.84
#Mann=4,-1,0
  4819.2    0.05       0  4929.1    0.03       0  4935.1    0.05       0
  5173.8     0.1       0
Bank Sta=4929.1,4935.1
Exp/Cntr=0.3,0.1

Type RM Length L Ch R = 1,1814,252,252,252
BEGIN DESCRIPTION:
Mapping XS 05fb53b0
END DESCRIPTION:
XS GIS Cut Line= 2
      3570578.57     10228200.83      3570908.21     10228091.81
#Sta/Elev= 30
  4803.7  307.78  4820.1  308.00  4828.5  308.46  4839.0  308.28  4846.6  307.66
  4851.9  308.16  4860.1  307.65  4870.6  307.41  4883.6  307.43  4910.0  307.06
  4915.3  308.36  4941.8  305.66  4947.0  305.83  4976.6  306.06  4978.7  306.10
  5005.2  305.57  5028.6  305.55  5039.2  305.41  5041.9  304.91  5042.4  304.91
  5045.2  305.41  5049.7  305.47  5060.2  306.27  5068.7  307.88  5073.9  307.78
  5081.3  308.29  5100.0  308.72  5105.6  309.05  5112.9  308.73  5150.9  309.30
#Mann=5,-1,0
  4803.7    0.05       0  4976.6     0.1       0  5039.2    0.07       0
  5045.2     0.1       0  5100.0    0.05       0
Bank Sta=5039.2,5045.2
Exp/Cntr=0.3,0.1

Type RM Length L Ch R = 1,1562,23,23,23
BEGIN DESCRIPTION:
Mapping XS 9692c01d
END DESCRIPTION:
XS GIS Cut Line= 6
      3570595.28     10228247.49      3570776.57     10228381.18
      3570829.74     10228382.26      3570863.38     10228357.31
      3570890.50     10228323.67      3570894.70     10228155.18
#Sta/Elev= 30
  4727.4  307.13  4757.1  306.82  4777.9  307.21  4807.2  305.47  4821.9  305.45
  4848.9  306.95  4857.3  306.07  4863.6  306.50  4872.0  305.75  4878.2  306.30
  4900.7  305.55  4913.7  306.03  4922.1  305.47  4928.3  306.30  4942.9  305.50
  4948.8  306.67  4952.6  306.67  4968.2  305.85  4988.2  305.63  5015.1  306.29
  5021.4  305.61  5079.9  305.44  5086.3  306.35  5089.0  305.67  5103.0  305.37
  5170.0  305.28  5172.8  304.78  5176.0  305.28  5223.0  306.13  5259.5  307.84
#Mann=4,-1,0
  4727.4    0.05       0  4900.7     0.1       0  5170.0    0.07       0
  5176.0     0.1       0
Bank Sta=5170,5176
Exp/Cntr=0.3,0.1

Type RM Length L Ch R = 1,1539,25,25,25
BEGIN DESCRIPTION:
Mapping XS 54886fc0
END DESCRIPTION:
XS GIS Cut Line= 6
      3570595.27     10228267.02      3570749.44     10228382.26
      3570847.10     10228400.71      3570897.01     10228359.48
      3570916.54     10228312.82      3570924.64     10228155.13
#Sta/Elev= 30
  4719.2  306.58  4734.6  307.45  4763.8  307.29  4787.9  305.77  4790.6  305.27
  4793.9  305.77  4813.8  306.97  4820.1  306.37  4834.7  307.28  4855.5  306.30
  4863.9  306.97  4870.1  306.33  4892.3  306.73  4927.0  306.36  4945.7  307.01
  4951.1  306.22  4974.4  307.84  5031.9  308.37  5052.7  307.18  5059.8  307.80
  5066.5  307.34  5098.5  307.71  5110.0  307.11  5132.6  307.69  5136.3  306.33
  5201.2  308.14  5212.5  307.90  5231.2  305.97  5241.2  305.78  5287.7  308.39
#Mann=6,-1,0
  4719.2    0.05       0  4787.9    0.07       0  4793.9    0.05       0
  4892.3     0.1       0  5066.5    0.05       0  5136.3     0.1       0
Bank Sta=4787.9,4793.9
Exp/Cntr=0.3,0.1

Type RM Length L Ch R = 1,1514,210,210,210
BEGIN DESCRIPTION:
Mapping XS f3caef77
END DESCRIPTION:
XS GIS Cut Line= 6
      3570578.31     10228278.71      3570739.68     10228401.79
      3570839.50     10228427.84      3570919.80     10228365.99
      3570944.76     10228299.80      3570942.90     10228156.45
#Sta/Elev= 30
  4688.3  306.00  4729.4  306.85  4882.7  303.55  4924.5  303.56  4929.9  302.09
  4975.9  304.79  4980.9  301.97  4991.8  300.50  4994.6  300.00  4997.8  300.50
  5001.6  303.67  5017.5  302.31  5023.2  304.95  5025.3  304.55  5033.9  303.78
  5038.8  306.18  5046.3  304.22  5053.0  306.15  5060.5  303.94  5067.2  305.95
  5081.4  301.79  5088.1  303.21  5102.9  302.98  5118.6  304.65  5123.9  303.69
  5168.6  304.37  5217.3  307.31  5256.8  305.50  5303.0  307.71  5312.0  308.39
#Mann=7,-1,0
  4688.3    0.05       0  4882.7     0.1       0  4991.8    0.07       0
  4997.8     0.1       0  5025.3    0.05       0  5217.3     0.1       0
  5303.0    0.05       0
Bank Sta=4991.8,4997.8
Exp/Cntr=0.3,0.1

Type RM Length L Ch R = 1,1304,131,131,131
BEGIN DESCRIPTION:
UNT117 IN WICK 3.0
END DESCRIPTION:
XS GIS Cut Line= 2
      3570810.28     10228668.46      3571135.71     10228527.87
#Sta/Elev= 30
  4876.9  297.40  4882.9  297.56  4922.5  296.49  4929.9  295.94  4935.4  296.17
  4944.2  295.89  4958.9  296.41  4966.0  296.35  4976.9  295.22  4982.4  293.72
  4987.8  291.08  4998.1  288.91  5002.9  288.62  5005.6  288.12  5008.9  288.62
  5011.3  289.35  5020.5  290.02  5029.4  291.81  5034.8  291.68  5042.3  293.06
  5052.9  294.12  5064.1  296.19  5081.8  297.63  5096.8  298.40  5133.6  299.38
  5157.8  301.93  5181.3  302.05  5186.7  301.74  5198.3  302.03  5231.4  302.42
#Mann=5,-1,0
  4876.9    0.05       0  4998.1    0.16       0  5002.9    0.07       0
  5008.9    0.16       0  5198.3    0.05       0
Bank Sta=5002.9,5008.9
Exp/Cntr=0.3,0.1

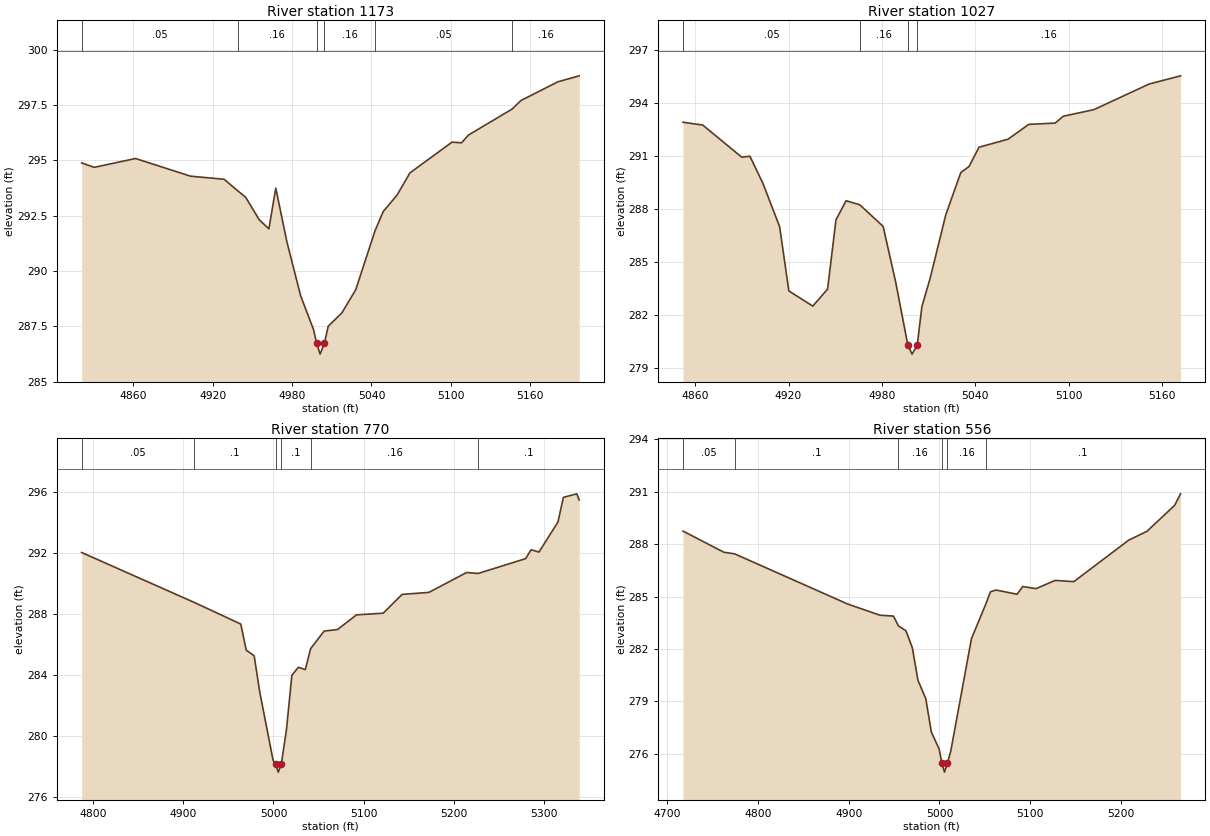
Type RM Length L Ch R = 1,1173,146,146,146
BEGIN DESCRIPTION:
Mapping XS c58b002c
END DESCRIPTION:
XS GIS Cut Line= 2
      3570802.95     10228786.06      3571164.49     10228682.76
#Sta/Elev= 30
  4821.0  294.89  4830.5  294.69  4861.7  295.09  4903.3  294.29  4928.7  294.15
  4938.9  293.63  4944.9  293.34  4955.3  292.31  4962.5  291.91  4967.7  293.75
  4976.1  291.32  4986.5  288.88  4996.3  287.34  4998.5  286.74  5001.2  286.24
  5004.5  286.74  5007.3  287.50  5017.7  288.11  5028.1  289.15  5042.7  291.82
  5048.9  292.69  5059.3  293.43  5069.1  294.44  5100.9  295.83  5108.1  295.80
  5113.3  296.15  5146.4  297.33  5152.9  297.71  5180.9  298.56  5197.0  298.83
#Mann=6,-1,0
  4821.0    0.05       0  4938.9    0.16       0  4998.5    0.07       0
  5004.5    0.16       0  5042.7    0.05       0  5146.4    0.16       0
Bank Sta=4998.5,5004.5
Exp/Cntr=0.3,0.1

Type RM Length L Ch R = 1,1027,257,257,257
BEGIN DESCRIPTION:
UNT117 IN WICK 2.0
END DESCRIPTION:
XS GIS Cut Line= 2
      3570903.98     10228910.66      3571203.43     10228798.69
#Sta/Elev= 30
  4852.2  292.90  4864.9  292.74  4889.9  290.93  4895.2  290.98  4903.6  289.44
  4914.3  287.00  4920.2  283.38  4935.6  282.52  4945.1  283.48  4950.5  287.39
  4957.0  288.47  4965.8  288.24  4980.8  287.02  4989.0  283.82  4996.7  280.31
  4999.4  279.81  5002.7  280.31  5005.7  282.49  5011.1  284.12  5021.0  287.66
  5030.7  290.06  5036.0  290.40  5042.4  291.49  5061.0  291.94  5074.4  292.78
  5091.3  292.85  5096.6  293.24  5116.2  293.61  5151.8  295.06  5171.9  295.52
#Mann=4,-1,0
  4852.2    0.05       0  4965.8    0.16       0  4996.7    0.07       0
  5002.7    0.16       0
Bank Sta=4996.7,5002.7
Exp/Cntr=0.3,0.1

Type RM Length L Ch R = 1,770,214,214,214
BEGIN DESCRIPTION:
Mapping XS eb3e0ca3
END DESCRIPTION:
XS GIS Cut Line= 3
      3570948.36     10229094.61      3571096.51     10229094.61
      3571427.62     10228863.92
#Sta/Elev= 30
  4787.3  292.01  4911.9  288.75  4963.7  287.33  4969.8  285.62  4978.6  285.25
  4984.7  282.90  4999.5  278.43  5002.6  278.14  5005.3  277.64  5008.6  278.14
  5014.3  280.37  5020.4  283.98  5027.6  284.50  5035.3  284.35  5041.2  285.72
  5056.2  286.87  5071.0  286.97  5092.0  287.93  5121.7  288.04  5142.6  289.27
  5172.3  289.40  5214.1  290.70  5227.0  290.64  5279.6  291.61  5285.7  292.19
  5294.4  292.04  5315.4  294.00  5321.5  295.62  5336.3  295.85  5339.0  295.45
#Mann=6,-1,0
  4787.3    0.05       0  4911.9     0.1       0  5002.6    0.07       0
  5008.6     0.1       0  5041.2    0.16       0  5227.0     0.1       0
Bank Sta=5002.6,5008.6
Exp/Cntr=0.3,0.1

Type RM Length L Ch R = 1,556,0,0,0
BEGIN DESCRIPTION:
UNT117 IN WICK 1.0
END DESCRIPTION:
XS GIS Cut Line= 4
      3571073.24     10229181.49      3571234.72     10229199.72
      3571448.26     10229046.08      3571466.26     10228925.19
#Sta/Elev= 30
  4717.6  288.74  4762.6  287.53  4774.4  287.44  4898.9  284.57  4934.5  283.93
  4949.3  283.88  4954.8  283.32  4963.1  283.04  4970.1  282.07  4976.3  280.21
  4984.9  279.16  4991.0  277.26  4999.6  276.28  5002.7  275.46  5005.5  274.96
  5008.7  275.46  5012.4  276.16  5035.2  282.59  5051.1  284.58  5056.1  285.27
  5062.2  285.37  5085.5  285.13  5091.7  285.57  5106.4  285.45  5127.3  285.92
  5147.9  285.85  5208.3  288.22  5228.5  288.73  5258.9  290.21  5265.4  290.87
#Mann=6,-1,0
  4717.6    0.05       0  4774.4     0.1       0  4954.8    0.16       0
  5002.7    0.07       0  5008.7    0.16       0  5051.1     0.1       0
Bank Sta=5002.7,5008.7
Exp/Cntr=0.3,0.1

Chan Stop Cuts=-1