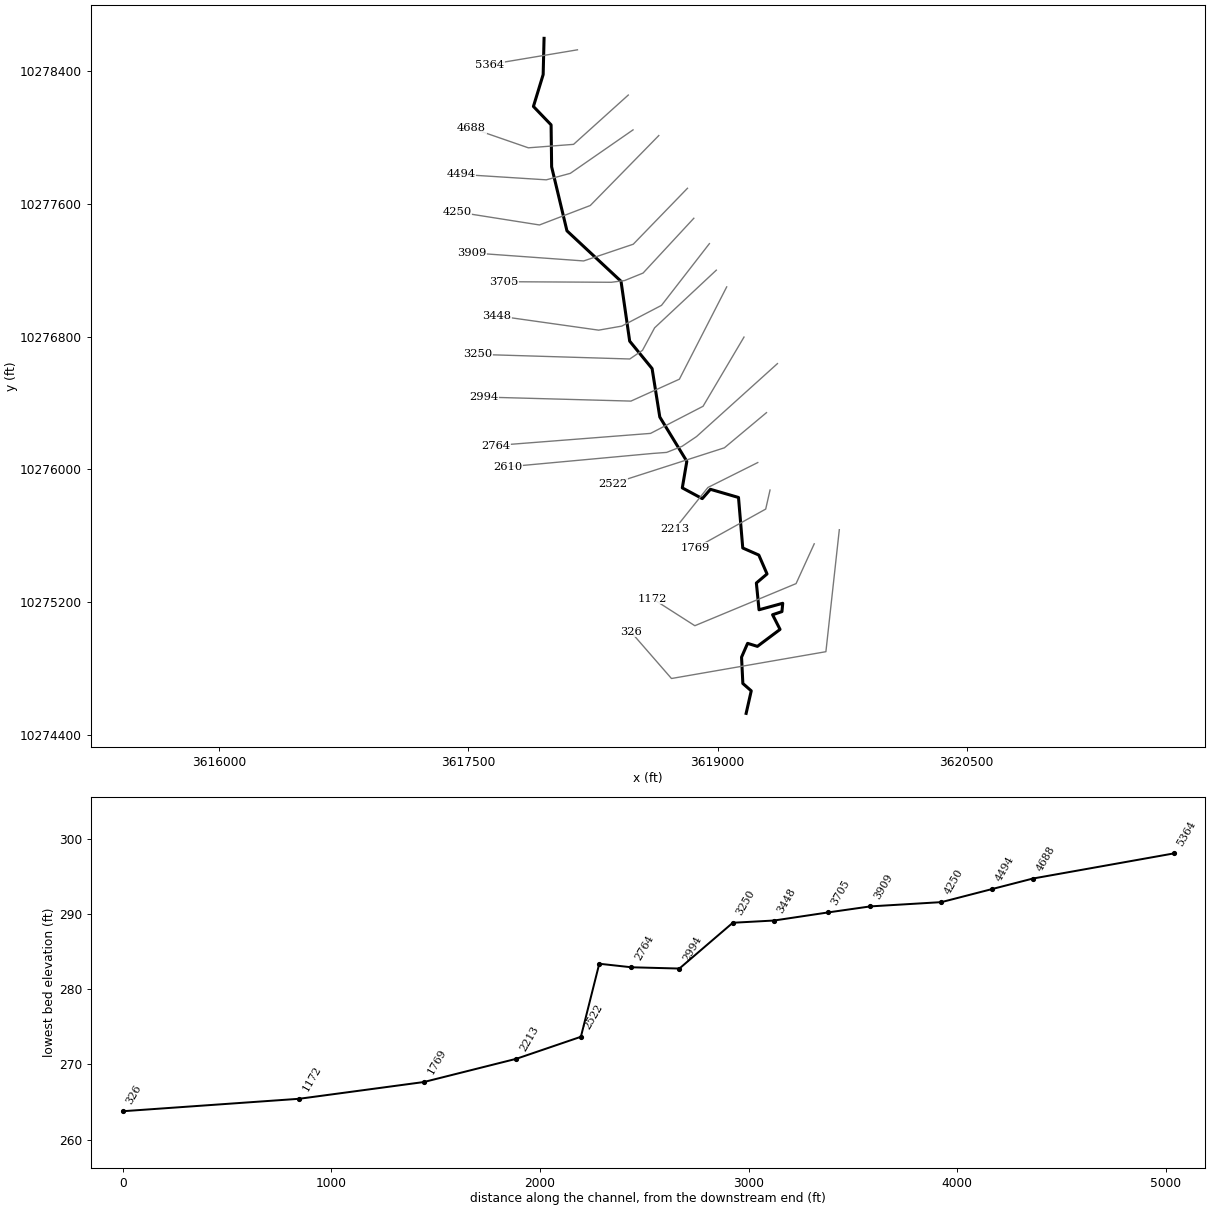
--- UNT997 IN WICK.prj (project) ---

Proj Title=UNT997 IN WICK Base Level Engineering
Current Plan=p01
Default Exp/Contr=0.3,0.1
English Units
Geom File=g01
Flow File=f01
Plan File=p01
BEGIN DESCRIPTION:
UNT997 IN WICK
END DESCRIPTION:

--- UNT997 IN WICK.p01 (plan) ---

Plan Title=Multiple Run
Short Identifier=Multiple
Geom File=g01
Flow File=f01
Subcritical Flow
K Sum by GR= 0
Std Step Tol= 0.01
Critical Tol= 0.01
Num of Std Step Trials= 20
Max Error Tol= 0.3
Flow Tol Ratio= 0.001
Split Flow NTrial= 30
Split Flow Tol= 0.02
Split Flow Ratio= 0.02
Log Output Level= 0
Friction Slope Method= 1
Unsteady Friction Slope Method= 2
Unsteady Bridges Friction Slope Method= 1
Parabolic Critical Depth
Global Vel Dist=  1 , 1 , 1
Global Log Level= 0
CheckData=True
Encroach Param= -1, 0, 0, 0
BEGIN DESCRIPTION:
Multiple Run
END DESCRIPTION:

--- UNT997 IN WICK.f01 (steady flow) ---

Flow Title=Multiple
Number of Profiles=7
Profile Names=10-year,25-year,50-year,1pct_min,100-year,1pct_plu,500-year
River Rch & RM= UNT997 IN WICK,Reach-1,5364
     237     300     349     298     404     546     539
Boundary for River Rch & Prof#=UNT997 IN WICK,Reach-1,1
Up Type=0
Dn Type=3
Dn Slope=0.005
Boundary for River Rch & Prof#=UNT997 IN WICK,Reach-1,2
Up Type=0
Dn Type=3
Dn Slope=0.005
Boundary for River Rch & Prof#=UNT997 IN WICK,Reach-1,3
Up Type=0
Dn Type=3
Dn Slope=0.005
Boundary for River Rch & Prof#=UNT997 IN WICK,Reach-1,4
Up Type=0
Dn Type=3
Dn Slope=0.005
Boundary for River Rch & Prof#=UNT997 IN WICK,Reach-1,5
Up Type=0
Dn Type=3
Dn Slope=0.005
Boundary for River Rch & Prof#=UNT997 IN WICK,Reach-1,6
Up Type=0
Dn Type=3
Dn Slope=0.005
Boundary for River Rch & Prof#=UNT997 IN WICK,Reach-1,7
Up Type=0
Dn Type=3
Dn Slope=0.005

--- UNT997 IN WICK.g01 (geometry) ---

Geom Title=Existing Conditions

River Reach=UNT997 IN WICK,Reach-1
Reach XY= 30
      3617955.61     10278595.45      3617950.18     10278377.35
      3617891.59     10278185.29      3617997.92     10278074.62
      3618001.18     10277821.80      3618093.41     10277436.60
      3618418.93     10277132.78      3618471.01     10276772.53
      3618605.95     10276607.42      3618652.31     10276315.75
      3618815.02     10276048.98      3618787.81     10275889.11
      3618908.03     10275824.51      3618957.00     10275880.60
      3619126.11     10275831.41      3619151.79     10275527.21
      3619248.40     10275484.75      3619297.91     10275370.93
      3619233.74     10275316.43      3619249.70     10275155.33
      3619392.41     10275194.40      3619387.72     10275144.40
      3619331.27     10275125.45      3619376.27     10275037.10
      3619239.81     10274935.02      3619180.95     10274953.25
      3619144.50     10274869.92      3619152.31     10274711.58
      3619202.83     10274667.31      3619172.11     10274531.64

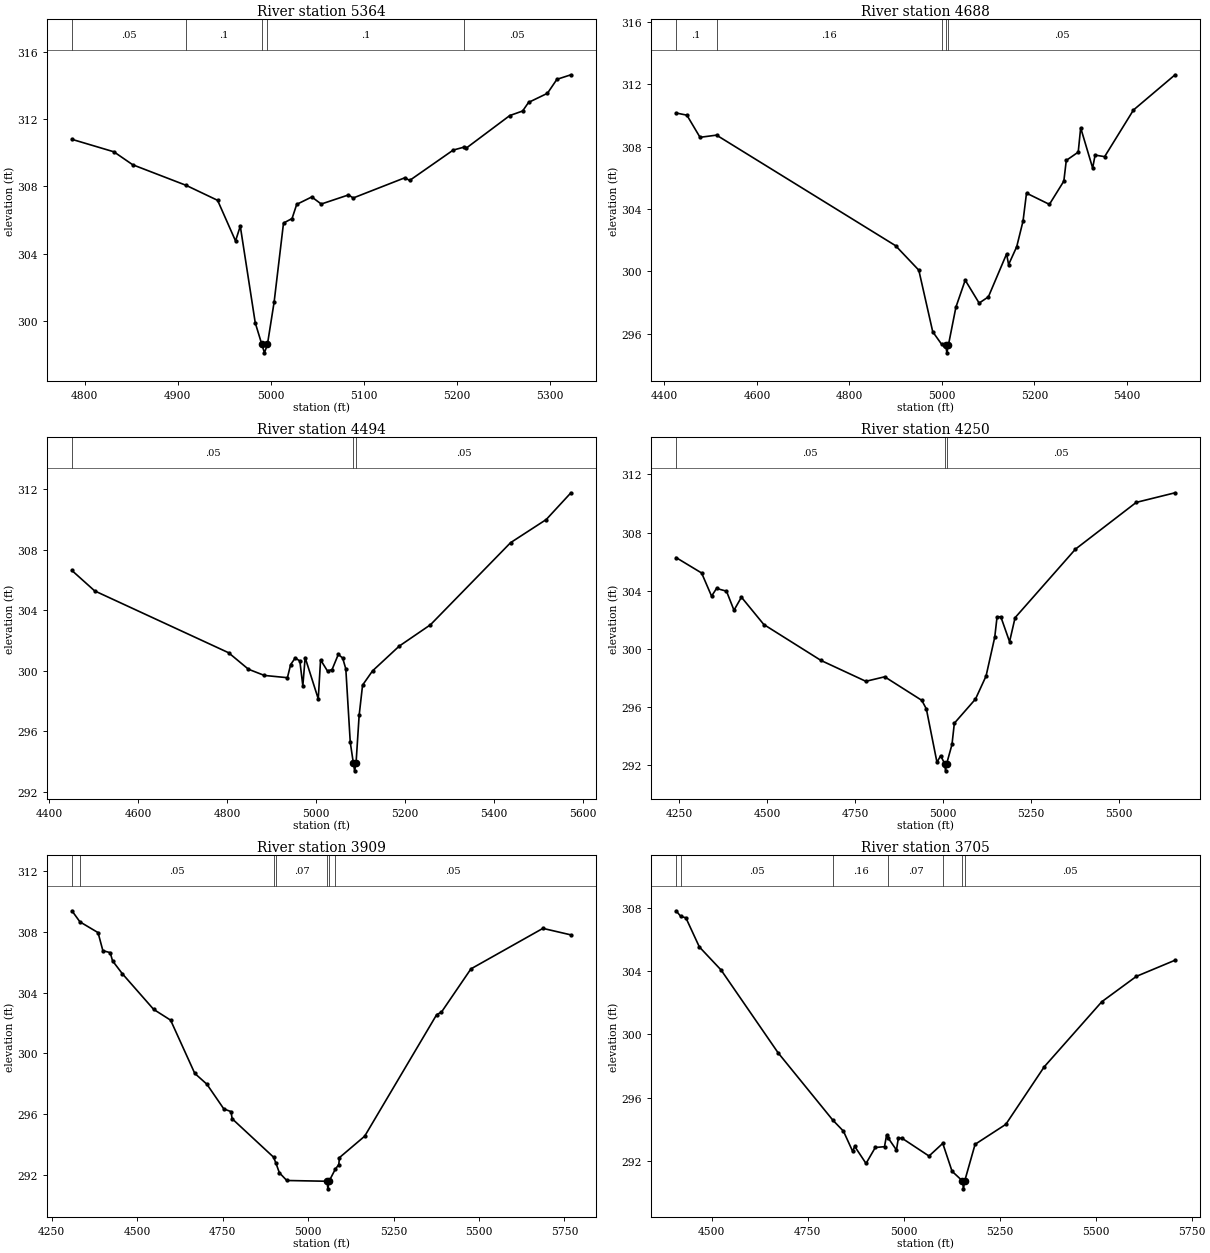
Type RM Length L Ch R = 1,5364,676,676,676
BEGIN DESCRIPTION:
UNT997 IN WICK 5.0
END DESCRIPTION:
XS GIS Cut Line= 2
      3618156.61     10278526.36      3617627.16     10278437.83
#Sta/Elev= 30
  4786.2  310.79  4831.3  310.05  4851.6  309.28  4909.0  308.06  4942.9  307.17
  4962.2  304.76  4967.3  305.64  4983.4  299.90  4990.5  298.62  4993.3  298.12
  4996.5  298.62  5003.7  301.13  5013.8  305.82  5023.0  306.09  5028.0  306.93
  5044.2  307.37  5054.4  306.95  5083.7  307.49  5088.8  307.31  5144.4  308.51
  5149.5  308.35  5196.3  310.15  5207.5  310.32  5210.2  310.26  5257.2  312.20
  5271.0  312.47  5277.4  312.98  5297.7  313.52  5307.9  314.35  5323.0  314.62
#Mann=5,-1,0
  4786.2    0.05       0  4909.0     0.1       0  4990.5    0.07       0
  4996.5     0.1       0  5207.5    0.05       0
Bank Sta=4990.5,4996.5
Exp/Cntr=0.3,0.1

Type RM Length L Ch R = 1,4688,194,194,194
BEGIN DESCRIPTION:
Mapping XS eb4a82c1
END DESCRIPTION:
XS GIS Cut Line= 4
      3618462.61     10278254.05      3618133.19     10277957.18
      3617861.06     10277936.35      3617518.56     10278054.86
#Sta/Elev= 30
  4425.3  310.15  4448.7  310.01  4477.1  308.59  4512.8  308.73  4899.9  301.64
  4950.1  300.07  4980.2  296.12  4999.6  295.31  5008.1  295.27  5010.8  294.77
  5014.1  295.27  5030.3  297.70  5050.4  299.43  5080.5  297.96  5100.5  298.36
  5139.8  301.11  5144.2  300.43  5161.7  301.57  5175.4  303.22  5182.9  305.01
  5232.4  304.29  5263.6  305.78  5268.9  307.11  5294.7  307.64  5300.0  309.20
  5325.9  306.62  5331.2  307.45  5351.8  307.35  5414.1  310.34  5504.1  312.60
#Mann=5,-1,0
  4425.3     0.1       0  4512.8    0.16       0  4999.6    0.05       0
  5008.1    0.03       0  5014.1    0.05       0
Bank Sta=5008.1,5014.1
Exp/Cntr=0.3,0.1

Type RM Length L Ch R = 1,4494,244,244,244
BEGIN DESCRIPTION:
Mapping XS b658711e
END DESCRIPTION:
XS GIS Cut Line= 4
      3618491.26     10278044.42      3618113.66     10277782.70
      3617969.13     10277743.64      3617456.60     10277776.16
#Sta/Elev= 30
  4450.6  306.63  4501.8  305.28  4803.1  301.19  4847.7  300.10  4883.5  299.69
  4935.4  299.54  4942.7  300.41  4953.1  300.85  4963.4  300.64  4970.1  299.00
  4975.3  300.87  5004.8  298.14  5010.0  300.72  5025.6  299.98  5035.9  300.08
  5049.9  301.08  5059.7  300.84  5066.8  300.12  5076.8  295.27  5083.8  293.88
  5086.6  293.38  5089.8  293.88  5096.8  297.05  5104.5  299.05  5126.9  299.99
  5187.0  301.63  5257.2  303.04  5437.5  308.47  5517.7  310.00  5573.3  311.77
#Mann=3,-1,0
  4450.6    0.05       0  5083.8    0.03       0  5089.8    0.05       0
Bank Sta=5083.8,5089.8
Exp/Cntr=0.3,0.1

Type RM Length L Ch R = 1,4250,341,341,341
BEGIN DESCRIPTION:
Mapping XS 1fc41627
END DESCRIPTION:
XS GIS Cut Line= 4
      3618646.24     10278010.16      3618233.89     10277589.13
      3617927.90     10277471.94      3617433.11     10277550.06
#Sta/Elev= 30
  4241.4  306.28  4314.0  305.22  4342.3  303.63  4356.4  304.16  4384.7  303.97
  4406.0  302.66  4427.1  303.56  4490.8  301.68  4653.4  299.21  4780.7  297.78
  4834.2  298.09  4939.7  296.47  4952.6  295.88  4982.7  292.22  4993.3  292.67
  5004.4  292.13  5007.1  291.63  5010.4  292.13  5025.4  293.44  5032.1  294.90
  5092.2  296.56  5122.2  298.14  5146.9  300.81  5153.5  302.21  5164.2  302.21
  5189.0  300.50  5204.7  302.15  5376.3  306.86  5549.0  310.07  5659.3  310.73
#Mann=3,-1,0
  4241.4    0.05       0  5004.4    0.03       0  5010.4    0.05       0
Bank Sta=5004.4,5010.4
Exp/Cntr=0.3,0.1

Type RM Length L Ch R = 1,3909,204,204,204
BEGIN DESCRIPTION:
Mapping XS 417b5401
END DESCRIPTION:
XS GIS Cut Line= 4
      3618818.96     10277692.86      3618492.57     10277356.06
      3618193.96     10277255.36      3617520.35     10277303.97
#Sta/Elev= 30
  4309.4  309.39  4332.8  308.66  4385.8  307.95  4399.9  306.76  4421.3  306.63
  4428.2  306.09  4456.5  305.25  4548.4  302.89  4598.0  302.18  4668.7  298.67
  4704.0  297.96  4753.6  296.33  4774.7  296.15  4778.0  295.68  4899.0  293.15
  4906.3  292.74  4916.1  292.12  4937.8  291.61  5055.4  291.56  5058.1  291.06
  5061.4  291.56  5079.8  292.36  5089.9  292.66  5091.9  293.12  5165.6  294.53
  5376.1  302.54  5390.2  302.71  5476.4  305.56  5686.9  308.23  5768.9  307.80
#Mann=7,-1,0
  4309.4    0.16       0  4332.8    0.05       0  4899.0    0.16       0
  4906.3    0.07       0  5055.4    0.07       0  5061.4    0.07       0
  5079.8    0.05       0
Bank Sta=5055.4,5061.4
Exp/Cntr=0.3,0.1

Type RM Length L Ch R = 1,3705,257,257,257
BEGIN DESCRIPTION:
Mapping XS 674e81b0
END DESCRIPTION:
XS GIS Cut Line= 5
      3618857.18     10277512.33      3618551.60     10277182.44
      3618440.49     10277137.31      3618360.62     10277126.89
      3617711.28     10277130.36
#Sta/Elev= 30
  4407.4  307.80  4419.8  307.44  4432.9  307.36  4468.0  305.52  4524.7  304.06
  4673.3  298.83  4815.5  294.59  4843.3  293.89  4867.2  292.62  4872.6  292.93
  4902.1  291.85  4926.2  292.86  4950.2  292.91  4955.6  293.64  4960.4  293.44
  4981.3  292.70  4986.3  293.45  4995.5  293.45  5066.1  292.32  5101.9  293.12
  5126.1  291.36  5153.1  290.75  5155.8  290.25  5159.1  290.75  5186.1  293.06
  5266.1  294.32  5366.1  297.95  5516.1  302.06  5606.1  303.66  5706.9  304.68
#Mann=7,-1,0
  4407.4    0.16       0  4419.8    0.05       0  4815.5    0.16       0
  4960.4    0.07       0  5101.9    0.05       0  5153.1    0.07       0
  5159.1    0.05       0
Bank Sta=5153.1,5159.1
Exp/Cntr=0.3,0.1

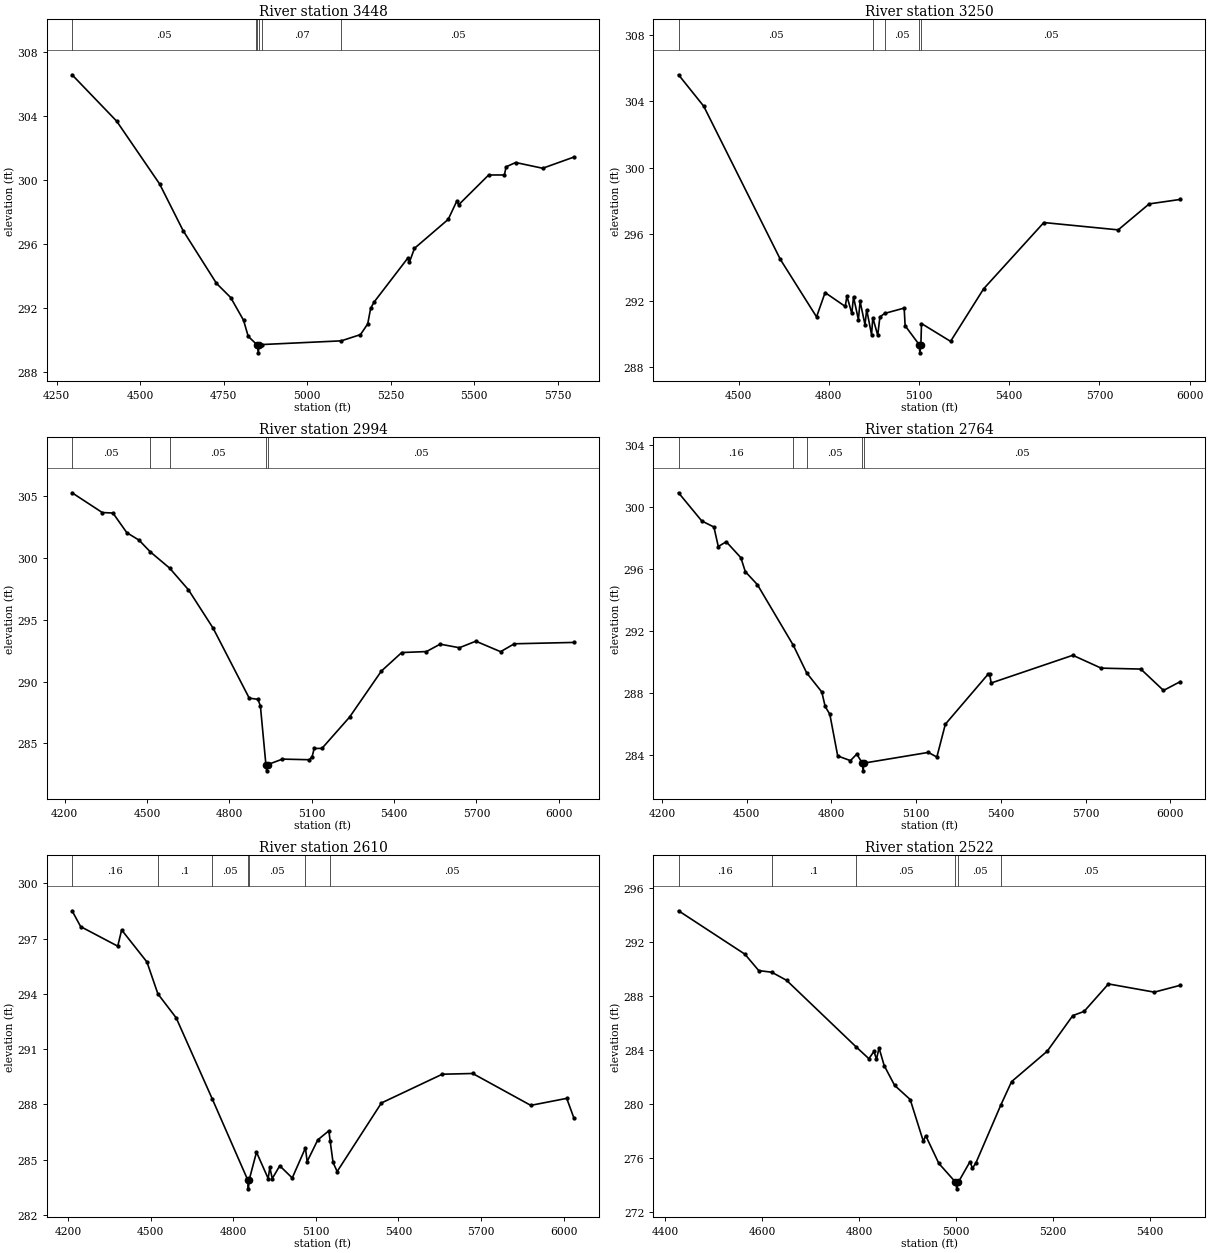
Type RM Length L Ch R = 1,3448,198,198,198
BEGIN DESCRIPTION:
Mapping XS 906effdd
END DESCRIPTION:
XS GIS Cut Line= 5
      3618950.89     10277359.51      3618662.71     10276988.00
      3618423.12     10276863.00      3618284.24     10276838.69
      3617669.65     10276925.50
#Sta/Elev= 30
  4296.1  306.58  4429.5  303.68  4558.1  299.75  4628.7  296.82  4728.3  293.53
  4770.9  292.64  4809.4  291.22  4823.4  290.21  4848.1  289.72  4850.6  289.68
  4853.4  289.18  4856.6  289.68  4865.3  289.70  5101.8  289.93  5159.4  290.32
  5181.1  290.99  5189.8  291.96  5199.9  292.35  5300.8  295.10  5305.9  294.85
  5321.1  295.72  5422.0  297.53  5448.1  298.69  5453.1  298.44  5543.2  300.31
  5590.3  300.31  5595.3  300.82  5624.0  301.09  5704.8  300.73  5798.2  301.43
#Mann=6,-1,0
  4296.1    0.05       0  4848.1    0.16       0  4850.6    0.07       0
  4856.6    0.16       0  4865.3    0.07       0  5101.8    0.05       0
Bank Sta=4850.6,4856.6
Exp/Cntr=0.3,0.1

Type RM Length L Ch R = 1,3250,256,256,256
BEGIN DESCRIPTION:
Mapping XS 4c7424cd
END DESCRIPTION:
XS GIS Cut Line= 5
      3618992.58     10277199.82      3618621.04     10276852.58
      3618548.12     10276717.17      3618471.74     10276665.08
      3617558.56     10276692.86
#Sta/Elev= 30
  4300.4  305.59  4384.2  303.70  4639.1  294.49  4759.3  291.04  4787.7  292.50
  4854.6  291.67  4860.3  292.28  4876.5  291.25  4882.2  292.24  4898.4  290.88
  4904.1  291.97  4920.3  290.57  4926.0  291.47  4942.2  289.97  4946.3  290.99
  4962.7  289.94  4970.0  291.04  4986.0  291.25  5050.6  291.57  5053.8  290.51
  5100.2  289.38  5102.9  288.88  5106.2  289.38  5108.2  290.64  5204.9  289.57
  5314.9  292.73  5515.0  296.71  5762.2  296.27  5865.2  297.83  5968.8  298.10
#Mann=5,-1,0
  4300.4    0.05       0  4946.3    0.07       0  4986.0    0.05       0
  5100.2    0.03       0  5106.2    0.05       0
Bank Sta=5100.2,5106.2
Exp/Cntr=0.3,0.1

Type RM Length L Ch R = 1,2994,230,230,230
BEGIN DESCRIPTION:
Mapping XS 277d2240
END DESCRIPTION:
XS GIS Cut Line= 4
      3619055.05     10277099.08      3618770.35     10276543.56
      3618478.68     10276411.61      3617595.17     10276435.86
#Sta/Elev= 30
  4226.6  305.30  4336.7  303.70  4375.5  303.66  4426.0  302.07  4470.9  301.46
  4511.3  300.52  4582.0  299.20  4650.7  297.44  4740.6  294.33  4872.0  288.67
  4903.8  288.57  4912.7  288.04  4932.8  283.28  4935.6  282.78  4938.8  283.28
  4993.0  283.73  5090.9  283.68  5101.3  283.92  5108.5  284.59  5137.1  284.60
  5237.6  287.13  5353.5  290.86  5427.6  292.36  5517.7  292.44  5567.7  293.04
  5637.7  292.75  5697.7  293.28  5787.8  292.43  5837.8  293.07  6054.8  293.18
#Mann=5,-1,0
  4226.6    0.05       0  4511.3    0.16       0  4582.0    0.05       0
  4932.8    0.03       0  4938.8    0.05       0
Bank Sta=4932.8,4938.8
Exp/Cntr=0.3,0.1

Type RM Length L Ch R = 1,2764,154,154,154
BEGIN DESCRIPTION:
Mapping XS c0a5bbb7
END DESCRIPTION:
XS GIS Cut Line= 4
      3619159.24     10276797.04      3618912.71     10276380.36
      3618596.74     10276217.17      3617662.66     10276144.25
#Sta/Elev= 30
  4259.0  300.90  4341.3  299.08  4384.2  298.69  4399.8  297.43  4427.9  297.74
  4479.7  296.71  4495.4  295.81  4538.2  294.97  4665.5  291.05  4712.8  289.27
  4766.3  288.04  4778.1  287.11  4794.7  286.60  4822.6  283.91  4867.6  283.61
  4890.1  284.03  4909.7  283.45  4912.4  282.95  4915.7  283.45  5143.5  284.14
  5173.6  283.84  5203.7  285.96  5354.2  289.17  5360.8  289.17  5365.9  288.62
  5655.1  290.41  5755.4  289.58  5895.8  289.52  5976.1  288.14  6035.7  288.71
#Mann=5,-1,0
  4259.0    0.16       0  4665.5     0.1       0  4712.8    0.05       0
  4909.7    0.03       0  4915.7    0.05       0
Bank Sta=4909.7,4915.7
Exp/Cntr=0.3,0.1

Type RM Length L Ch R = 1,2610,88,88,88
BEGIN DESCRIPTION:
Mapping XS 14016f3a
END DESCRIPTION:
XS GIS Cut Line= 6
      3619360.61     10276637.29      3618873.65     10276198.20
      3618786.84     10276139.61      3618693.53     10276102.72
      3618606.72     10276096.20      3617736.33     10276015.84
#Sta/Elev= 30
  4214.9  298.51  4246.1  297.65  4380.7  296.59  4394.9  297.47  4486.8  295.73
  4526.5  294.00  4592.9  292.70  4724.5  288.28  4852.2  283.92  4855.0  283.42
  4858.2  283.92  4884.5  285.41  4926.9  283.98  4932.9  284.58  4941.8  283.98
  4969.0  284.67  5014.3  284.01  5062.2  285.64  5068.4  284.90  5107.2  286.08
  5147.3  286.57  5151.9  286.02  5162.5  284.85  5177.4  284.36  5338.1  288.08
  5559.0  289.64  5669.5  289.68  5880.4  287.95  6010.9  288.33  6036.8  287.27
#Mann=7,-1,0
  4214.9    0.16       0  4526.5     0.1       0  4724.5    0.05       0
  4852.2    0.03       0  4858.2    0.05       0  5062.2    0.16       0
  5151.9    0.05       0
Bank Sta=4852.2,4858.2
Exp/Cntr=0.3,0.1

Type RM Length L Ch R = 1,2522,309,309,309
BEGIN DESCRIPTION:
UNT997 IN WICK 4.0
END DESCRIPTION:
XS GIS Cut Line= 3
      3619294.62     10276342.14      3619041.18     10276130.36
      3618371.08     10275915.10
#Sta/Elev= 30
  4427.9  294.33  4564.6  291.11  4593.2  289.89  4619.9  289.77  4650.5  289.17
  4793.5  284.24  4820.2  283.35  4830.6  283.89  4835.8  283.32  4841.2  284.14
  4851.7  282.84  4873.2  281.37  4905.3  280.32  4932.2  277.24  4937.4  277.63
  4964.3  275.58  4998.6  274.19  5001.4  273.69  5004.6  274.19  5028.5  275.70
  5033.7  275.22  5040.8  275.62  5092.3  279.93  5114.3  281.65  5187.8  283.91
  5240.4  286.55  5263.7  286.86  5313.9  288.90  5408.4  288.29  5462.0  288.80
#Mann=6,-1,0
  4427.9    0.16       0  4619.9     0.1       0  4793.5    0.05       0
  4998.6    0.03       0  5004.6    0.05       0  5092.3    0.05       0
Bank Sta=4998.6,5004.6
Exp/Cntr=0.3,0.1

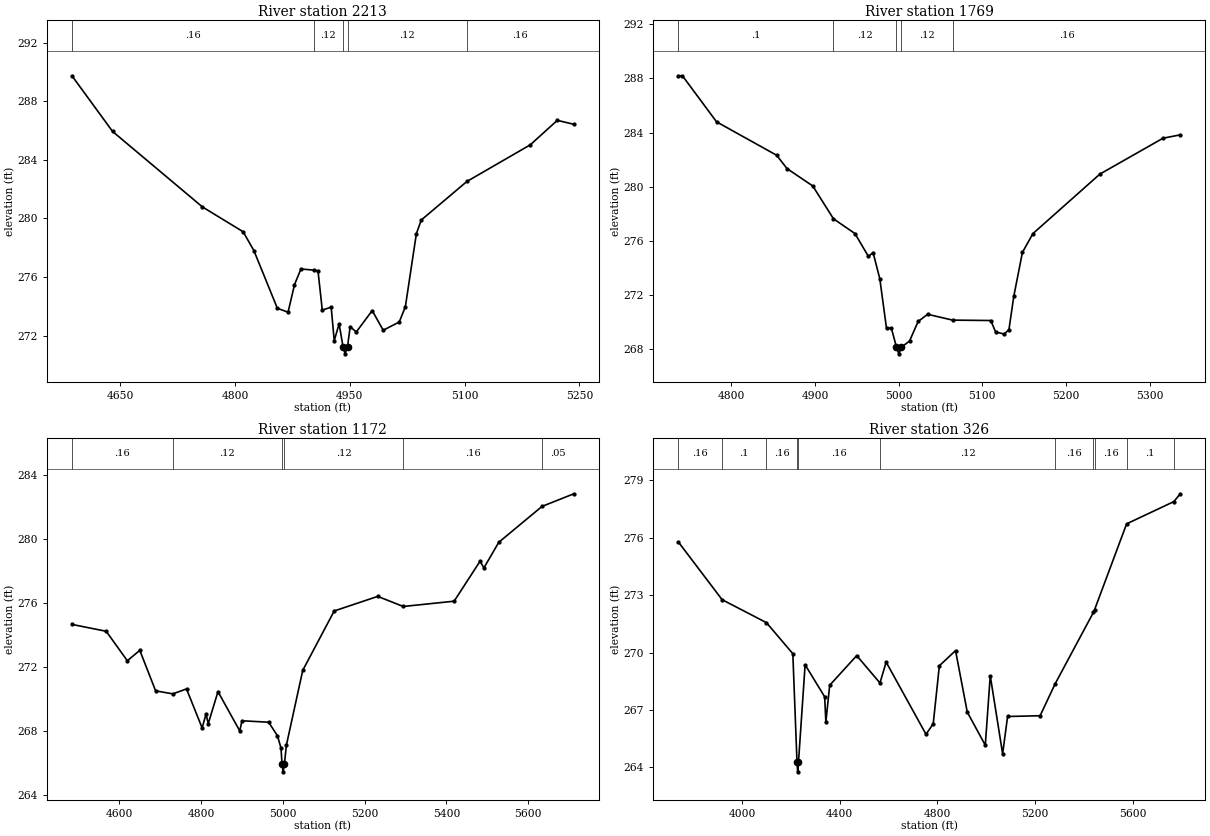
Type RM Length L Ch R = 1,2213,444,444,444
BEGIN DESCRIPTION:
UNT997 IN WICK 3.0
END DESCRIPTION:
XS GIS Cut Line= 3
      3619242.10     10276041.64      3618942.11     10275891.64
      3618742.08     10275641.62
#Sta/Elev= 30
  4587.1  289.73  4640.2  285.93  4757.6  280.78  4810.7  279.09  4824.7  277.81
  4855.4  273.87  4869.4  273.60  4877.8  275.48  4886.2  276.55  4903.1  276.47
  4908.5  276.42  4914.1  273.74  4925.7  273.95  4929.7  271.66  4936.1  272.81
  4941.1  271.26  4943.9  270.76  4947.1  271.26  4950.5  272.61  4958.5  272.25
  4979.3  273.71  4993.7  272.37  5014.6  272.93  5022.6  273.97  5037.0  278.96
  5043.4  279.89  5103.0  282.52  5185.8  285.02  5221.1  286.69  5242.7  286.42
#Mann=5,-1,0
  4587.1    0.16       0  4903.1    0.12       0  4941.1    0.07       0
  4947.1    0.12       0  5103.0    0.16       0
Bank Sta=4941.1,4947.1
Exp/Cntr=0.3,0.1

Type RM Length L Ch R = 1,1769,597,597,597
BEGIN DESCRIPTION:
UNT997 IN WICK 2.0
END DESCRIPTION:
XS GIS Cut Line= 3
      3619315.95     10275876.10      3619289.90     10275761.51
      3618868.04     10275527.14
#Sta/Elev= 30
  4736.6  288.19  4741.4  288.19  4782.2  284.79  4854.1  282.32  4866.4  281.34
  4897.3  280.05  4922.0  277.63  4947.7  276.54  4963.7  274.86  4969.4  275.13
  4977.4  273.20  4985.4  269.54  4991.1  269.58  4997.3  268.16  5000.1  267.66
  5003.3  268.16  5012.9  268.60  5023.2  270.05  5034.6  270.58  5064.4  270.15
  5110.1  270.12  5115.8  269.28  5126.1  269.12  5131.8  269.45  5137.6  271.91
  5147.9  275.15  5160.5  276.54  5240.5  280.93  5316.0  283.58  5336.7  283.83
#Mann=5,-1,0
  4736.6     0.1       0  4922.0    0.12       0  4997.3    0.07       0
  5003.3    0.12       0  5064.4    0.16       0
Bank Sta=4997.3,5003.3
Exp/Cntr=0.3,0.1

Type RM Length L Ch R = 1,1172,846,846,846
BEGIN DESCRIPTION:
Mapping XS 5b33a953
END DESCRIPTION:
XS GIS Cut Line= 4
      3619582.04     10275552.43      3619472.66     10275312.85
      3618863.29     10275059.37      3618608.06     10275222.58
#Sta/Elev= 30
  4484.9  274.64  4568.6  274.21  4620.2  272.37  4650.7  273.02  4689.3  270.49
  4731.4  270.30  4764.8  270.61  4803.0  268.17  4812.5  269.04  4817.9  268.44
  4841.7  270.44  4894.8  267.99  4900.5  268.62  4965.5  268.53  4987.1  267.68
  4995.7  266.91  4998.1  265.93  5000.8  265.43  5004.1  265.93  5008.8  267.09
  5048.8  271.77  5125.7  275.48  5232.0  276.39  5294.4  275.76  5418.7  276.09
  5482.1  278.59  5491.4  278.17  5527.8  279.77  5633.4  282.01  5711.2  282.80
#Mann=6,-1,0
  4484.9    0.16       0  4731.4    0.12       0  4998.1   0.035       0
  5004.1    0.12       0  5294.4    0.16       0  5633.4    0.05       0
Bank Sta=4998.1,5004.1
Exp/Cntr=0.3,0.1

Type RM Length L Ch R = 1,326,0,0,0
BEGIN DESCRIPTION:
UNT997 IN WICK 1.0
END DESCRIPTION:
XS GIS Cut Line= 4
      3619733.02     10275637.34      3619652.30     10274903.00
      3618722.61     10274741.55      3618477.84     10275022.78
#Sta/Elev= 30
  3739.3  275.77  3918.2  272.76  4099.8  271.56  4207.8  269.94  4224.9  264.27
  4227.7  263.77  4230.9  264.27  4258.1  269.36  4338.1  267.69  4343.1  266.37
  4358.7  268.29  4469.4  269.84  4564.6  268.41  4589.9  269.50  4753.2  265.73
  4782.7  266.28  4807.8  269.31  4874.1  270.10  4922.1  266.89  4995.9  265.16
  5016.2  268.79  5066.9  264.71  5087.2  266.66  5220.4  266.70  5281.6  268.36
  5438.8  272.10  5443.2  272.23  5574.6  276.72  5767.8  277.88  5794.5  278.29
#Mann=11,-1,0
  3739.3    0.16       0  3918.2     0.1       0  4099.8    0.16       0
  4224.9    0.07       0  4230.9    0.16       0  4564.6    0.12       0
  5281.6    0.16       0  5438.8     0.1       0  5443.2    0.16       0
  5574.6     0.1       0  5767.8    0.05       0
Bank Sta=4224.9,4230.9
Exp/Cntr=0.3,0.1

Chan Stop Cuts=-1