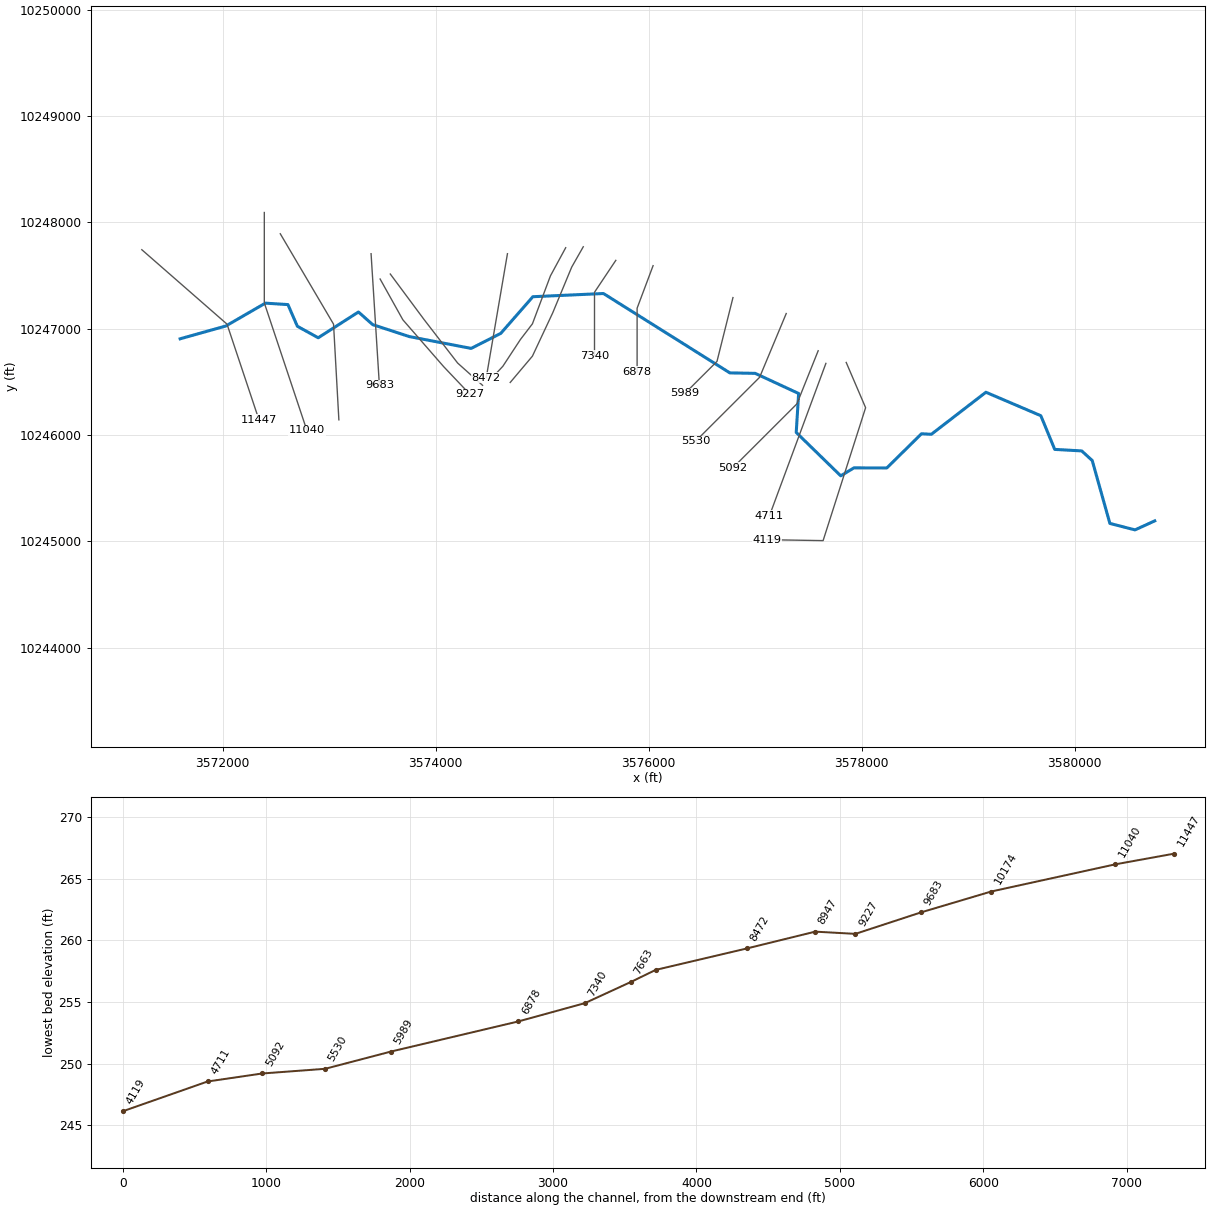
--- WICKSONCREEKTRIB.prj (project) ---

Proj Title=WICKSON CREEK TRIB 13
Current Plan=p01
Default Exp/Contr=0.3,0.1
English Units
Geom File=g01
Flow File=f01
Plan File=p01
Y Axis Title=Elevation
X Axis Title(PF)=Main Channel Distance
X Axis Title(XS)=Station
BEGIN DESCRIPTION:
UNT05237 IN WICK
END DESCRIPTION:
DSS Export Rating Curves= 0
DSS Export Rating Curve Sorted= 0
DSS Export Volume Flow Curves= 0
DXF OffsetX= 0
DXF OffsetY= 0
DXF ScaleX= 1
DXF ScaleY= 10

--- WICKSONCREEKTRIB.p01 (plan) ---

Plan Title=Multiple Run
Short Identifier=Multiple
Geom File=g01
Flow File=f01
Subcritical Flow
K Sum by GR= 0
Std Step Tol= 0.01
Critical Tol= 0.01
Num of Std Step Trials= 20
Max Error Tol= 0.3
Flow Tol Ratio= 0.001
Split Flow NTrial= 30
Split Flow Tol= 0.02
Split Flow Ratio= 0.02
Log Output Level= 0
Friction Slope Method= 1
Unsteady Friction Slope Method= 2
Unsteady Bridges Friction Slope Method= 1
Parabolic Critical Depth
Global Vel Dist=  1 , 1 , 1
Global Log Level= 0
CheckData=True
Encroach Param= -1, 0, 0, 0
BEGIN DESCRIPTION:
Multiple Run
END DESCRIPTION:

--- WICKSONCREEKTRIB.f01 (steady flow) ---

Flow Title=Multiple
Program Version=4.10
Number of Profiles= 7
Profile Names=10-year,25-year,50-year,1pct_min,100-year,1pct_plu,500-year
River Rch & RM=UNT05237 IN WICK,Reach-1         ,11447
     395     513     605     523     707     957     968
River Rch & RM=WICKSONCRTR13,Reach-1         ,11447
     395     513     605     523     707     957     968
Boundary for River Rch & Prof#=WICKSONCRTR13,Reach-1         , 1
Up Type= 0
Dn Type= 3
Dn Slope=0.005
Boundary for River Rch & Prof#=WICKSONCRTR13,Reach-1         , 2
Up Type= 0
Dn Type= 3
Dn Slope=0.005
Boundary for River Rch & Prof#=WICKSONCRTR13,Reach-1         , 3
Up Type= 0
Dn Type= 3
Dn Slope=0.005
Boundary for River Rch & Prof#=WICKSONCRTR13,Reach-1         , 4
Up Type= 0
Dn Type= 3
Dn Slope=0.005
Boundary for River Rch & Prof#=WICKSONCRTR13,Reach-1         , 5
Up Type= 0
Dn Type= 3
Dn Slope=0.005
Boundary for River Rch & Prof#=WICKSONCRTR13,Reach-1         , 6
Up Type= 0
Dn Type= 3
Dn Slope=0.005
Boundary for River Rch & Prof#=WICKSONCRTR13,Reach-1         , 7
Up Type= 0
Dn Type= 3
Dn Slope=0.005
DSS Import GetInterval= 0
DSS Import GetPeak= 0
DSS Import FillOption= 0

--- WICKSONCREEKTRIB.g01 (geometry) ---

Geom Title=Existing Conditions
Program Version=4.10

River Reach=WICKSONCRTR13   ,Reach-1
Reach XY= 30
      3571602.08     10246903.83      3572030.96     10247024.41
      3572401.89     10247239.08       3572613.9      10247225.6
      3572702.54     10247021.73       3572898.1     10246913.58
      3573276.07     10247156.02      3573409.32     10247037.29
      3573753.42     10246924.82      3574334.34     10246813.56
      3574612.12     10246955.05      3574913.34     10247299.67
       3575576.3     10247329.69      3576762.78     10246583.26
      3577000.95      10246578.9      3577408.56     10246389.51
      3577385.91     10246023.19      3577803.74     10245615.09
      3577927.68     10245689.99      3578236.55     10245689.41
       3578561.9     10246010.65      3578654.93       10246006.
      3579166.68     10246401.29      3579682.43     10246180.63
      3579812.87     10245863.78      3580066.42     10245849.53
      3580165.08     10245758.91      3580330.54     10245167.79
      3580566.62     10245106.86      3580752.11     10245191.64

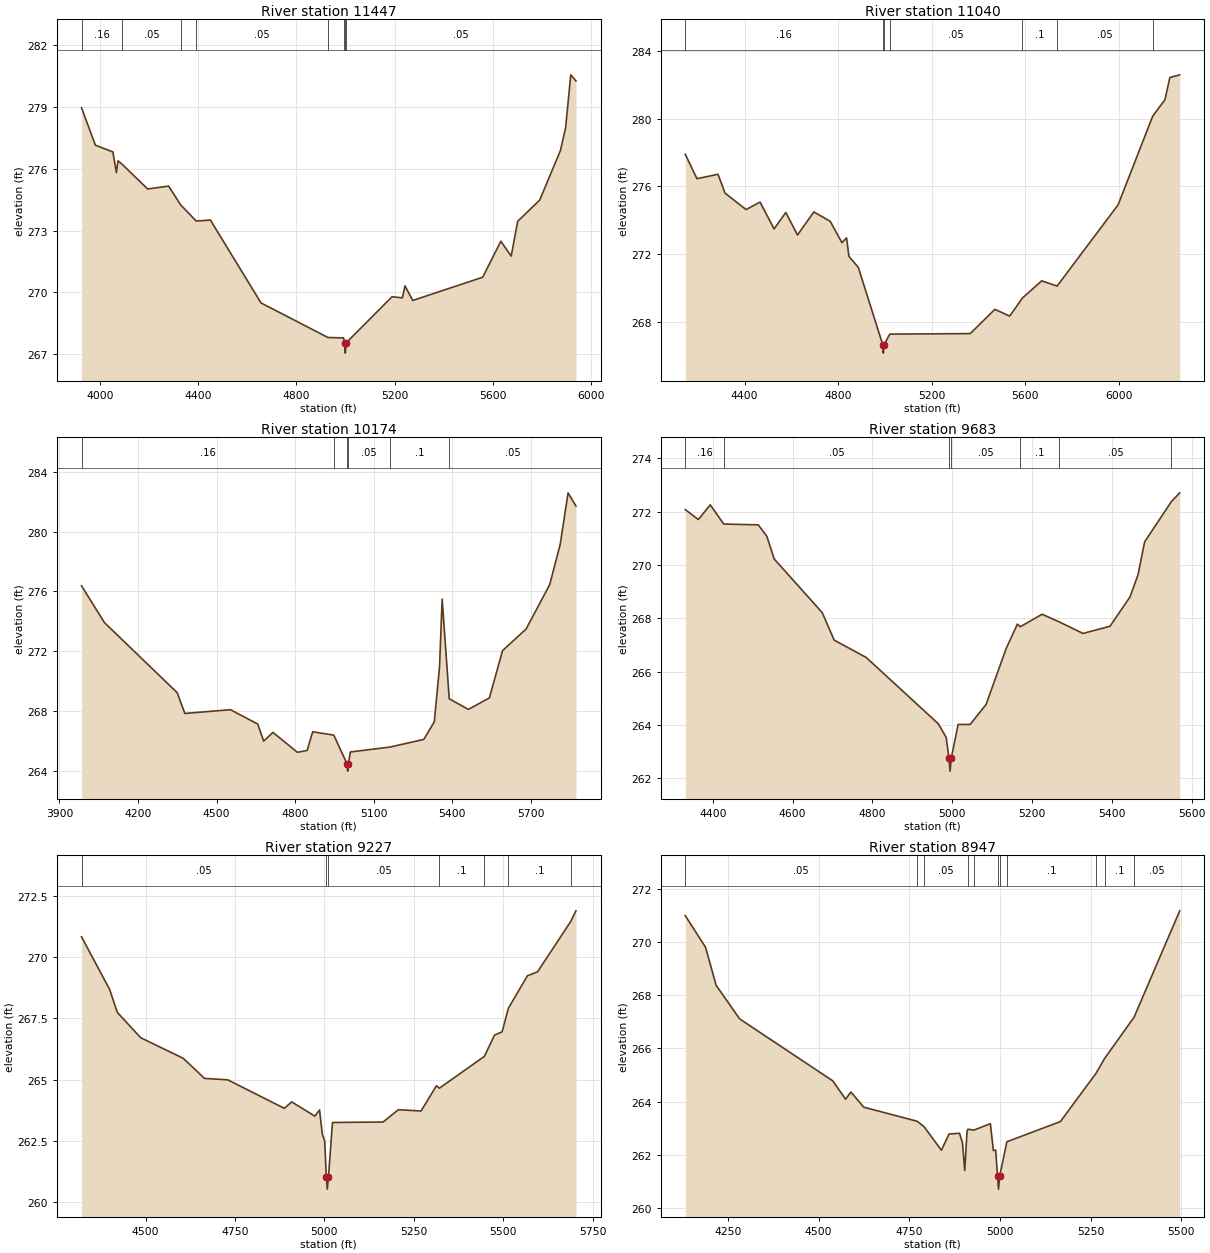
Type RM Length L Ch R = 1 ,11447   ,407,407,407
BEGIN DESCRIPTION:
UNT05237 IN WICK 17.0
END DESCRIPTION:
XS GIS Cut Line= 3
      3571242.08     10247741.66      3572042.11     10247041.64
       3572342.1     10246141.67
#Sta/Elev= 30
  3925.8  278.97  3982.3  277.15  4053.5  276.82  4067.7  275.82  4074.4  276.39
  4091.3  276.22  4194.9  275.02  4280.3  275.16    4329  274.25  4392.5  273.46
  4450.2  273.51  4656.2  269.48  4928.5   267.8  4991.9  267.78  4996.4  267.54
  4999.1  267.04  5002.4  267.54  5189.1  269.78  5231.3  269.73  5241.8  270.31
  5273.5   269.6  5558.1  270.73  5631.8  272.48    5674  271.76  5700.4  273.45
    5790  274.48  5874.3  276.89  5895.4     278  5916.4  280.57  5937.5  280.27
#Mann= 8 ,-1 , 0
  3925.8     .16       0  4091.3     .05       0    4329     .16       0
  4392.5     .05       0  4928.5     .16       0  4991.9     .05       0
  4996.4     .03       0  5002.4     .05       0
Bank Sta=4996.4,5002.4
XS Rating Curve= 0 ,0
Exp/Cntr=0.3,0.1

Type RM Length L Ch R = 1 ,11040   ,866,866,866
BEGIN DESCRIPTION:
UNT05237 IN WICK 16.0
END DESCRIPTION:
XS GIS Cut Line= 3
      3572392.11     10248091.61      3572392.11     10247241.64
      3572792.11     10246041.62
#Sta/Elev= 30
  4146.5   277.9  4196.5  276.46  4286.5  276.72  4316.5  275.61  4406.5  274.64
  4466.5  275.08  4526.5   273.5  4576.5  274.47  4626.5  273.14  4696.5   274.5
  4766.5  273.95  4816.5  272.69  4836.5  272.97  4846.5  271.88  4886.5  271.24
    4991  266.68  4993.7  266.18    4997  266.68  5021.3   267.3  5365.4  267.33
  5470.8  268.76  5534.1  268.36  5588.8  269.43  5671.1  270.44  5736.8  270.13
  5997.9  274.92  6145.7  280.14  6198.1  281.11  6219.2  282.42  6261.4  282.58
#Mann= 7 ,-1 , 0
  4146.5     .16       0    4991     .07       0    4997     .16       0
  5021.3     .05       0  5588.8      .1       0  5736.8     .05       0
  6145.7      .1       0
Bank Sta=4991,4997
XS Rating Curve= 0 ,0
Exp/Cntr=0.3,0.1

Type RM Length L Ch R = 1 ,10174   ,491,491,491
BEGIN DESCRIPTION:
UNT05237 IN WICK 15.0
END DESCRIPTION:
XS GIS Cut Line= 3
      3572542.08     10247891.68      3573042.11     10247041.64
      3573092.11     10246141.63
#Sta/Elev= 30
  3984.2  276.37  4072.1   273.9  4349.4  269.22  4378.7  267.83  4552.7  268.08
  4657.1  267.12  4679.5  265.98  4715.2  266.56  4808.3  265.23  4845.4  265.35
  4866.8   266.6  4947.3  266.38  4997.4  264.47  5000.2  263.97  5003.4  264.47
  5010.5  265.25  5161.5  265.58  5290.9  266.09    5331  267.27    5351  270.95
    5361  275.48    5388  268.81  5461.2   268.1  5541.3  268.87  5591.4  272.03
  5681.5  273.48  5771.6  276.45  5811.7  279.15  5841.7  282.59  5871.8   281.7
#Mann= 6 ,-1 , 0
  3984.2     .16       0  4947.3     .05       0  4997.4     .03       0
  5003.4     .05       0  5161.5      .1       0    5388     .05       0
Bank Sta=4997.4,5003.4
XS Rating Curve= 0 ,0
Exp/Cntr=0.3,0.1

Type RM Length L Ch R = 1 ,9683    ,456,456,456
BEGIN DESCRIPTION:
UNT05237 IN WICK 14.0
END DESCRIPTION:
XS GIS Cut Line= 2
      3573394.43     10247704.24      3573472.55     10246467.31
#Sta/Elev= 30
  4330.8  272.07  4363.5   271.7  4393.5  272.25  4427.2  271.53  4513.8   271.5
  4535.3  271.07  4553.8  270.22  4674.1  268.21  4704.1  267.18  4784.3  266.53
  4964.7  264.05  4984.7  263.54  4991.7  262.77  4994.5  262.27  4997.7  262.77
  5014.8  264.02  5044.8  264.02  5084.9  264.77    5135  266.86  5163.3  267.78
  5170.4  267.68  5225.2  268.15  5268.6  267.86  5327.8  267.43  5395.5   267.7
  5445.6   268.8  5465.7  269.63  5482.2  270.86  5549.2  272.37  5570.2   272.7
#Mann= 7 ,-1 , 0
  4330.8     .16       0  4427.2     .05       0  4991.7    .035       0
  4997.7     .05       0  5170.4      .1       0  5268.6     .05       0
  5549.2      .1       0
Bank Sta=4991.7,4997.7
XS Rating Curve= 0 ,0
Exp/Cntr=0.3,0.1

Type RM Length L Ch R = 1 ,9227    ,280,280,280
BEGIN DESCRIPTION:
Mapping XS acd42e82
END DESCRIPTION:
XS GIS Cut Line= 4
      3573479.38      10247466.2      3573692.95     10247082.48
      3574074.89     10246643.25      3574323.17     10246381.07
#Sta/Elev= 30
  4320.9  270.83  4399.5  268.68  4421.2  267.74  4486.4  266.71  4605.3  265.87
  4664.8  265.05  4729.9  264.99  4887.7  263.83  4908.5  264.09  4973.2  263.51
  4986.4  263.76    4994  262.78  5000.7   262.5  5005.3  261.03    5008  260.53
  5011.3  261.03  5022.5  263.25    5164  263.27  5206.7  263.77  5270.3  263.72
  5313.1  264.75  5321.4  264.65  5447.2  265.95  5475.7  266.82  5496.7  266.95
  5514.2  267.91  5567.5  269.24  5595.8   269.4  5688.3  271.45  5703.2  271.89
#Mann= 7 ,-1 , 0
  4320.9     .05       0  5005.3    .035       0  5011.3     .05       0
  5321.4      .1       0  5447.2     .05       0  5514.2      .1       0
  5688.3     .05       0
Bank Sta=5005.3,5011.3
XS Rating Curve= 0 ,0
Exp/Cntr=0.3,0.1

Type RM Length L Ch R = 1 ,8947    ,475,475,475
BEGIN DESCRIPTION:
UNT05237 IN WICK 13.0
END DESCRIPTION:
XS GIS Cut Line= 4
      3573574.92       10247513.       3573892.6     10247084.22
      3574206.84     10246676.23      3574440.95      10246466.4
#Sta/Elev= 30
  4132.4  270.99  4188.3   269.8  4217.5  268.37  4282.2  267.11  4538.9  264.78
  4574.4  264.09    4589  264.36  4624.5  263.79  4771.8  263.26  4791.1  263.05
  4838.5  262.17  4859.3  262.78  4888.3  262.81  4896.5  262.46  4902.8  261.41
  4909.1  262.88  4911.5  262.96  4928.5  262.93  4973.5  263.17  4981.7  262.16
    4988  262.18  4993.2  261.21  4995.9  260.71  4999.2  261.21  5018.9  262.49
  5166.5  263.25  5264.1  265.05  5288.3  265.62  5369.5  267.17  5495.4  271.17
#Mann= 11 ,-1 , 0
  4132.4     .05       0  4771.8      .1       0  4791.1     .05       0
  4911.5      .1       0  4928.5     .05       0  4993.2     .03       0
  4999.2     .05       0  5018.9      .1       0  5264.1     .05       0
  5288.3      .1       0  5369.5     .05       0
Bank Sta=4993.2,4999.2
XS Rating Curve= 0 ,0
Exp/Cntr=0.3,0.1

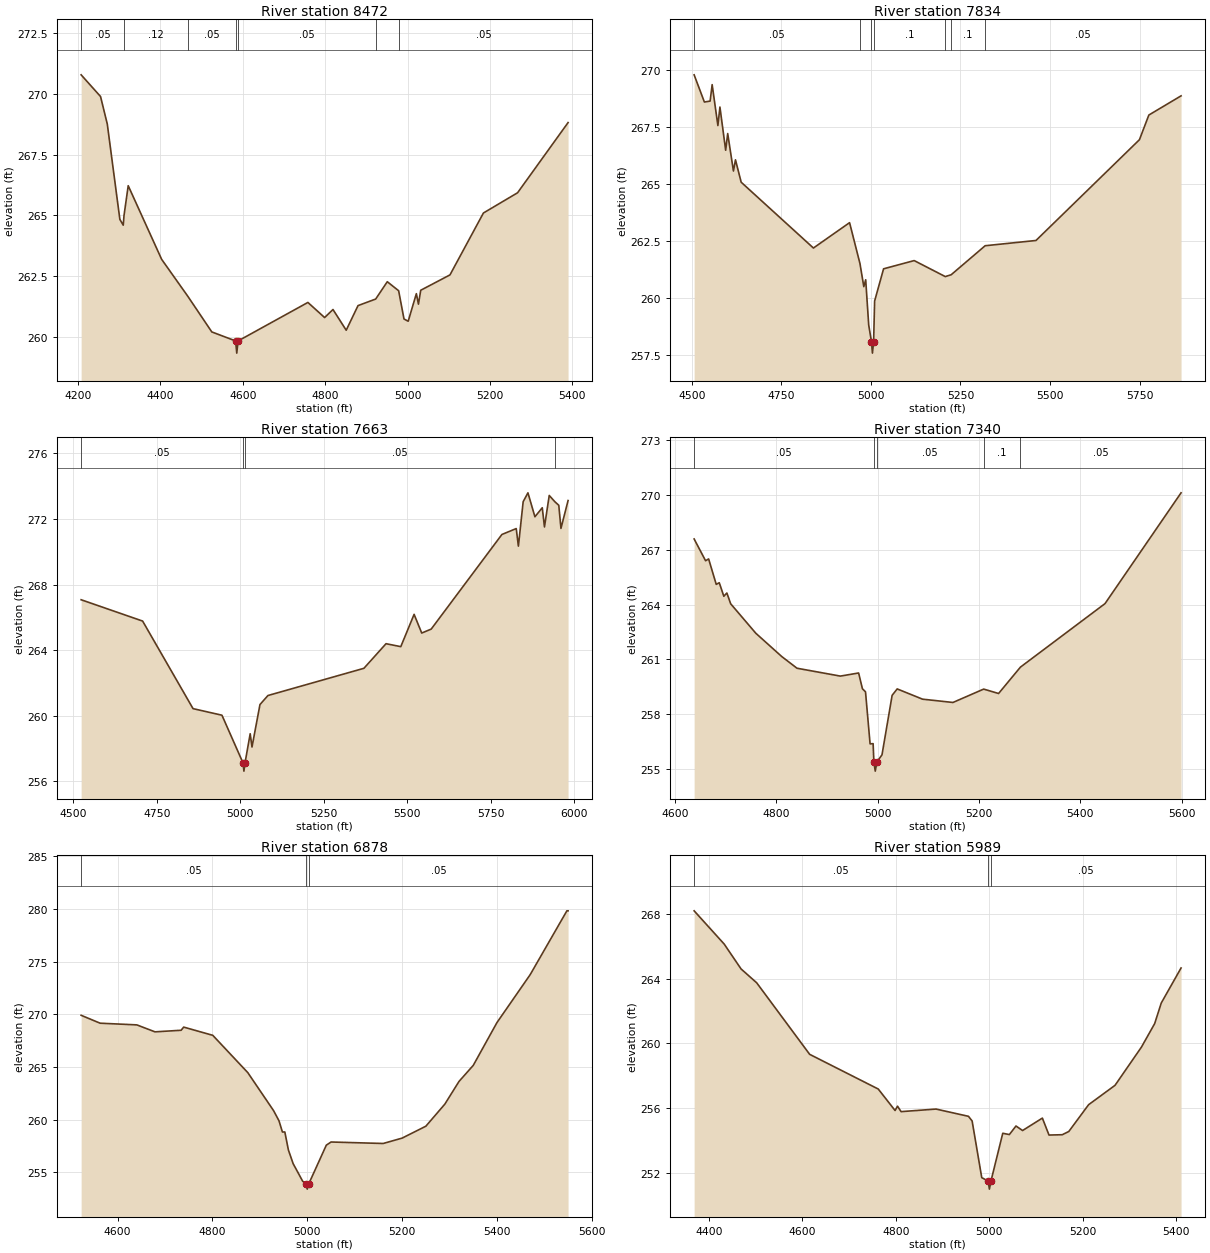
Type RM Length L Ch R = 1 ,8472    ,638,638,638
BEGIN DESCRIPTION:
UNT05237 IN WICK 12.0
END DESCRIPTION:
XS GIS Cut Line= 2
      3574674.82     10247704.28      3574475.93     10246539.04
#Sta/Elev= 30
  4207.7  270.77  4254.8  269.88  4271.2  268.75  4301.7  264.84  4309.9   264.6
  4311.8     265    4322  266.22  4403.1   263.2  4466.8  261.68  4524.9  260.22
  4582.7  259.85  4585.5  259.35  4588.7  259.85  4758.2  261.43  4798.8  260.81
  4819.1  261.14  4851.2  260.29  4879.9   261.3  4922.8  261.57  4950.9  262.28
  4978.5  261.91  4991.5  260.75  5001.7  260.66  5021.5  261.79  5026.6  261.36
  5032.1  261.93  5103.1  262.56  5184.3   265.1  5267.2  265.93  5389.8  268.81
#Mann= 7 ,-1 , 0
  4207.7     .05       0  4311.8     .12       0  4466.8     .05       0
  4582.7     .03       0  4588.7     .05       0  4922.8      .1       0
  4978.5     .05       0
Bank Sta=4582.7,4588.7
XS Rating Curve= 0 ,0
Exp/Cntr=0.3,0.1

Type RM Length L Ch R = 1 ,7834    ,171,171,171
BEGIN DESCRIPTION:
UNT05237 IN WICK 11.0
END DESCRIPTION:
XS GIS Cut Line= 6
      3575221.67     10247760.64      3575078.46     10247495.91
      3574909.19     10247044.52      3574796.34     10246896.95
      3574631.41     10246645.22      3574570.66     10246580.13
#Sta/Elev= 30
  4506.8  269.78  4535.4  268.59  4551.4  268.63  4557.1  269.35  4573.1  267.56
  4578.8  268.37  4594.8  266.48  4600.5  267.21  4616.5  265.57  4622.2  266.06
  4638.1  265.08  4839.7   262.2  4940.6  263.31  4969.6  261.52  4980.3  260.51
  4985.6  260.81    4994  258.83  5001.7   258.1  5004.4   257.6  5007.7   258.1
  5010.5  259.88  5035.5  261.29  5120.9  261.65  5207.7  260.95  5224.1  261.03
    5319   262.3  5460.8  262.53  5749.5  266.94  5775.8  268.02  5865.7  268.86
#Mann= 7 ,-1 , 0
  4506.8     .05       0  4969.6      .1       0  5001.7     .07       0
  5007.7      .1       0  5207.7     .05       0  5224.1      .1       0
    5319     .05       0
Bank Sta=5001.7,5007.7
XS Rating Curve= 0 ,0
Exp/Cntr=0.3,0.1

Type RM Length L Ch R = 1 ,7663    ,323,323,323
BEGIN DESCRIPTION:
UNT05237 IN WICK 10.0
END DESCRIPTION:
XS GIS Cut Line= 5
      3575386.62     10247769.36      3575278.11     10247578.38
      3575100.16     10247148.69      3574909.19      10246740.7
      3574700.88     10246493.33
#Sta/Elev= 30
  4523.1  267.08  4707.3  265.78  4858.3  260.44  4944.9  260.04    5008  257.13
  5010.7  256.63    5014  257.13  5029.5  258.91  5034.9   258.1  5058.8  260.69
  5082.7  261.24  5370.2   262.9  5436.4   264.4  5480.6  264.22  5520.5  266.19
  5543.3  265.05  5571.7  265.29  5783.5  271.06  5826.4  271.42  5832.9  270.35
  5847.2  273.06  5861.5   273.6  5882.4  272.14  5904.4  272.69    5911  271.52
  5925.3  273.44    5942  273.06  5953.9  272.84  5960.4  271.43  5981.7  273.13
#Mann= 4 ,-1 , 0
  4523.1     .05       0    5008     .04       0    5014     .05       0
    5942      .1       0
Bank Sta=5008,5014
XS Rating Curve= 0 ,0
Exp/Cntr=0.3,0.1

Type RM Length L Ch R = 1 ,7340    ,462,462,462
BEGIN DESCRIPTION:
UNT05237 IN WICK 9.0
END DESCRIPTION:
XS GIS Cut Line= 3
      3575692.13     10247641.67      3575492.11     10247341.64
      3575492.11     10246741.64
#Sta/Elev= 30
  4638.1  267.58  4660.7  266.39  4666.7  266.49  4681.7   265.1  4687.7  265.19
  4696.7  264.45  4702.7  264.63  4710.2  264.04  4759.8  262.43  4810.9  261.16
    4841  260.52  4926.6  260.09  4962.6  260.26  4970.1   259.4  4976.2  259.23
  4985.2  256.39  4991.2   256.4  4992.7   255.4  4995.4   254.9  4998.7   255.4
  5008.7  255.79  5028.7  259.04  5038.7  259.39  5088.7  258.83  5148.7  258.65
  5209.3  259.38  5238.7  259.14  5281.8  260.58  5448.7  264.05  5598.7   270.1
#Mann= 5 ,-1 , 0
  4638.1     .05       0  4992.7     .03       0  4998.7     .05       0
  5209.3      .1       0  5281.8     .05       0
Bank Sta=4992.7,4998.7
XS Rating Curve= 0 ,0
Exp/Cntr=0.3,0.1

Type RM Length L Ch R = 1 ,6878    ,889,889,889
BEGIN DESCRIPTION:
UNT05237 IN WICK 8.0
END DESCRIPTION:
XS GIS Cut Line= 3
      3576042.12     10247591.68      3575892.11     10247191.64
      3575892.11     10246591.68
#Sta/Elev= 30
  4522.9  269.91    4563  269.16  4640.4     269  4678.7  268.34  4733.9  268.49
  4739.2  268.79  4800.6  268.01  4874.5  264.47  4928.8  260.87  4940.3   259.9
  4947.5  258.84  4952.6  258.84  4960.1  257.14  4970.1  255.84  4990.1  254.18
  4997.1  253.92  4999.9  253.42  5003.1  253.92  5040.1  257.59  5050.1  257.89
  5160.1  257.75  5200.1  258.26  5250.1  259.39  5290.1  261.48  5320.1  263.64
  5350.1  265.16  5400.1  269.22  5470.1  273.76  5547.6  279.82  5550.1  279.82
#Mann= 3 ,-1 , 0
  4522.9     .05       0  4997.1     .03       0  5003.1     .05       0
Bank Sta=4997.1,5003.1
XS Rating Curve= 0 ,0
Exp/Cntr=0.3,0.1

Type RM Length L Ch R = 1 ,5989    ,459,459,459
BEGIN DESCRIPTION:
UNT05237 IN WICK 6.0
END DESCRIPTION:
XS GIS Cut Line= 3
       3576792.1     10247291.63      3576642.11     10246691.64
      3576342.11     10246391.65
#Sta/Elev= 30
  4368.2  268.21  4432.6  266.15  4468.7  264.61  4502.2  263.75  4615.6  259.32
  4762.5  257.17  4798.5  255.84  4803.7  256.11  4811.4  255.77  4886.1  255.93
  4955.7  255.48  4963.5  255.19  4984.1  251.68  4997.8  251.47  5000.5  250.97
  5003.8  251.47  5029.1  254.43  5043.2  254.35  5057.4  254.88  5071.5   254.6
  5113.9  255.37  5128.1  254.32  5156.4  254.34  5170.5  254.54  5212.9   256.2
  5269.5   257.4  5326.1  259.77  5354.3  261.22  5368.5   262.5  5410.9  264.67
#Mann= 3 ,-1 , 0
  4368.2     .05       0  4997.8     .03       0  5003.8     .05       0
Bank Sta=4997.8,5003.8
XS Rating Curve= 0 ,0
Exp/Cntr=0.3,0.1

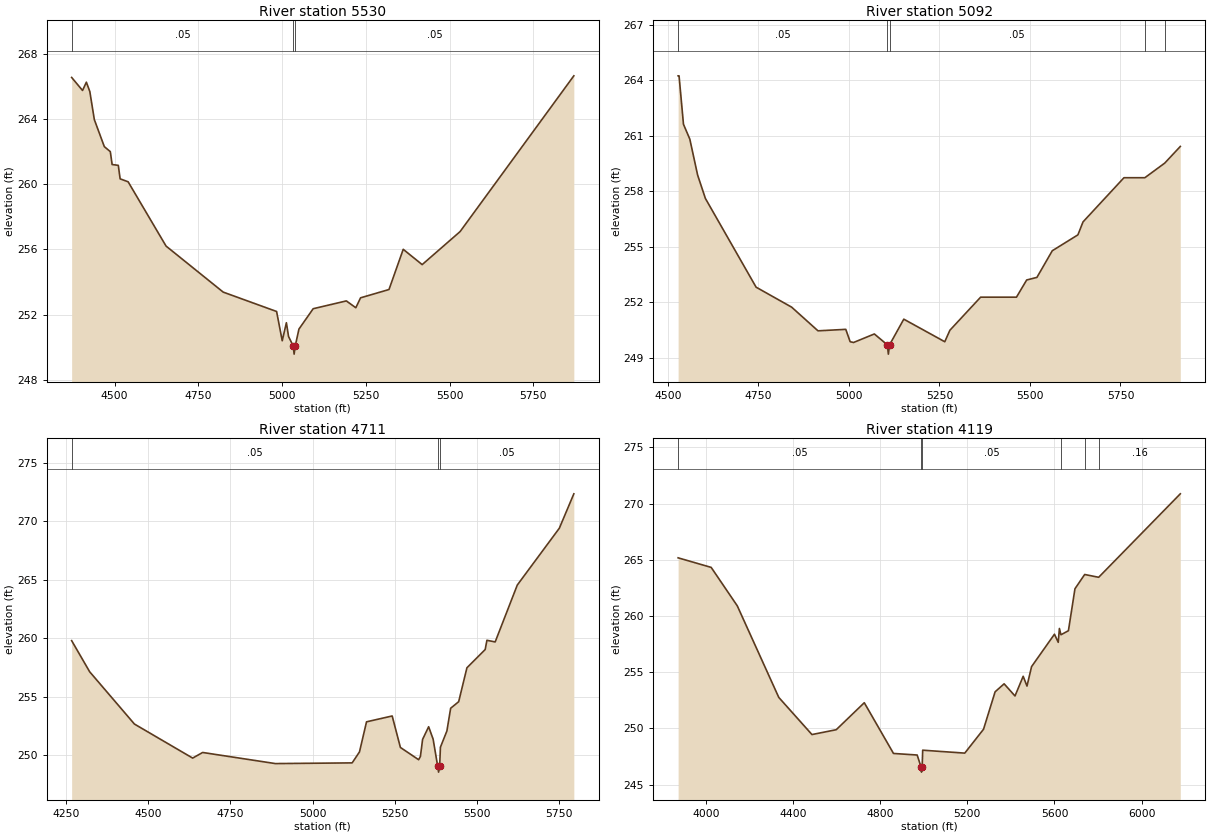
Type RM Length L Ch R = 1 ,5530    ,438,438,438
BEGIN DESCRIPTION:
UNT05237 IN WICK 5.0
END DESCRIPTION:
XS GIS Cut Line= 3
      3577292.12     10247141.68      3577042.11     10246541.64
      3576442.08     10245941.62
#Sta/Elev= 30
    4372  266.57  4404.5  265.77  4415.9  266.28  4426.2  265.71  4439.7  263.98
  4469.5  262.32  4487.4  262.01  4492.8  261.22  4511.2  261.17  4516.7  260.34
  4540.5  260.16  4653.7  256.21  4824.3  253.38  4983.6  252.19  5000.4  250.39
  5012.8   251.5  5019.3  250.65  5033.2  250.07  5035.9  249.57  5039.2  250.07
  5050.3  251.11  5092.8  252.36  5191.7  252.84    5220  252.42  5234.2  253.03
    5319  253.54  5361.5  256.01    5418  255.07  5531.2   257.1  5870.6  266.67
#Mann= 3 ,-1 , 0
    4372     .05       0  5033.2     .03       0  5039.2     .05       0
Bank Sta=5033.2,5039.2
XS Rating Curve= 0 ,0
Exp/Cntr=0.3,0.1

Type RM Length L Ch R = 1 ,5092    ,381,381,381
BEGIN DESCRIPTION:
UNT05237 IN WICK 4.0
END DESCRIPTION:
XS GIS Cut Line= 3
      3577592.09      10246791.6      3577392.11     10246291.64
      3576792.11     10245691.64
#Sta/Elev= 30
  4528.3  264.24  4530.9  264.24  4543.1  261.62  4560.6  260.82  4582.1  258.88
  4603.6  257.61  4743.7  252.81  4841.9  251.73  4914.6  250.45  4991.4  250.53
  5003.5  249.86  5012.9  249.82  5070.3  250.28  5106.2  249.69    5109  249.19
  5112.2  249.69  5151.6  251.08  5264.8  249.86  5278.9  250.48  5363.8  252.27
  5462.8  252.27    5491   253.2  5519.3  253.34  5561.7  254.78  5632.5  255.64
  5646.6  256.34  5759.7  258.73  5817.4  258.73  5872.3  259.52  5915.3  260.42
#Mann= 5 ,-1 , 0
  4528.3     .05       0  5106.2     .03       0  5112.2     .05       0
  5817.4      .1       0  5872.3     .05       0
Bank Sta=5106.2,5112.2
XS Rating Curve= 0 ,0
Exp/Cntr=0.3,0.1

Type RM Length L Ch R = 1 ,4711    ,592,592,592
BEGIN DESCRIPTION:
UNT05237 IN WICK 2.0
END DESCRIPTION:
XS GIS Cut Line= 2
       3577664.4     10246672.66      3577134.87     10245240.31
#Sta/Elev= 30
  4267.1  259.78  4321.9  257.12    4458  252.65  4635.1  249.74  4665.5  250.22
  4886.6  249.27  5120.1  249.33  5142.4  250.27  5163.8  252.84  5241.8  253.34
  5266.8  250.65  5322.3   249.6  5327.7  249.89  5334.3  251.34  5352.7  252.42
  5366.3  251.36  5380.2  249.04  5382.9  248.54  5386.2  249.04  5388.5  250.67
  5408.2  252.06  5419.6     254    5444  254.56  5469.1  257.46  5524.6  259.02
  5529.9  259.81    5555  259.67  5622.2  264.53  5750.1  269.39  5794.2  272.33
#Mann= 3 ,-1 , 0
  4267.1     .05       0  5380.2     .03       0  5386.2     .05       0
Bank Sta=5380.2,5386.2
XS Rating Curve= 0 ,0
Exp/Cntr=0.3,0.1

Type RM Length L Ch R = 1 ,4119    ,0,0,0
BEGIN DESCRIPTION:
UNT05237 IN WICK 1.0
END DESCRIPTION:
XS GIS Cut Line= 4
      3577855.36     10246681.34      3578037.36     10246255.88
      3577638.35     10245005.98      3577108.82     10245014.66
#Sta/Elev= 30
  3873.1  265.17  4024.8  264.32  4144.7   260.9  4335.1  252.76  4487.3  249.46
  4598.6  249.89  4727.4  252.29  4861.4  247.78  4970.1  247.64  4987.1  246.62
  4989.9  246.12  4993.1  246.62  4995.4  248.07  5188.5  247.81  5274.5  249.93
  5327.7  253.26    5369  253.97    5419  252.89  5456.5  254.64    5474  253.77
    5495   255.5    5600  258.38  5617.4  257.66  5622.7  258.89  5629.8  258.33
  5664.1  258.69  5694.1  262.42  5738.7  263.69  5802.9  263.44  6177.5  270.86
#Mann= 6 ,-1 , 0
  3873.1     .05       0  4987.1     .03       0  4993.1     .05       0
  5629.8     .16       0  5738.7     .05       0  5802.9     .16       0
Bank Sta=4987.1,4993.1
XS Rating Curve= 0 ,0
Exp/Cntr=0.3,0.1

Chan Stop Cuts=-1
Use User Specified Reach Order=0
Composite Channel Slope=5