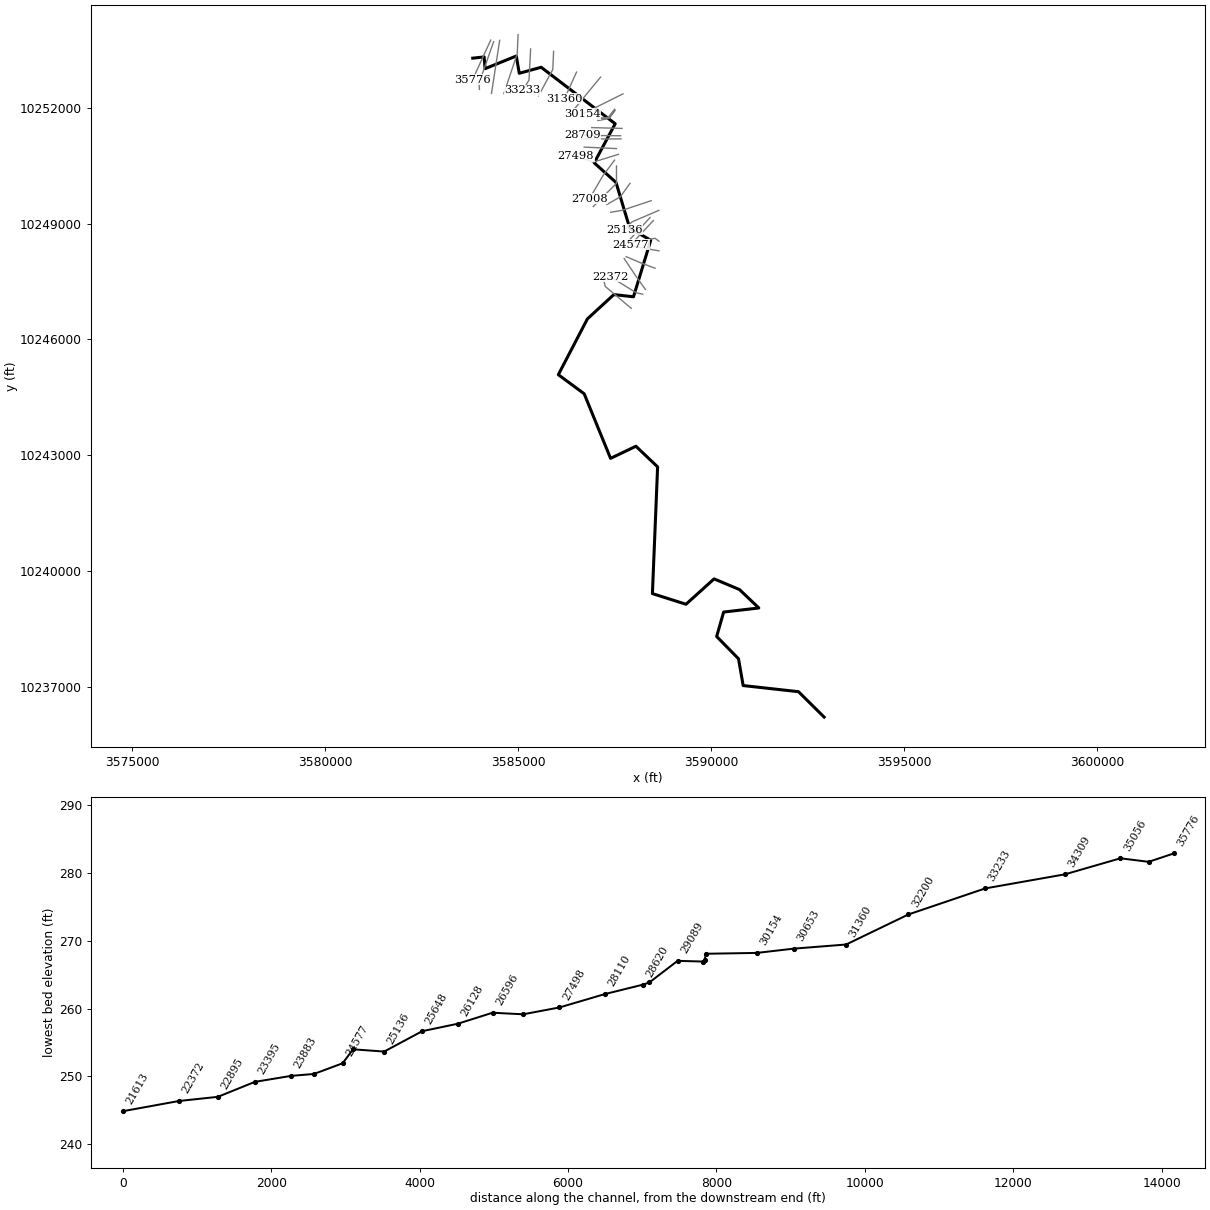
--- WICKSONCREEKTRIB.prj (project) ---

Proj Title=WICKSON CREEK TRIB 14
Current Plan=p01
Default Exp/Contr=0.3,0.1
English Units
Geom File=g01
Flow File=f01
Plan File=p01
Y Axis Title=Elevation
X Axis Title(PF)=Main Channel Distance
X Axis Title(XS)=Station
BEGIN DESCRIPTION:
UNT0505 IN WICK
END DESCRIPTION:
DSS Export Rating Curves= 0
DSS Export Rating Curve Sorted= 0
DSS Export Volume Flow Curves= 0
DXF Filename=UNT0505 IN WICK.
DXF OffsetX= 0
DXF OffsetY= 0
DXF ScaleX= 1
DXF ScaleY= 10

--- WICKSONCREEKTRIB.p01 (plan) ---

Plan Title=Multiple Run
Short Identifier=Multiple
Geom File=g01
Flow File=f01
Subcritical Flow
K Sum by GR= 0
Std Step Tol= 0.01
Critical Tol= 0.01
Num of Std Step Trials= 20
Max Error Tol= 0.3
Flow Tol Ratio= 0.001
Split Flow NTrial= 30
Split Flow Tol= 0.02
Split Flow Ratio= 0.02
Log Output Level= 0
Friction Slope Method= 1
Unsteady Friction Slope Method= 2
Unsteady Bridges Friction Slope Method= 1
Parabolic Critical Depth
Global Vel Dist=  1 , 1 , 1
Global Log Level= 0
CheckData=True
Encroach Param= -1, 0, 0, 0
BEGIN DESCRIPTION:
Multiple Run
END DESCRIPTION:

--- WICKSONCREEKTRIB.f01 (steady flow) ---

Flow Title=Multiple
Program Version=4.10
Number of Profiles= 7
Profile Names=10-year,25-year,50-year,1pct_min,100-year,1pct_plu,500-year
River Rch & RM=UNT0505 IN WICK,Reach-1         ,35776
     762    1030    1249    1108    1498    2026    2160
River Rch & RM=UNT0505 IN WICK,Reach-1         ,24716
     995    1362    1665    1487    2011    2720    2942
River Rch & RM=WICKSONCRTR14,Reach-1         ,35776
     762    1030    1249    1108    1498    2026    2160
River Rch & RM=WICKSONCRTR14,Reach-1         ,24716
     995    1362    1665    1487    2011    2720    2942
Boundary for River Rch & Prof#=WICKSONCRTR14,Reach-1         , 1
Up Type= 0
Dn Type= 3
Dn Slope=0.005
Boundary for River Rch & Prof#=WICKSONCRTR14,Reach-1         , 2
Up Type= 0
Dn Type= 3
Dn Slope=0.005
Boundary for River Rch & Prof#=WICKSONCRTR14,Reach-1         , 3
Up Type= 0
Dn Type= 3
Dn Slope=0.005
Boundary for River Rch & Prof#=WICKSONCRTR14,Reach-1         , 4
Up Type= 0
Dn Type= 3
Dn Slope=0.005
Boundary for River Rch & Prof#=WICKSONCRTR14,Reach-1         , 5
Up Type= 0
Dn Type= 3
Dn Slope=0.005
Boundary for River Rch & Prof#=WICKSONCRTR14,Reach-1         , 6
Up Type= 0
Dn Type= 3
Dn Slope=0.005
Boundary for River Rch & Prof#=WICKSONCRTR14,Reach-1         , 7
Up Type= 0
Dn Type= 3
Dn Slope=0.005
DSS Import GetInterval= 0
DSS Import GetPeak= 0
DSS Import FillOption= 0

--- WICKSONCREEKTRIB.g01 (geometry) ---

Geom Title=Existing Conditions
Program Version=4.10

River Reach=WICKSONCRTR14   ,Reach-1
Reach XY= 30
      3583817.66     10253284.33       3584113.5     10253316.27
      3584136.88     10253012.12       3584946.4     10253339.98
      3585022.88     10252892.79      3585590.79     10253048.39
      3587508.92     10251585.05      3586964.83     10250572.83
      3587529.77     10250064.23      3587886.79     10248876.35
      3588429.92     10248567.22      3587982.75     10247101.77
      3587473.67     10247158.24      3586788.51     10246528.76
      3586035.54     10245083.23      3586705.38     10244588.03
       3587388.9     10242914.91       3588045.8     10243229.22
       3588607.7     10242694.53      3588472.87     10239411.19
      3589342.55     10239135.11      3590071.28     10239792.58
      3590730.13     10239515.23      3591230.13     10239038.67
      3590318.68      10238933.2      3590137.76     10238299.48
      3590704.01     10237722.74      3590824.45      10237028.3
      3592257.63     10236869.64      3592922.11     10236211.64

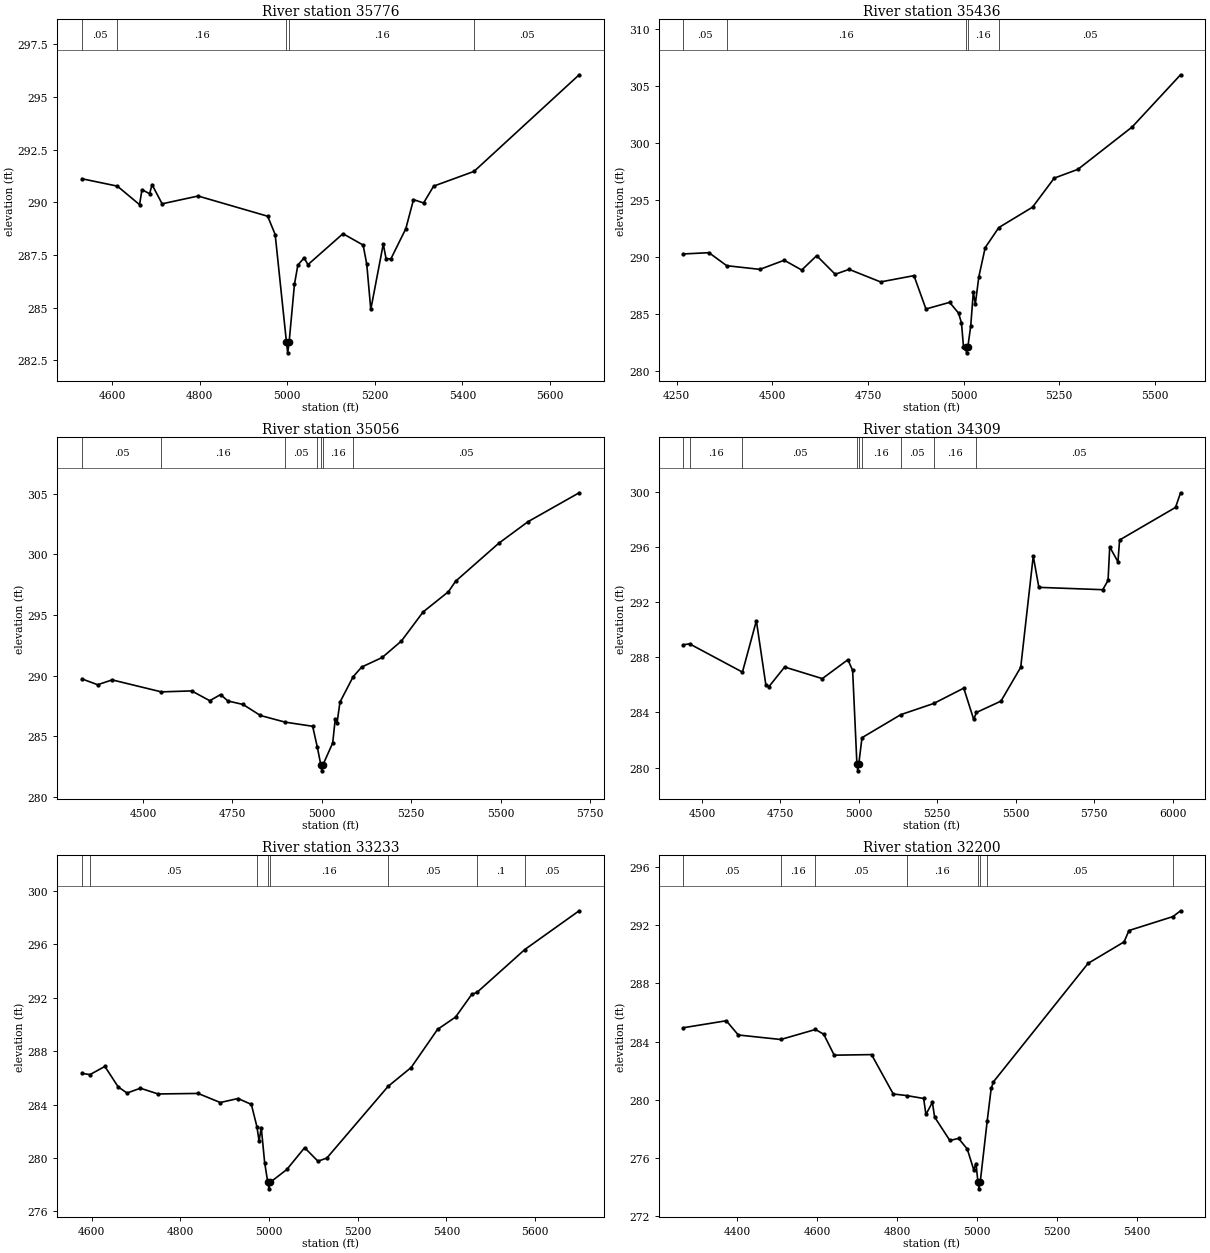
Type RM Length L Ch R = 1 ,35776   ,340,340,340
BEGIN DESCRIPTION:
UNT0505 IN WICK 37.0
END DESCRIPTION:
XS GIS Cut Line= 2
       3584283.5     10253752.65      3583810.45     10252720.82
#Sta/Elev= 30
  4531.5  291.12  4612.3  290.77    4663  289.89  4668.5   290.6    4686  290.41
  4691.5  290.84  4714.5  289.93  4796.6   290.3  4955.5  289.34  4972.6  288.47
  4998.4  283.35  5001.2  282.85  5004.4  283.35  5016.6   286.1  5024.4  287.02
  5038.6  287.36  5047.4  287.04  5127.4  288.51  5173.4  287.97  5181.7  287.06
  5190.9  284.91  5219.4  288.02  5225.7  287.33  5236.7  287.31  5270.9  288.75
  5288.4  290.13  5311.4  289.97  5334.4  290.77  5426.6  291.47  5666.6  296.06
#Mann= 5 ,-1 , 0
  4531.5     .05       0  4612.3     .16       0  4998.4     .07       0
  5004.4     .16       0  5426.6     .05       0
Bank Sta=4998.4,5004.4
XS Rating Curve= 0 ,0
Exp/Cntr=0.3,0.1

Type RM Length L Ch R = 1 ,35436   ,380,380,380
BEGIN DESCRIPTION:
Mapping XS 0f96a7a2
END DESCRIPTION:
XS GIS Cut Line= 3
      3584359.06     10253710.41      3583980.58       10252634.
      3583990.92     10252475.45
#Sta/Elev= 30
  4267.3  290.27  4334.2  290.38  4380.7  289.24  4467.4  288.92    4531  289.72
  4576.7  288.86  4615.8  290.12  4664.3  288.49  4700.6  288.92  4782.9  287.82
  4870.2  288.37  4901.5  285.45  4963.4  286.03  4986.8  285.09  4994.4  284.23
  4999.7  282.14    5005  282.11  5007.8  281.61    5011  282.11  5018.6  283.96
  5025.4  286.92  5030.7   285.9  5039.8  288.27  5056.4  290.82    5092  292.58
  5180.3  294.37  5236.9  296.91  5298.9  297.68  5440.7  301.39  5567.2  305.96
#Mann= 5 ,-1 , 0
  4267.3     .05       0  4380.7     .16       0    5005     .07       0
    5011     .16       0    5092     .05       0
Bank Sta=5005,5011
XS Rating Curve= 0 ,0
Exp/Cntr=0.3,0.1

Type RM Length L Ch R = 1 ,35056   ,747,747,747
BEGIN DESCRIPTION:
Mapping XS 89fb72c4
END DESCRIPTION:
XS GIS Cut Line= 2
       3584515.3      10253745.1       3584303.5     10252370.12
#Sta/Elev= 30
  4328.8  289.72  4372.8  289.24  4413.2  289.64  4550.9  288.65  4635.8  288.73
  4686.4  287.92  4716.8  288.43    4737   287.9  4779.6  287.61  4828.1   286.7
  4897.5  286.15  4974.3  285.81  4987.4  284.08  4997.1  282.63  4999.8  282.13
  5003.1  282.63  5030.4  284.43  5037.5  286.41  5042.5  286.07  5050.7   287.8
  5087.4  289.89  5111.4   290.7  5168.9  291.49  5222.7  292.85  5283.4  295.25
  5354.2  296.92  5374.4  297.79    5495  300.92  5576.8   302.7    5720  305.09
#Mann= 7 ,-1 , 0
  4328.8     .05       0  4550.9     .16       0  4897.5     .05       0
  4987.4     .16       0  4997.1     .07       0  5003.1     .16       0
  5087.4     .05       0
Bank Sta=4997.1,5003.1
XS Rating Curve= 0 ,0
Exp/Cntr=0.3,0.1

Type RM Length L Ch R = 1 ,34309   ,1076,1076,1076
BEGIN DESCRIPTION:
UNT0505 IN WICK 36.0
END DESCRIPTION:
XS GIS Cut Line= 3
      3584992.71     10253894.15      3584971.01     10253399.36
      3584623.83     10252366.51
#Sta/Elev= 30
  4440.6   288.9  4460.2  288.97  4628.9  286.92  4673.3  290.64  4703.4  286.02
  4713.4  285.87  4763.4  287.29  4883.5  286.45  4965.1  287.82  4980.2  287.04
  4993.8  280.27  4996.5  279.77  4999.8  280.27    5010  282.17  5133.7  283.84
  5238.8  284.65  5334.4  285.76    5366   283.5    5375     284    5453  284.82
    5516  287.27  5555.9  295.32  5573.8  293.06  5777.4  292.89  5794.4  293.56
  5799.7  295.99  5825.9  294.91  5831.2  296.49  6009.5  298.85  6025.5  299.91
#Mann= 9 ,-1 , 0
  4440.6     .05       0  4460.2     .16       0  4628.9     .05       0
  4993.8     .03       0  4999.8     .05       0    5010     .16       0
  5133.7     .05       0  5238.8     .16       0    5375     .05       0
Bank Sta=4993.8,4999.8
XS Rating Curve= 0 ,0
Exp/Cntr=0.3,0.1

Type RM Length L Ch R = 1 ,33233   ,1033,1033,1033
BEGIN DESCRIPTION:
UNT0505 IN WICK 35.0
END DESCRIPTION:
XS GIS Cut Line= 3
      3585317.87     10253523.23       3585276.2     10252717.72
      3585109.56     10252450.39
#Sta/Elev= 30
    4578  286.33  4596.1  286.24  4629.7  286.85  4659.7  285.32  4679.7  284.86
  4709.8  285.22  4749.8  284.79  4839.9  284.83    4890  284.15  4930.1  284.45
  4960.1  284.01  4972.9  282.31  4977.5  281.26  4982.5  282.28  4990.1  279.66
  4997.1  278.19  4999.9  277.69  5003.1  278.19  5040.2  279.14  5080.3  280.77
  5110.3  279.76  5130.3  279.99  5268.6  285.36  5320.6  286.77  5380.1  289.62
  5420.9  290.55  5457.5  292.25  5469.1  292.39    5577   295.6  5699.6   298.5
#Mann= 8 ,-1 , 0
    4578     .16       0  4596.1     .05       0  4972.9     .16       0
  4997.1     .07       0  5003.1     .16       0  5268.6     .05       0
  5469.1      .1       0    5577     .05       0
Bank Sta=4997.1,5003.1
XS Rating Curve= 0 ,0
Exp/Cntr=0.3,0.1

Type RM Length L Ch R = 1 ,32200   ,840,840,840
BEGIN DESCRIPTION:
UNT0505 IN WICK 34.0
END DESCRIPTION:
XS GIS Cut Line= 3
      3585912.66     10253459.07      3585891.83     10252990.28
      3585522.04       10252308.
#Sta/Elev= 30
  4264.6  284.95  4372.1  285.43  4402.2  284.45  4508.6  284.14  4595.5  284.83
  4616.2   284.5  4642.4  283.06  4735.9   283.1  4790.3  280.39  4823.9  280.28
  4866.4  280.08  4872.1  278.98  4888.3  279.81  4893.9   278.8    4932  277.19
  4953.9  277.33  4975.7   276.6  4991.9  275.17  4997.6   275.6  5002.3  274.36
    5005  273.86  5008.3  274.36  5025.6  278.53  5035.6  280.77  5041.3  281.23
  5278.3  289.38  5368.5  290.86  5380.6  291.64  5490.8   292.6  5509.9     293
#Mann= 8 ,-1 , 0
  4264.6     .05       0  4508.6     .16       0  4595.5     .05       0
  4823.9     .16       0  5002.3     .07       0  5008.3     .16       0
  5025.6     .05       0  5490.8      .1       0
Bank Sta=5002.3,5008.3
XS Rating Curve= 0 ,0
Exp/Cntr=0.3,0.1

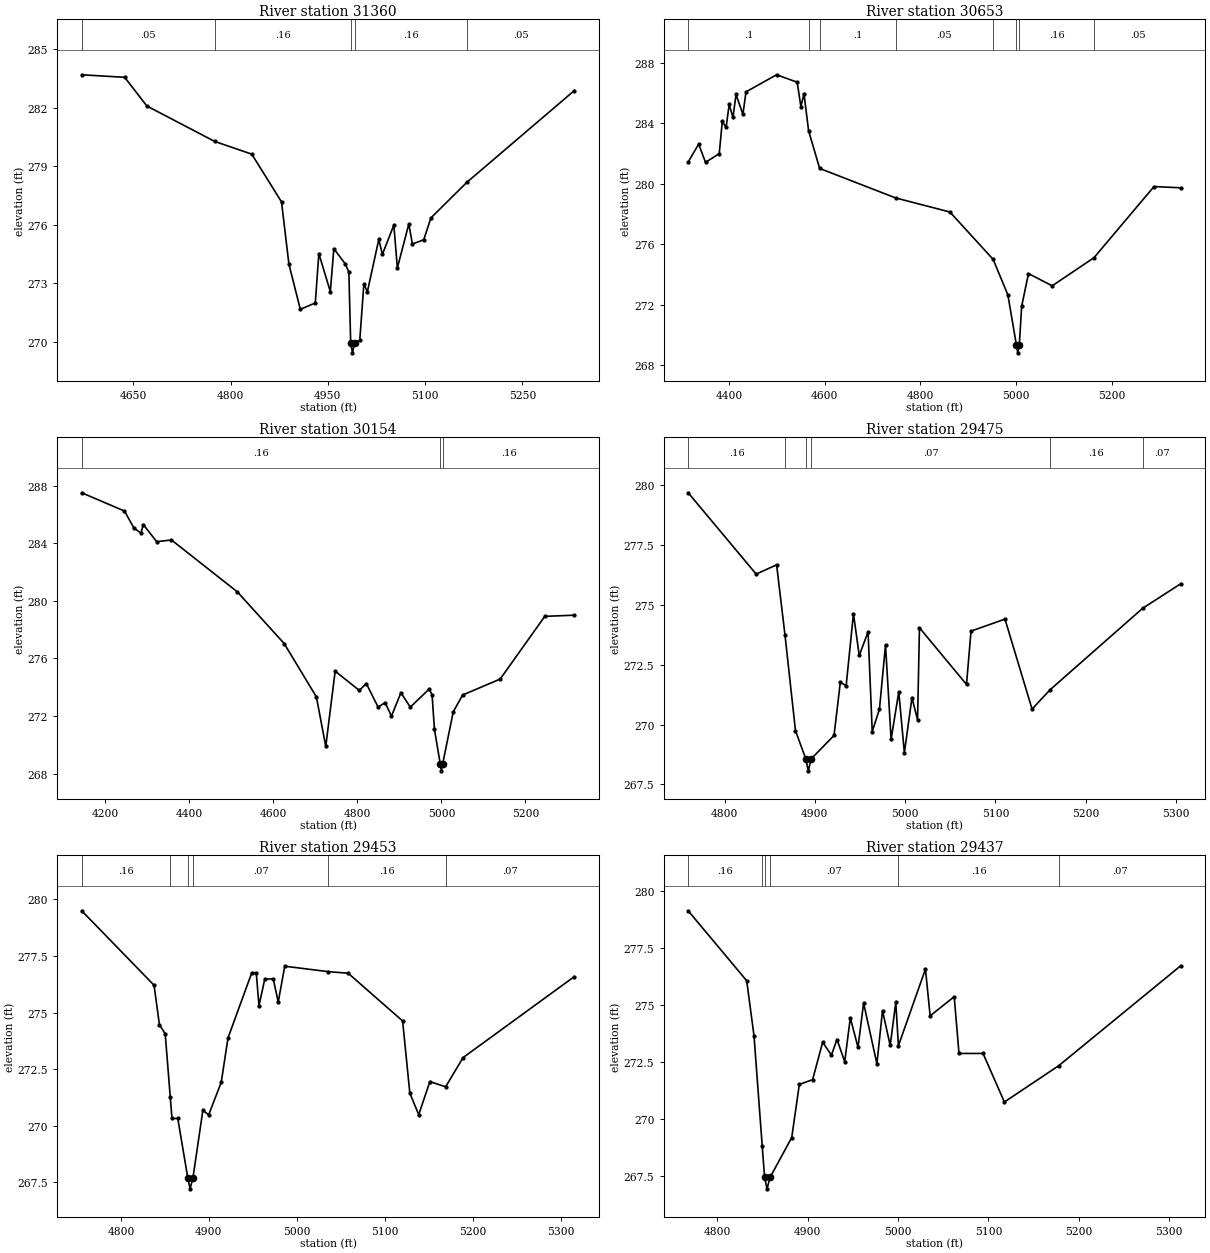
Type RM Length L Ch R = 1 ,31360   ,707,707,707
BEGIN DESCRIPTION:
Mapping XS 4f3f7c7c
END DESCRIPTION:
XS GIS Cut Line= 2
      3586506.41     10252922.58      3586193.93     10252229.91
#Sta/Elev= 30
  4570.3  283.69  4636.6  283.56  4670.7  282.09  4775.5  280.27  4832.6  279.62
  4878.5  277.17  4889.9  273.98  4907.5  271.66  4930.6  271.99  4936.1  274.52
  4953.8  272.57  4959.2  274.77  4976.9  273.99  4982.4  273.57  4985.2  269.93
    4988  269.43  4991.2  269.93  4999.2  270.07  5005.5  272.95    5011  272.57
  5028.6  275.25  5034.1  274.48  5051.8  275.98  5057.2  273.78  5074.9  276.04
  5080.4  275.01  5097.9  275.23    5109  276.35  5164.6  278.18  5330.2  282.88
#Mann= 5 ,-1 , 0
  4570.3     .05       0  4775.5     .16       0  4985.2     .07       0
  4991.2     .16       0  5164.6     .05       0
Bank Sta=4985.2,4991.2
XS Rating Curve= 0 ,0
Exp/Cntr=0.3,0.1

Type RM Length L Ch R = 1 ,30653   ,499,499,499
BEGIN DESCRIPTION:
Mapping XS b38f88ec
END DESCRIPTION:
XS GIS Cut Line= 2
      3587130.17     10252794.43      3586476.92     10251998.34
#Sta/Elev= 30
    4315  281.43  4336.8  282.62  4351.2  281.41  4379.9  281.99  4386.3  284.12
  4394.2  283.72  4400.7  285.24  4408.6  284.38    4415   285.9  4429.4  284.58
  4435.8  286.07  4499.7   287.2  4542.8  286.71  4550.6   285.1  4557.1  285.95
  4566.7   283.5  4589.8  281.01  4748.6  279.06  4862.1  278.13  4952.5     275
  4983.4  272.64  5001.2  269.32    5004  268.82  5007.2  269.32  5012.1  271.89
  5026.4  274.06  5075.9  273.25  5163.4  275.11  5288.8  279.81  5344.8  279.73
#Mann= 8 ,-1 , 0
    4315      .1       0  4566.7     .05       0  4589.8      .1       0
  4748.6     .05       0  4952.5     .16       0  5001.2     .07       0
  5007.2     .16       0  5163.4     .05       0
Bank Sta=5001.2,5007.2
XS Rating Curve= 0 ,0
Exp/Cntr=0.3,0.1

Type RM Length L Ch R = 1 ,30154   ,679,679,679
BEGIN DESCRIPTION:
Mapping XS 684bba75
END DESCRIPTION:
XS GIS Cut Line= 2
      3587711.78     10252360.39      3586662.79      10251835.9
#Sta/Elev= 30
  4143.6  287.52  4245.4  286.25  4267.8  285.07  4284.6  284.72  4290.2  285.31
  4322.1  284.12  4357.2  284.24  4513.8  280.64  4625.6  277.04  4702.3  273.33
  4724.6  269.89    4747  275.12  4804.5  273.78  4821.2  274.26  4849.2  272.62
  4865.9  272.93  4881.1  271.99  4903.5  273.62  4925.9  272.62  4970.6  273.87
  4977.7  273.49  4983.3  271.09  4997.1  268.69  4999.9  268.19  5003.1  268.69
  5028.1  272.29  5050.4  273.46  5139.9  274.57  5246.1  278.93  5316.4  279.01
#Mann= 3 ,-1 , 0
  4143.6     .16       0  4997.1     .07       0  5003.1     .16       0
Bank Sta=4997.1,5003.1
XS Rating Curve= 0 ,0
Exp/Cntr=0.3,0.1

Type RM Length L Ch R = 1 ,29475   ,22,22,22
BEGIN DESCRIPTION:
Mapping XS 2c150ad0
END DESCRIPTION:
XS GIS Cut Line= 5
      3587490.89     10251959.22      3587370.46     10251804.07
      3587334.65     10251755.25      3587246.76     10251741.14
      3587048.19     10251721.61
#Sta/Elev= 30
  4759.8  279.69  4835.1  276.29  4857.7  276.68    4867  273.74  4878.6  269.75
    4890  268.57  4892.8  268.07    4896  268.57  4921.3  269.55  4928.3  271.78
  4934.7  271.62  4942.8  274.64  4949.2  272.89    4959  273.88  4963.6  269.71
  4971.6  270.65  4978.3  273.33  4984.5  269.39    4993  271.37  4999.2  268.82
  5007.6  271.13  5013.8   270.2  5015.9  274.05    5068  271.68    5073  273.91
  5110.6  274.41  5140.6  270.65  5160.6  271.46    5263  274.86  5305.3  275.89
#Mann= 6 ,-1 , 0
  4759.8     .16       0    4867     .07       0    4890     .07       0
    4896     .07       0  5160.6     .16       0    5263     .07       0
Bank Sta=4890,4896
XS Rating Curve= 0 ,0
Exp/Cntr=0.3,0.1

Type RM Length L Ch R = 1 ,29453   ,16,16,16
BEGIN DESCRIPTION:
Mapping XS 703ed307
END DESCRIPTION:
XS GIS Cut Line= 6
      3587501.76     10251945.15      3587379.14     10251792.14
      3587355.27     10251747.65      3587318.38     10251732.46
      3587240.25     10251730.29      3587046.61     10251705.41
#Sta/Elev= 30
  4755.5   279.5  4837.7  276.21  4843.8  274.47  4850.4  274.06  4856.1  271.29
  4858.1  270.32  4864.7  270.32    4876  267.71  4878.7  267.21    4882  267.71
  4893.2  270.68  4899.8  270.48  4914.1  271.92  4921.8  273.88  4948.8  276.76
  4953.9  276.76    4957  275.31  4963.6  276.48  4973.2  276.49  4978.9  275.47
  4986.3  277.05  5035.6  276.81  5058.4  276.74  5120.3  274.63  5128.5  271.44
  5138.6  270.49  5151.3  271.95  5169.2  271.72    5189  273.01  5315.5  276.59
#Mann= 6 ,-1 , 0
  4755.5     .16       0  4856.1     .07       0    4876     .07       0
    4882     .07       0  5035.6     .16       0  5169.2     .07       0
Bank Sta=4876,4882
XS Rating Curve= 0 ,0
Exp/Cntr=0.3,0.1

Type RM Length L Ch R = 1 ,29437   ,348,348,348
BEGIN DESCRIPTION:
Mapping XS 66061a4c
END DESCRIPTION:
XS GIS Cut Line= 5
      3587501.58     10251923.64      3587411.26     10251801.58
      3587364.26     10251736.64      3587260.22     10251702.62
      3587059.72     10251668.77
#Sta/Elev= 30
    4768  279.12  4832.7  276.05  4840.8  273.63  4849.9  268.78  4852.5  267.42
  4855.2  266.92  4858.5  267.42  4882.5  269.17  4890.9   271.5  4905.6  271.71
  4916.7  273.35  4926.4  272.79  4932.6  273.47  4941.1   272.5  4947.3  274.42
  4955.8  273.13    4962  275.07  4976.7  272.41  4982.9  274.74  4991.4  273.21
  4997.6   275.1  5000.5   273.2  5030.4  276.56  5035.6  274.51  5062.2  275.35
  5067.5  272.86  5094.1  272.86  5117.7  270.73  5177.7  272.32  5312.8  276.71
#Mann= 6 ,-1 , 0
    4768     .16       0  4849.9     .07       0  4852.5     .07       0
  4858.5     .07       0  5000.5     .16       0  5177.7     .07       0
Bank Sta=4852.5,4858.5
XS Rating Curve= 0 ,0
Exp/Cntr=0.3,0.1

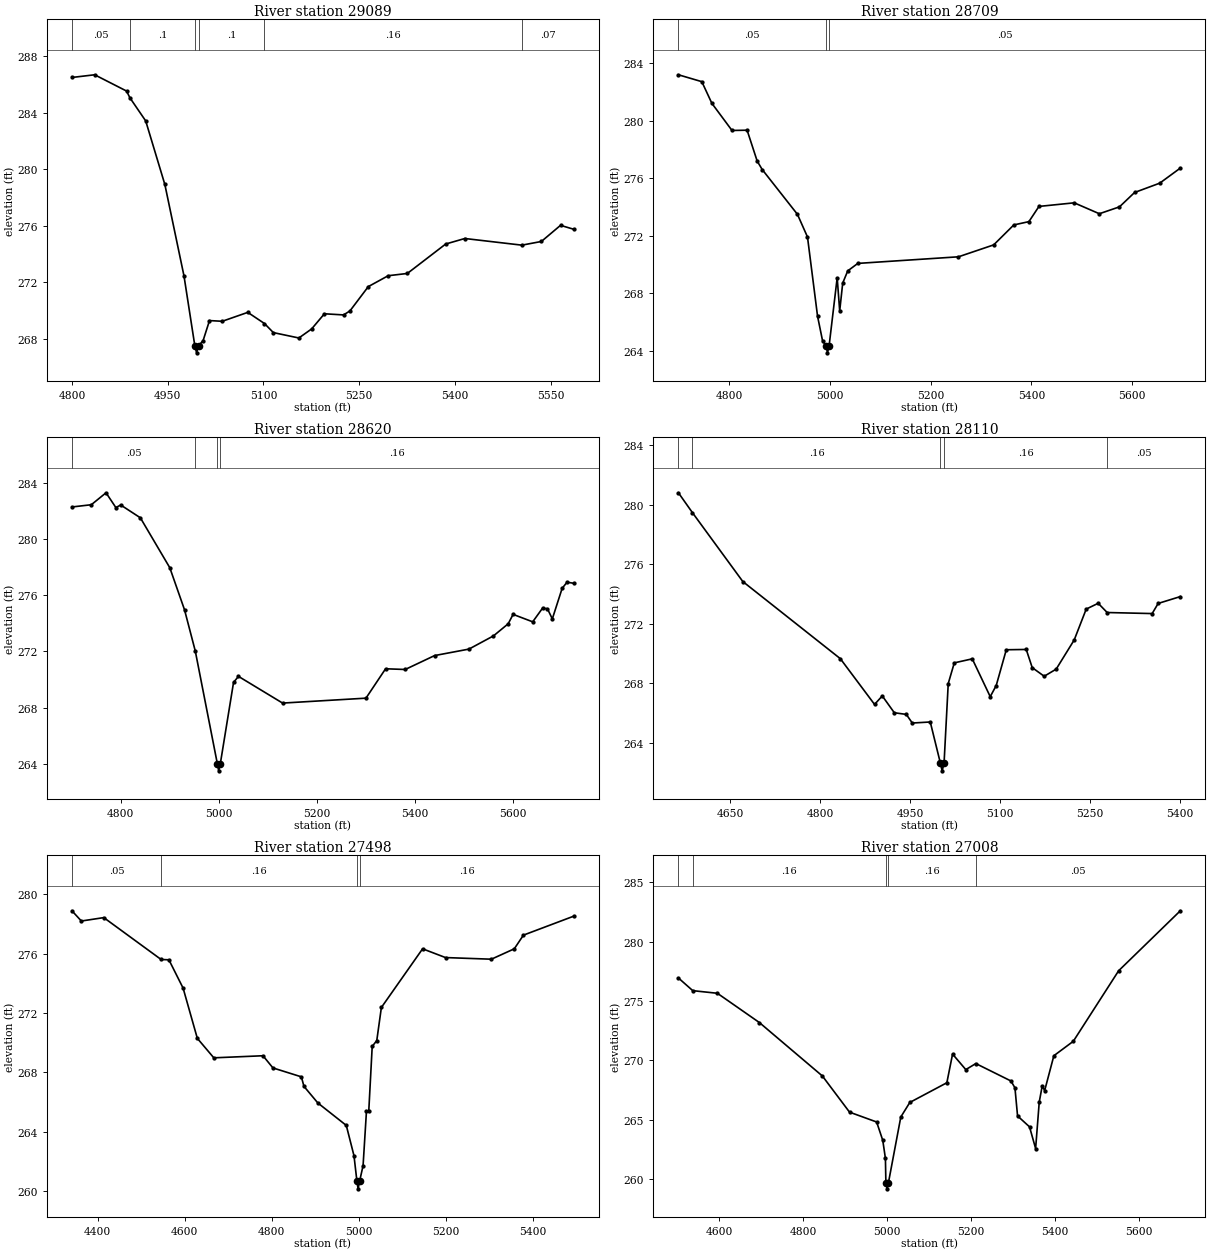
Type RM Length L Ch R = 1 ,29089   ,380,380,380
BEGIN DESCRIPTION:
Mapping XS c4bb406f
END DESCRIPTION:
XS GIS Cut Line= 2
      3587687.65     10251464.24      3586901.23     10251485.08
#Sta/Elev= 30
  4799.9  286.48  4835.5  286.67  4885.5  285.52  4890.8  285.04  4915.5  283.41
  4945.5  278.92  4975.5  272.46  4992.5  267.52  4995.3  267.02  4998.5  267.52
  5005.5  267.89  5015.5   269.3  5035.5  269.25  5075.5  269.88  5101.7  269.09
  5115.6  268.45  5155.6  268.07  5175.6  268.71  5195.6  269.78  5225.6   269.7
  5235.6  269.98  5264.4   271.7  5295.6  272.47  5325.6  272.63  5385.7  274.71
  5415.7   275.1  5505.1  274.63  5535.7  274.89  5565.7  276.03  5586.6  275.75
#Mann= 6 ,-1 , 0
  4799.9     .05       0  4890.8      .1       0  4992.5     .07       0
  4998.5      .1       0  5101.7     .16       0  5505.1     .07       0
Bank Sta=4992.5,4998.5
XS Rating Curve= 0 ,0
Exp/Cntr=0.3,0.1

Type RM Length L Ch R = 1 ,28709   ,89,89,89
BEGIN DESCRIPTION:
UNT0505 IN WICK 33.0
END DESCRIPTION:
XS GIS Cut Line= 2
      3587648.59     10251274.14      3586651.22     10251281.95
#Sta/Elev= 30
  4698.5  283.21    4745  282.73    4765  281.22    4805  279.33    4835  279.35
    4855   277.2    4865  276.61    4935  273.49    4955  271.91    4975  266.39
    4985  264.67    4992  264.34  4994.7  263.84    4998  264.34    5014  269.07
    5019  266.76    5025   268.7    5035  269.55    5055  270.07    5255  270.53
    5325  271.36    5365  272.75    5395  272.98    5415  274.04    5485  274.29
    5535  273.53    5575  274.01    5605  275.01    5655  275.66  5695.9  276.71
#Mann= 3 ,-1 , 0
  4698.5     .05       0    4992     .04       0    4998     .05       0
Bank Sta=4992,4998
XS Rating Curve= 0 ,0
Exp/Cntr=0.3,0.1

Type RM Length L Ch R = 1 ,28620   ,510,510,510
BEGIN DESCRIPTION:
UNT0505 IN WICK 32.0
END DESCRIPTION:
XS GIS Cut Line= 2
      3587661.57     10251193.41      3586638.19      10251188.2
#Sta/Elev= 30
  4700.7  282.28  4740.2  282.44  4770.2  283.29  4790.2  282.24  4800.2  282.42
  4840.2  281.51  4900.2  277.96  4930.2  274.97  4952.2  272.03  4997.2  264.01
  4999.9  263.51  5003.2  264.01  5030.2   269.8  5040.2  270.23  5130.2  268.33
  5300.2  268.68  5340.2  270.77  5380.2  270.72  5440.2  271.71  5510.2  272.17
  5560.2  273.11  5590.2  273.97  5600.2  274.64  5640.2  274.11  5660.2  275.08
  5670.2  275.04  5680.2  274.32  5700.2  276.49  5710.2  276.93  5724.1  276.85
#Mann= 4 ,-1 , 0
  4700.7     .05       0  4952.2     .16       0  4997.2     .07       0
  5003.2     .16       0
Bank Sta=4997.2,5003.2
XS Rating Curve= 0 ,0
Exp/Cntr=0.3,0.1

Type RM Length L Ch R = 1 ,28110   ,612,612,612
BEGIN DESCRIPTION:
UNT0505 IN WICK 31.0
END DESCRIPTION:
XS GIS Cut Line= 2
      3587542.08     10250941.64      3586705.15     10250979.78
#Sta/Elev= 30
  4563.2   280.8  4586.7  279.46  4670.7  274.84  4833.5  269.66  4890.6  266.59
  4903.5  267.16  4923.6  266.03  4943.6  265.92  4953.6  265.34  4983.6  265.41
  5000.6  262.63  5003.4  262.13  5006.6  262.63  5013.6  267.99  5023.7  269.38
  5053.7  269.65  5083.7  267.11  5093.7  267.86  5110.5  270.26  5143.8  270.28
  5153.8  269.06  5173.8  268.48  5193.8  268.96  5223.9  270.92  5243.9  272.99
  5263.9  273.38  5278.9  272.76    5354  272.69    5364  273.37    5401  273.83
#Mann= 5 ,-1 , 0
  4563.2     .05       0  4586.7     .16       0  5000.6     .07       0
  5006.6     .16       0  5278.9     .05       0
Bank Sta=5000.6,5006.6
XS Rating Curve= 0 ,0
Exp/Cntr=0.3,0.1

Type RM Length L Ch R = 1 ,27498   ,490,490,490
BEGIN DESCRIPTION:
UNT0505 IN WICK 30.0
END DESCRIPTION:
XS GIS Cut Line= 3
      3587592.08     10250791.63      3586942.11     10250591.64
       3586492.1     10250741.65
#Sta/Elev= 30
  4340.6  278.88  4362.2  278.19  4413.8  278.42  4545.7   275.6  4563.6  275.58
  4596.3  273.67    4629  270.29  4666.9  268.98    4780  269.12  4802.9   268.3
  4868.3   267.7  4874.2  267.06  4906.2  265.94  4971.6  264.43  4989.3  262.39
  4996.1  260.66  4998.8  260.16  5002.1  260.66  5010.2  261.72    5018  265.39
  5023.3  265.39  5031.2  269.75  5041.7  270.14  5052.3  272.37  5147.1  276.32
  5199.8  275.73  5305.3  275.62    5358  276.32    5379  277.24    5495  278.52
#Mann= 4 ,-1 , 0
  4340.6     .05       0  4545.7     .16       0  4996.1     .07       0
  5002.1     .16       0
Bank Sta=4996.1,5002.1
XS Rating Curve= 0 ,0
Exp/Cntr=0.3,0.1

Type RM Length L Ch R = 1 ,27008   ,412,412,412
BEGIN DESCRIPTION:
UNT0505 IN WICK 29.0
END DESCRIPTION:
XS GIS Cut Line= 3
      3587492.08     10250641.61      3587192.11     10250241.64
       3586842.1     10249641.63
#Sta/Elev= 30
    4503  276.94  4537.2  275.87  4595.7  275.65  4695.7  273.18  4845.7  268.67
  4910.3  265.62  4974.8  264.79  4989.4  263.24  4995.7  261.72  4996.8  259.65
  4999.6  259.15  5002.8  259.65  5032.3  265.21  5053.8  266.44  5141.9   268.1
  5155.5  270.52    5187  269.21  5210.9  269.72  5294.5  268.25    5304  267.67
  5310.2   265.3  5338.7  264.38  5353.2  262.55  5361.8  266.47  5368.9  267.84
  5374.7  267.44  5396.6  270.38  5442.9   271.6  5550.8  277.55  5697.6  282.61
#Mann= 5 ,-1 , 0
    4503     .05       0  4537.2     .16       0  4996.8     .07       0
  5002.8     .16       0  5210.9     .05       0
Bank Sta=4996.8,5002.8
XS Rating Curve= 0 ,0
Exp/Cntr=0.3,0.1

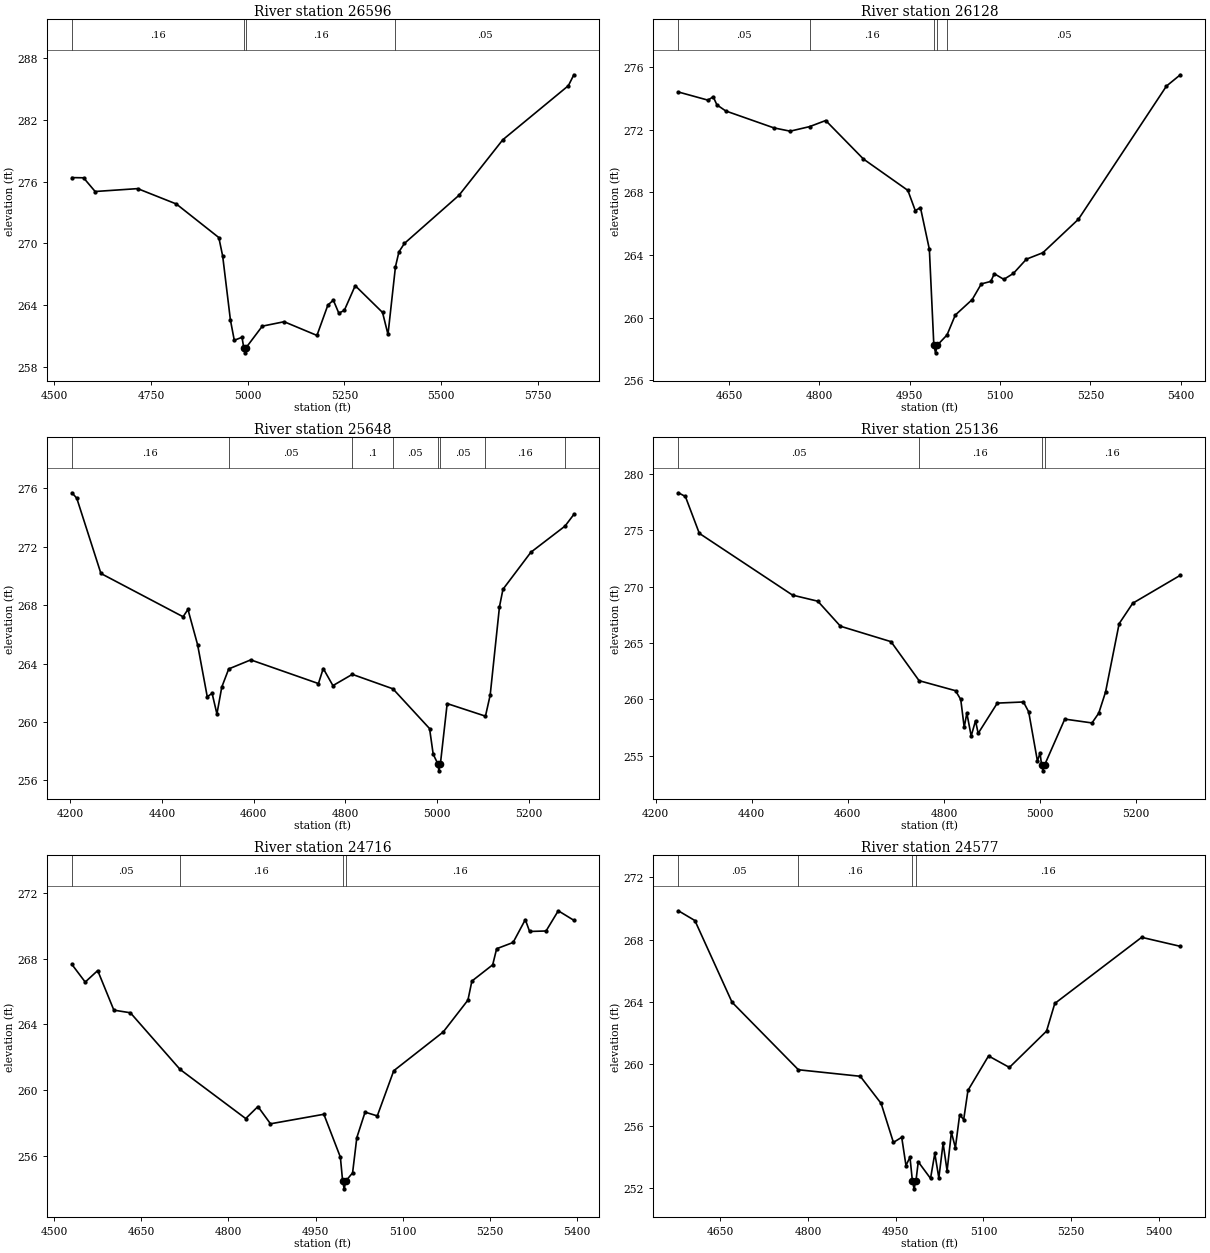
Type RM Length L Ch R = 1 ,26596   ,468,468,468
BEGIN DESCRIPTION:
UNT0505 IN WICK 28.0
END DESCRIPTION:
XS GIS Cut Line= 3
      3587542.11     10250491.67      3587542.11     10250041.64
      3586942.08     10249441.61
#Sta/Elev= 30
  4545.3  276.39  4575.3  276.37  4605.3  275.04  4715.3  275.32  4815.3  273.83
  4925.3  270.57  4935.3  268.77  4955.3  262.57  4965.3   260.6  4985.3  260.89
  4989.8  259.88  4992.6  259.38  4995.8  259.88  5037.8  261.97  5094.3   262.4
  5179.2  261.07  5207.5  264.02  5221.6  264.49  5235.7  263.24  5249.9  263.49
  5278.2   265.9  5348.9   263.3    5363  261.17  5382.3  267.73  5391.3  269.18
  5405.5     270  5546.9  274.68    5660  280.06  5829.7  285.31  5843.9  286.37
#Mann= 4 ,-1 , 0
  4545.3     .16       0  4989.8     .07       0  4995.8     .16       0
  5382.3     .05       0
Bank Sta=4989.8,4995.8
XS Rating Curve= 0 ,0
Exp/Cntr=0.3,0.1

Type RM Length L Ch R = 1 ,26128   ,480,480,480
BEGIN DESCRIPTION:
UNT0505 IN WICK 27.0
END DESCRIPTION:
XS GIS Cut Line= 3
       3587892.1     10250041.63      3587642.11     10249691.64
      3587292.12     10249491.65
#Sta/Elev= 30
  4566.1  274.41  4615.2  273.89  4623.8  274.11    4630  273.59  4644.7   273.2
  4724.6  272.12  4751.6  271.91  4783.8   272.2  4810.6  272.59  4873.3  270.13
    4947  268.13  4959.3  266.84  4967.9  267.03  4982.7  264.37  4990.1  258.26
  4992.9  257.76  4996.1  258.26    5012   258.9  5025.7  260.17  5053.8  261.16
  5068.9  262.16  5084.7  262.32  5090.5  262.81  5106.3  262.45  5122.2  262.83
  5143.8  263.74  5171.1  264.15  5230.2  266.29  5376.3  274.79  5399.3  275.51
#Mann= 5 ,-1 , 0
  4566.1     .05       0  4783.8     .16       0  4990.1     .07       0
  4996.1     .16       0    5012     .05       0
Bank Sta=4990.1,4996.1
XS Rating Curve= 0 ,0
Exp/Cntr=0.3,0.1

Type RM Length L Ch R = 1 ,25648   ,512,512,512
BEGIN DESCRIPTION:
UNT0505 IN WICK 26.0
END DESCRIPTION:
XS GIS Cut Line= 3
       3588442.1     10249591.64      3587692.11     10249341.64
       3587392.1     10249291.64
#Sta/Elev= 30
  4203.7  275.68  4214.2  275.31  4266.9  270.16  4446.1   267.2  4456.7   267.7
  4477.8  265.28  4498.8  261.73  4509.4  261.96  4519.9  260.55  4530.5  262.39
  4545.6  263.63  4593.7  264.25  4741.3  262.63  4751.8  263.66  4772.9  262.49
  4815.2  263.26  4903.8  262.27  4983.7  259.55  4991.6   257.8  5001.4  257.16
  5004.1  256.66  5007.4  257.16  5022.1  261.26  5105.6   260.4  5115.9  261.84
  5136.2  267.89  5143.8  269.08  5204.6  271.61  5279.1   273.4  5298.4   274.2
#Mann= 8 ,-1 , 0
  4203.7     .16       0  4545.6     .05       0  4815.2      .1       0
  4903.8     .05       0  5001.4     .04       0  5007.4     .05       0
  5105.6     .16       0  5279.1     .05       0
Bank Sta=5001.4,5007.4
XS Rating Curve= 0 ,0
Exp/Cntr=0.3,0.1

Type RM Length L Ch R = 1 ,25136   ,420,420,420
BEGIN DESCRIPTION:
UNT0505 IN WICK 25.0
END DESCRIPTION:
XS GIS Cut Line= 3
      3588642.09     10249341.63      3587942.11     10249041.64
      3587742.11     10248841.64
#Sta/Elev= 30
  4247.4  278.33  4261.9     278  4290.9  274.73  4484.9  269.25  4537.5  268.71
  4584.6  266.49  4689.8  265.12  4748.2  261.66    4824  260.77  4834.9  259.99
  4842.1  257.52  4847.6  258.78  4856.6  256.75  4865.7  258.11  4871.1  256.98
    4911  259.67  4965.4  259.77  4976.3  258.89  4994.5  254.52  4999.9  255.25
  5003.2  254.16    5006  253.66  5009.2  254.16  5051.4  258.25    5108  257.91
  5122.1  258.78  5136.2  260.65  5164.5  266.72  5192.8  268.53  5291.8  271.01
#Mann= 4 ,-1 , 0
  4247.4     .05       0  4748.2     .16       0  5003.2     .07       0
  5009.2     .16       0
Bank Sta=5003.2,5009.2
XS Rating Curve= 0 ,0
Exp/Cntr=0.3,0.1

Type RM Length L Ch R = 1 ,24716   ,139,139,139
BEGIN DESCRIPTION:
UNT0505 IN WICK 24.0
END DESCRIPTION:
XS GIS Cut Line= 2
      3588411.63     10249154.36       3587826.4     10248519.71
#Sta/Elev= 30
    4531  267.65  4553.8  266.58  4575.3  267.28  4603.1  264.87  4631.5  264.71
    4717  261.26  4829.9  258.27  4850.9     259  4872.5  257.95  4964.3  258.53
  4992.7  255.92  4996.5  254.49  4999.2  253.99  5002.5  254.49  5013.7  254.96
    5021  257.11  5035.2  258.66  5056.2  258.43  5084.5  261.18  5169.6  263.54
  5212.1  265.48  5218.9  266.64  5254.7  267.63  5261.5  268.61  5289.8  268.99
  5310.8  270.38  5318.2  269.66  5346.5  269.69  5367.5  270.92  5394.3  270.34
#Mann= 4 ,-1 , 0
    4531     .05       0    4717     .16       0  4996.5     .07       0
  5002.5     .16       0
Bank Sta=4996.5,5002.5
XS Rating Curve= 0 ,0
Exp/Cntr=0.3,0.1

Type RM Length L Ch R = 1 ,24577   ,387,387,387
BEGIN DESCRIPTION:
Mapping XS 00e08a0f
END DESCRIPTION:
XS GIS Cut Line= 2
      3588496.89      10249076.6      3587911.64     10248448.64
#Sta/Elev= 30
  4578.4  269.85  4606.6  269.22  4670.1  263.96  4783.6  259.61  4889.4  259.19
  4925.1  257.44  4946.1  254.93  4960.3  255.26  4967.6  253.44  4974.4  253.98
  4978.6  252.44  4981.4  251.94  4984.6  252.44  4988.6  253.68  5009.6  252.61
  5016.9  254.22  5023.8  252.64  5031.1  254.88  5037.9   253.1  5045.3  255.58
  5052.1  254.59  5059.4  256.71  5066.3   256.4  5073.6  258.28  5108.8   260.5
  5144.5  259.76    5208   262.1  5222.1  263.88  5370.7  268.14  5436.8  267.56
#Mann= 4 ,-1 , 0
  4578.4     .05       0  4783.6     .16       0  4978.6     .07       0
  4984.6     .16       0
Bank Sta=4978.6,4984.6
XS Rating Curve= 0 ,0
Exp/Cntr=0.3,0.1

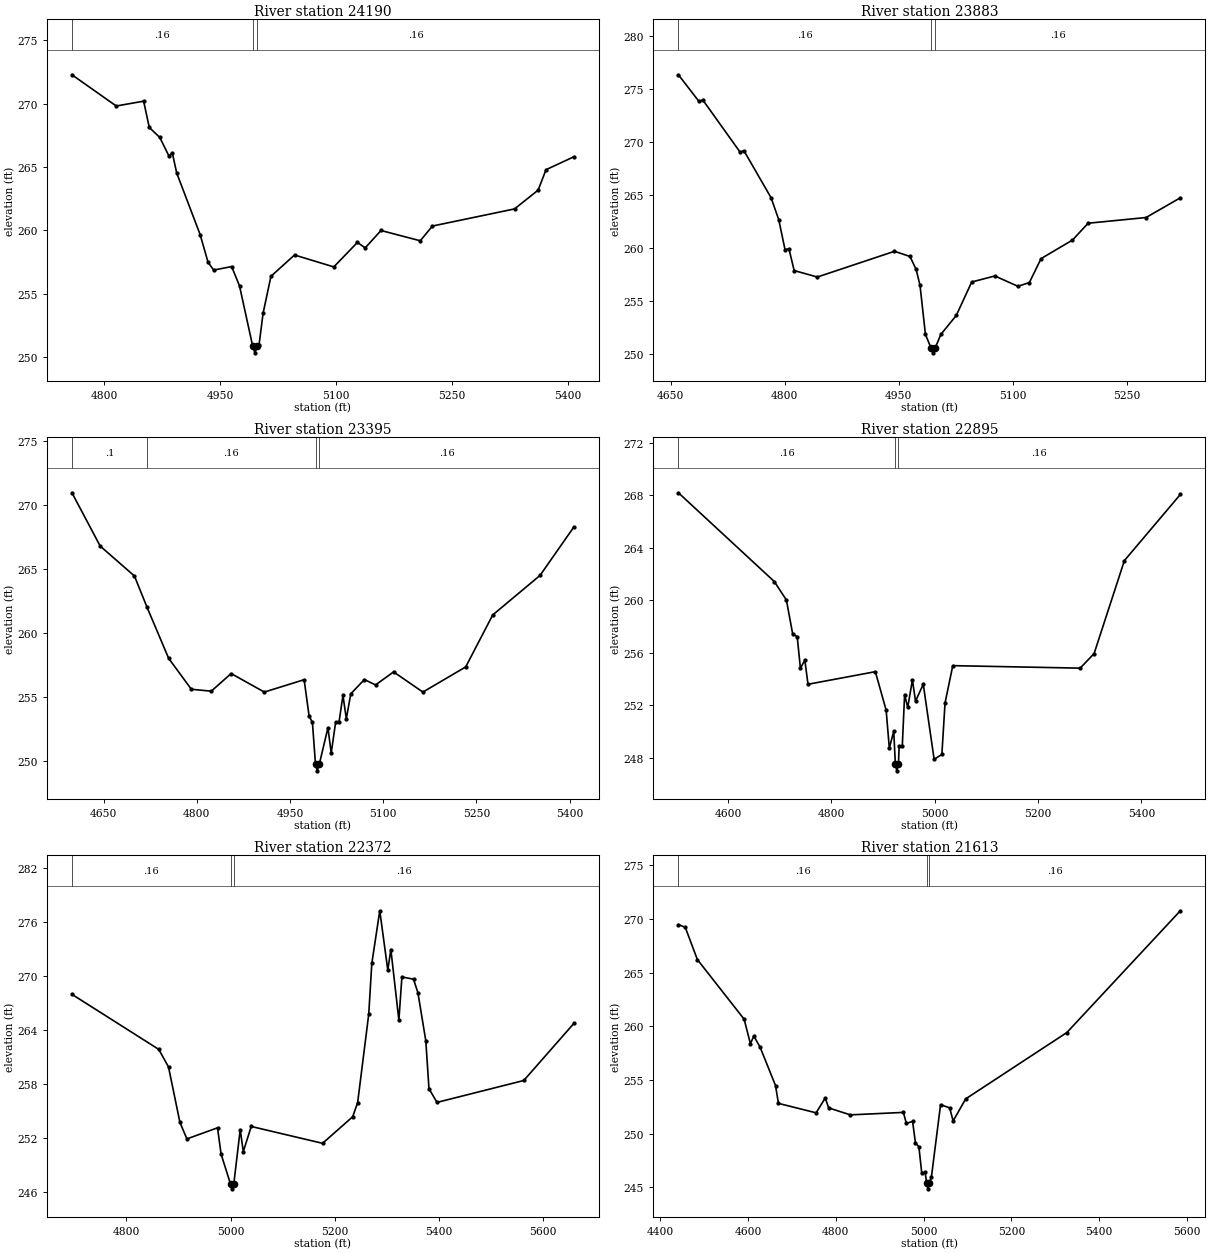
Type RM Length L Ch R = 1 ,24190   ,307,307,307
BEGIN DESCRIPTION:
UNT0505 IN WICK 23.0
END DESCRIPTION:
XS GIS Cut Line= 3
      3588642.12     10248541.63      3588541.33     10248617.22
      3588026.65     10248524.22
#Sta/Elev= 30
  4758.4  272.27  4815.7  269.81  4851.1  270.19  4858.4  268.12    4872  267.33
  4883.9  265.86  4888.2  266.11  4893.8  264.54  4924.2  259.67  4934.4  257.49
  4941.7  256.88  4964.9  257.16  4975.1  255.63  4992.2  250.86    4995  250.36
  4998.2  250.86  5000.3  250.97  5005.5  253.46  5015.7  256.39  5046.2  258.07
    5097  257.13  5127.5  259.06  5137.6  258.63    5158     260  5208.8  259.19
  5224.5  260.35  5330.7   261.7  5361.2  263.18  5371.4  264.79  5407.4  265.81
#Mann= 3 ,-1 , 0
  4758.4     .16       0  4992.2     .07       0  4998.2     .16       0
Bank Sta=4992.2,4998.2
XS Rating Curve= 0 ,0
Exp/Cntr=0.3,0.1

Type RM Length L Ch R = 1 ,23883   ,488,488,488
BEGIN DESCRIPTION:
UNT0505 IN WICK 22.0
END DESCRIPTION:
XS GIS Cut Line= 3
      3588642.11     10248291.64      3588187.37     10248372.05
      3587993.92       10248417.
#Sta/Elev= 30
  4660.1  276.34  4687.2  273.82  4692.2  273.96  4741.3  269.03  4746.3  269.17
    4782  264.73  4792.1  262.66  4800.4  259.82  4805.5  259.91  4812.4  257.85
  4842.9  257.24  4944.4  259.67  4964.8  259.18  4972.9  257.96    4978  256.45
  4985.1  251.83  4992.2  250.58    4995  250.08  4998.2  250.58  5005.4  251.82
  5025.7  253.61    5046  256.77  5076.5  257.34  5106.9  256.36  5121.9  256.72
  5137.3  258.98  5178.6  260.73  5199.2  262.32  5275.4  262.86  5320.5  264.72
#Mann= 3 ,-1 , 0
  4660.1     .16       0  4992.2     .07       0  4998.2     .16       0
Bank Sta=4992.2,4998.2
XS Rating Curve= 0 ,0
Exp/Cntr=0.3,0.1

Type RM Length L Ch R = 1 ,23395   ,500,500,500
BEGIN DESCRIPTION:
UNT0505 IN WICK 21.0
END DESCRIPTION:
XS GIS Cut Line= 3
      3588542.09     10247841.65      3588142.11     10247991.64
      3587792.08     10248141.65
#Sta/Elev= 30
  4598.9  270.98  4644.3  266.81  4699.5  264.46  4719.9     262  4754.6  258.01
  4791.1  255.59  4823.2  255.44  4855.2  256.82  4908.6  255.37  4972.7  256.34
  4980.7  253.48    4986     253    4991   249.7  4993.8   249.2    4997   249.7
    5011  252.57  5016.3  250.59  5023.4  253.01  5028.8  253.01  5035.2  255.11
  5040.6  253.28  5047.8  255.23  5069.6  256.35  5087.7  255.93  5116.7  256.95
  5163.9  255.37  5232.8  257.34  5276.3  261.41  5352.5  264.51  5406.9   268.3
#Mann= 4 ,-1 , 0
  4598.9      .1       0  4719.9     .16       0    4991     .07       0
    4997     .16       0
Bank Sta=4991,4997
XS Rating Curve= 0 ,0
Exp/Cntr=0.3,0.1

Type RM Length L Ch R = 1 ,22895   ,523,523,523
BEGIN DESCRIPTION:
UNT0505 IN WICK 20.0
END DESCRIPTION:
XS GIS Cut Line= 3
      3588292.11     10247291.64      3588042.11     10247641.64
      3587742.08     10248091.68
#Sta/Elev= 30
  4504.2  268.19  4689.8  261.42  4713.1  260.01  4725.4   257.4    4734  257.23
  4740.2  254.82  4748.8  255.42  4754.9  253.59  4885.2  254.55  4906.1  251.61
  4912.2  248.73  4920.8     250  4923.9  247.49  4926.7  246.99  4929.9  247.49
  4931.2  248.86  4937.3  248.86  4941.8  252.81  4947.8  251.82  4956.9  253.92
  4962.9   252.3  4977.9  253.59  4998.9  247.87  5013.9  248.24    5020  252.16
    5035  255.01  5281.4  254.82  5308.4  255.93    5367  263.02  5475.2  268.06
#Mann= 3 ,-1 , 0
  4504.2     .16       0  4923.9     .07       0  4929.9     .16       0
Bank Sta=4923.9,4929.9
XS Rating Curve= 0 ,0
Exp/Cntr=0.3,0.1

Type RM Length L Ch R = 1 ,22372   ,759,759,759
BEGIN DESCRIPTION:
UNT0505 IN WICK 19.0
END DESCRIPTION:
XS GIS Cut Line= 3
      3588221.51     10247169.97      3588058.04       10247203.
      3587380.36      10247623.1
#Sta/Elev= 30
  4695.3  267.96  4862.1  261.85  4880.8   259.9  4902.7  253.75  4916.1  251.92
  4974.9  253.15  4981.8  250.23  5000.1  246.88  5002.8  246.38  5006.1  246.88
  5018.5  252.95  5024.4  250.51  5039.7   253.3  5176.7  251.43  5234.6  254.38
  5244.1  255.95  5265.4  265.76  5271.3  271.39  5286.6  277.23    5302  270.65
  5307.9  272.93  5323.3  265.09  5329.1  269.89  5351.4  269.64  5359.9  268.13
    5375  262.81  5381.1  257.49  5396.5  255.97  5563.2   258.4  5659.4  264.73
#Mann= 3 ,-1 , 0
  4695.3     .16       0  5000.1     .07       0  5006.1     .16       0
Bank Sta=5000.1,5006.1
XS Rating Curve= 0 ,0
Exp/Cntr=0.3,0.1

Type RM Length L Ch R = 1 ,21613   ,218,218,218
BEGIN DESCRIPTION:
UNT0505 IN WICK 18.0
END DESCRIPTION:
XS GIS Cut Line= 3
      3587924.67     10246802.75      3587250.16     10247370.49
      3587192.87      10247625.7
#Sta/Elev= 30
  4441.7  269.49  4457.4  269.22  4484.8  266.23  4591.4  260.67  4605.7  258.39
  4613.5   259.1  4627.8  258.06  4662.9  254.49  4669.5  252.83  4755.3  251.95
  4776.1  253.33  4783.9  252.41  4833.3  251.76  4954.2  251.99  4960.8  250.97
  4975.1  251.15  4981.6  249.15  4989.4  248.79  4995.9  246.36  5003.7   246.4
  5007.2  245.37    5010  244.87  5013.2  245.37    5018  245.98  5038.8  252.71
  5059.6  252.41  5067.4  251.19    5096  253.25  5326.5  259.43  5584.9  270.77
#Mann= 3 ,-1 , 0
  4441.7     .16       0  5007.2     .07       0  5013.2     .16       0
Bank Sta=5007.2,5013.2
XS Rating Curve= 0 ,0
Exp/Cntr=0.3,0.1