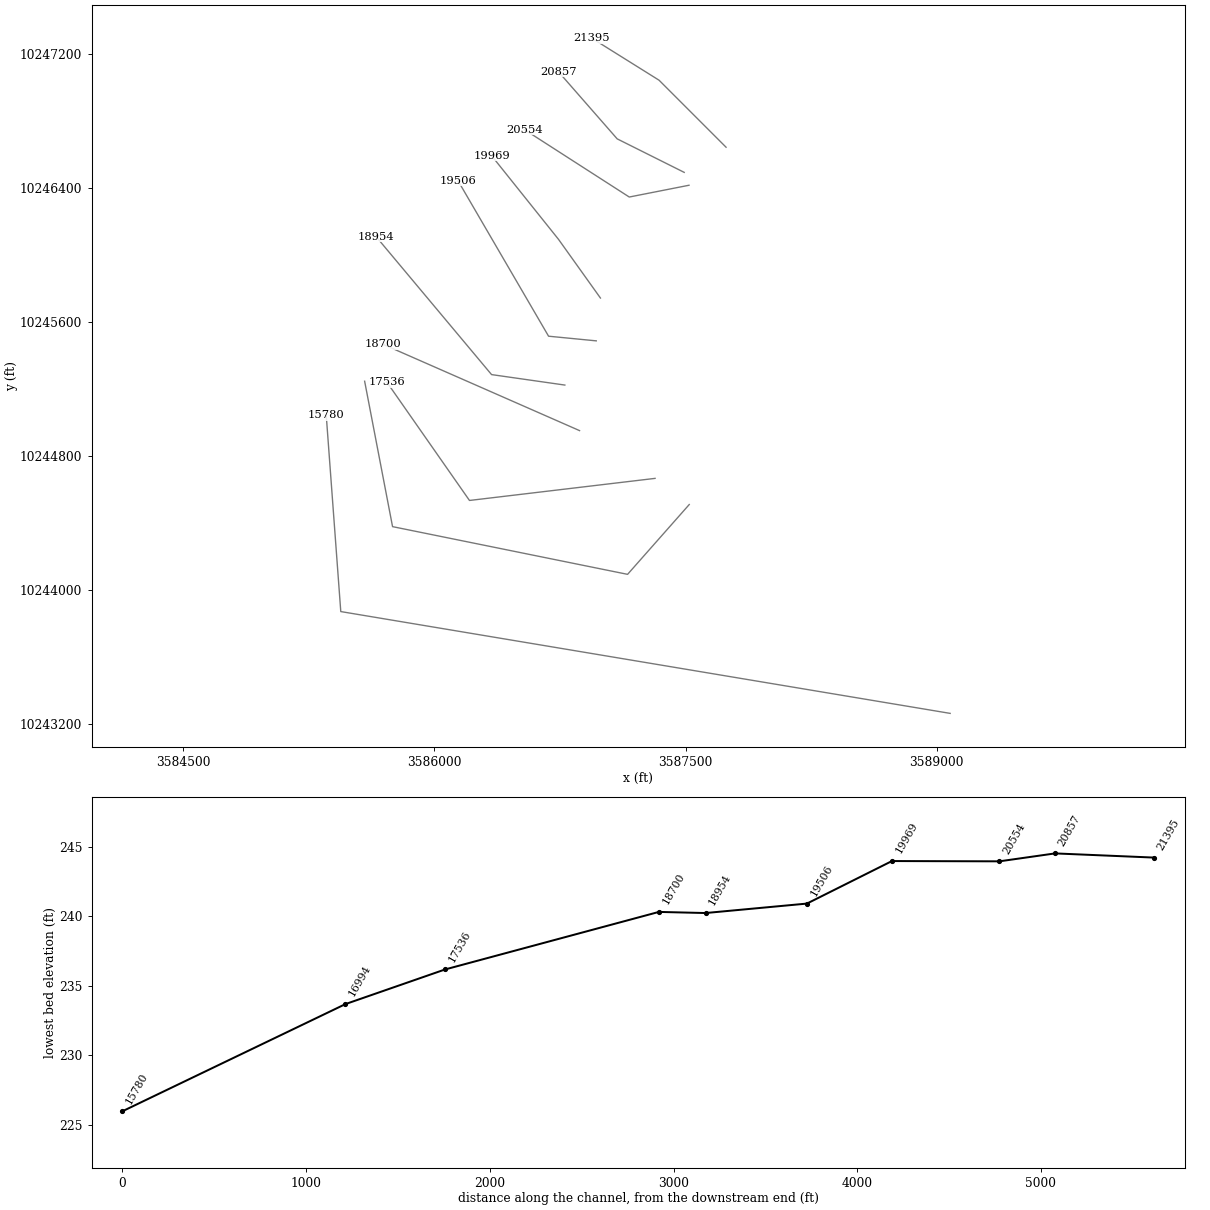
HEC-RAS study WICKSONCREEKTRIB.prj: WICKSON CREEK TRIB 14

--- WICKSONCREEKTRIB.g01 (geometry) --- (continued)

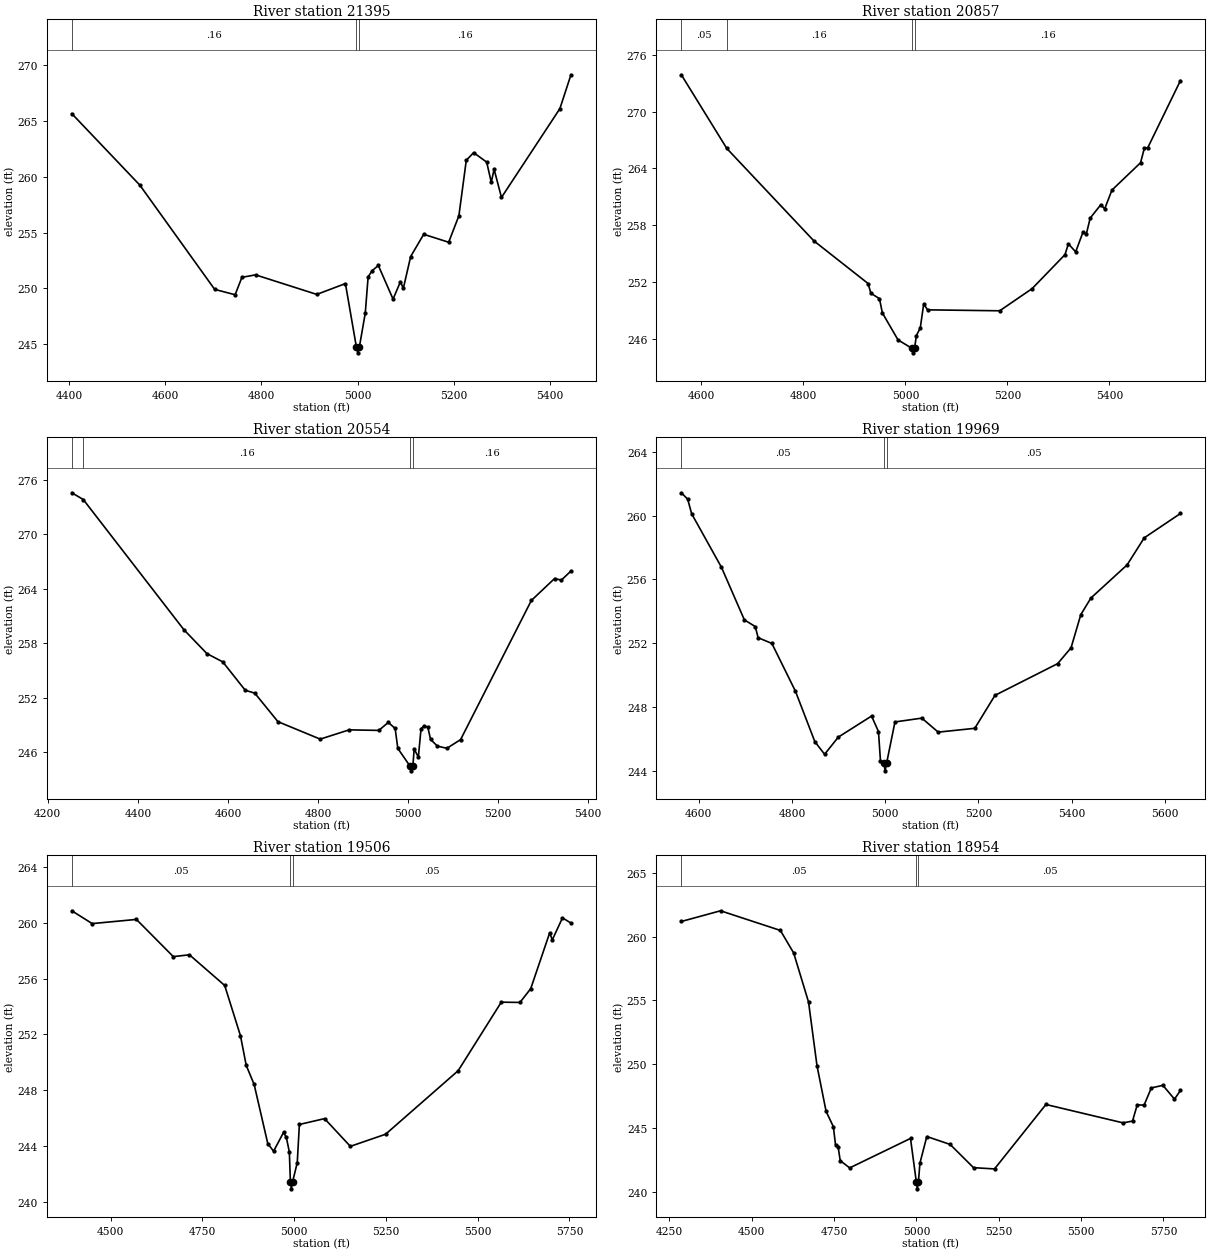
Type RM Length L Ch R = 1 ,21395   ,538,538,538
BEGIN DESCRIPTION:
UNT0505 IN WICK 17.0
END DESCRIPTION:
XS GIS Cut Line= 3
      3587742.08     10246641.67      3587342.11     10247041.64
      3586942.14     10247291.62
#Sta/Elev= 30
  4405.9  265.64  4547.3  259.24  4702.8  249.91  4745.3  249.43  4759.4  250.99
  4787.7  251.21    4915  249.46  4974.5  250.43  4997.4  244.73  5000.2  244.23
  5003.4  244.73  5015.8   247.8  5021.7  251.04  5030.5   251.6  5042.9  252.05
  5073.5  249.04  5088.9   250.6  5094.8  249.99  5110.1  252.85  5137.2  254.84
  5189.1  254.13  5210.3   256.5  5225.7  261.47    5241  262.15  5268.1   261.3
  5277.6   259.5  5283.5  260.66  5298.8  258.14  5420.2  266.09  5443.2  269.12
#Mann= 3 ,-1 , 0
  4405.9     .16       0  4997.4     .07       0  5003.4     .16       0
Bank Sta=4997.4,5003.4
XS Rating Curve= 0 ,0
Exp/Cntr=0.3,0.1

Type RM Length L Ch R = 1 ,20857   ,303,303,303
BEGIN DESCRIPTION:
UNT0505 IN WICK 16.0
END DESCRIPTION:
XS GIS Cut Line= 3
      3587492.15     10246491.62      3587092.11     10246691.64
      3586742.09     10247091.67
#Sta/Elev= 30
  4560.5  273.89  4649.7  266.11  4820.5  256.35  4926.7  251.85  4932.3  250.82
  4949.1  250.25  4954.7  248.75  4985.4   245.9  5011.9  245.03  5014.6  244.53
  5017.9  245.03  5021.5  246.36  5029.1  247.16  5035.8   249.7  5043.4  249.07
  5184.8  248.97  5248.4  251.31  5312.9   254.9  5319.5  256.04  5333.8  255.19
    5348  257.25  5354.7  257.07  5362.3  258.76  5383.1  260.17  5390.7  259.73
    5405  261.72    5461   264.6  5468.6  266.15  5475.2  266.19  5539.3  273.28
#Mann= 4 ,-1 , 0
  4560.5     .05       0  4649.7     .16       0  5011.9     .07       0
  5017.9     .16       0
Bank Sta=5011.9,5017.9
XS Rating Curve= 0 ,0
Exp/Cntr=0.3,0.1

Type RM Length L Ch R = 1 ,20554   ,585,585,585
BEGIN DESCRIPTION:
UNT0505 IN WICK 15.0
END DESCRIPTION:
XS GIS Cut Line= 3
      3587520.96     10246414.76      3587164.22     10246344.45
      3586537.97     10246747.23
#Sta/Elev= 30
  4253.3  274.56  4278.7  273.82    4502   259.5  4553.3  256.86  4588.5  255.95
  4638.3  252.83  4659.5  252.51    4711  249.37  4804.8  247.45  4869.1  248.47
  4934.9  248.41    4956  249.29  4971.2  248.62  4977.1  246.43  5004.5  244.46
  5007.3  243.96  5010.5  244.46  5013.4  246.37  5022.7  245.47  5028.6  248.57
  5035.6  248.93  5043.8  248.75  5049.8  247.42    5065  246.68  5086.1  246.44
  5116.5   247.4  5273.6  262.71  5325.1  265.12  5340.3  264.95  5361.5  265.95
#Mann= 4 ,-1 , 0
  4253.3     .05       0  4278.7     .16       0  5004.5     .07       0
  5010.5     .16       0
Bank Sta=5004.5,5010.5
XS Rating Curve= 0 ,0
Exp/Cntr=0.3,0.1

Type RM Length L Ch R = 1 ,19969   ,463,463,463
BEGIN DESCRIPTION:
UNT0505 IN WICK 14.0
END DESCRIPTION:
XS GIS Cut Line= 3
      3586992.13     10245741.61      3586742.11     10246091.64
      3586342.08     10246591.67
#Sta/Elev= 30
  4562.7  261.44  4576.3  261.04  4584.9  260.12  4648.8  256.76  4697.9  253.46
  4721.3  253.04  4727.4  252.34  4756.9  251.98  4807.3  248.99  4849.1  245.81
    4870  245.02  4899.5   246.1  4970.7  247.42  4985.5  246.45  4989.8  244.62
  4997.1  244.48  4999.8  243.98  5003.1  244.48  5020.9  247.05  5078.5  247.29
  5113.7  246.41  5192.1  246.65  5235.4  248.72  5369.8  250.71  5398.6  251.71
  5419.5  253.79  5441.1  254.83  5518.7  256.91  5555.5  258.61  5633.2  260.14
#Mann= 3 ,-1 , 0
  4562.7     .05       0  4997.1     .03       0  5003.1     .05       0
Bank Sta=4997.1,5003.1
XS Rating Curve= 0 ,0
Exp/Cntr=0.3,0.1

Type RM Length L Ch R = 1 ,19506   ,552,552,552
BEGIN DESCRIPTION:
UNT0505 IN WICK 13.0
END DESCRIPTION:
XS GIS Cut Line= 3
      3586967.31     10245485.95      3586682.63     10245513.72
      3586142.11     10246441.63
#Sta/Elev= 30
  4394.1  260.88  4449.6  259.96  4570.1  260.26  4670.6  257.59  4714.6  257.72
  4810.6  255.52  4853.6  251.91  4869.3  249.78  4890.8  248.42    4928  244.17
  4943.8  243.62    4971  244.97  4978.6  244.61  4986.8  243.56  4989.6  241.42
  4992.3  240.92  4995.6  241.42  5008.3   242.8  5014.1  245.54  5082.7  245.96
    5153  243.97    5249  244.84  5446.7   249.4  5564.2  254.32  5615.1   254.3
  5644.4  255.29  5696.1   259.3  5703.1  258.79  5730.9  260.37    5754     260
#Mann= 3 ,-1 , 0
  4394.1     .05       0  4989.6     .03       0  4995.6     .05       0
Bank Sta=4989.6,4995.6
XS Rating Curve= 0 ,0
Exp/Cntr=0.3,0.1

Type RM Length L Ch R = 1 ,18954   ,254,254,254
BEGIN DESCRIPTION:
UNT0505 IN WICK 11.0
END DESCRIPTION:
XS GIS Cut Line= 3
      3586779.86     10245222.05      3586342.35     10245284.56
      3585653.24     10246107.86
#Sta/Elev= 30
  4285.9  261.19  4404.9  262.03  4586.7  260.49  4627.1  258.72  4672.2  254.88
  4697.8   249.9  4725.5  246.31  4747.6  245.11  4754.1  243.69  4761.9  243.55
  4768.4  242.45  4797.1  241.88  4981.8  244.19  4999.7  240.74  5002.4  240.24
  5005.7  240.74  5010.4  242.25  5031.3  244.34  5102.2  243.72  5173.1   241.9
  5236.9   241.8    5393  246.85  5627.2  245.41  5655.9  245.55  5670.2  246.82
    5691   246.8  5713.1  248.15  5748.2  248.35  5783.4  247.27  5801.5  247.95
#Mann= 3 ,-1 , 0
  4285.9     .05       0  4999.7     .03       0  5005.7     .05       0
Bank Sta=4999.7,5005.7
XS Rating Curve= 0 ,0
Exp/Cntr=0.3,0.1

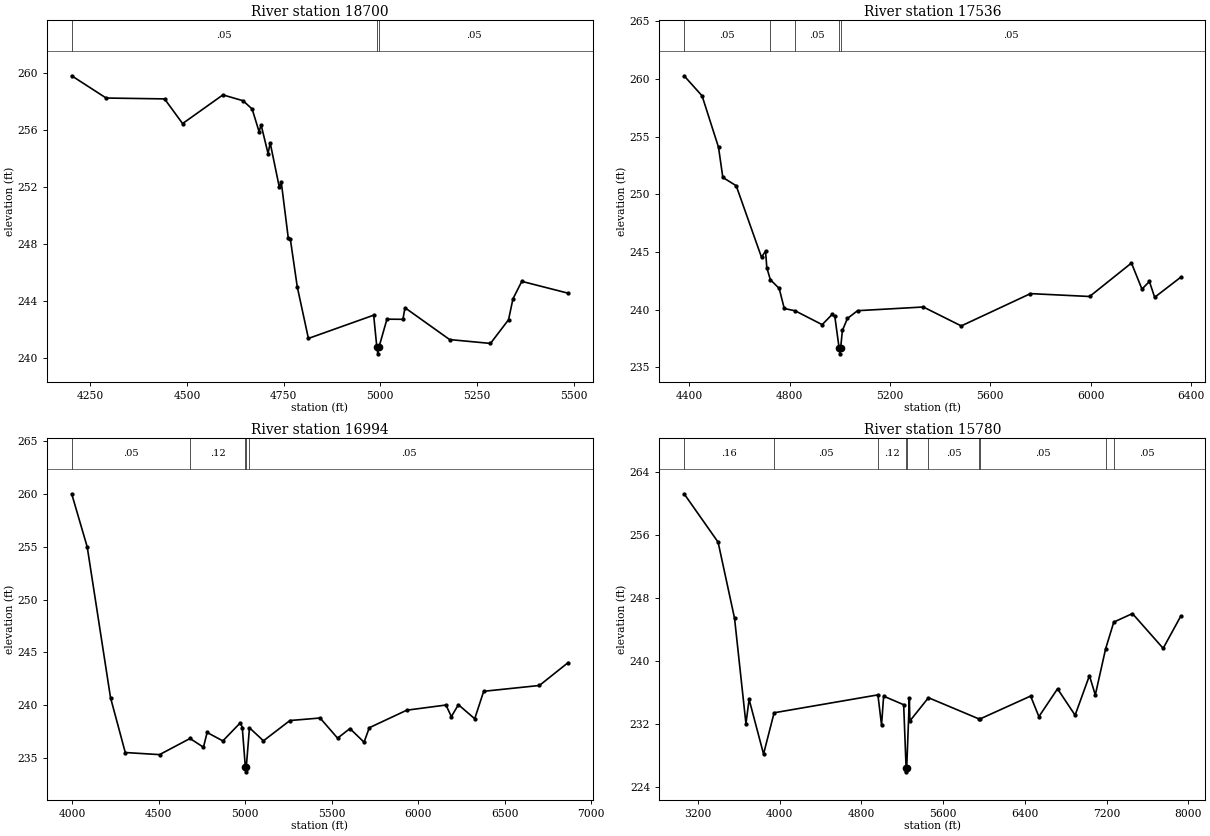
Type RM Length L Ch R = 1 ,18700   ,1164,1164,1164
BEGIN DESCRIPTION:
Mapping XS d22fda5c
END DESCRIPTION:
XS GIS Cut Line= 2
      3586867.52     10244950.22      3585691.33     10245466.71
#Sta/Elev= 30
  4201.6  259.81  4290.8  258.25  4441.9  258.19  4488.6  256.46  4592.9  258.47
  4645.1  258.06  4668.5  257.48  4686.4   255.9  4691.8  256.36  4709.7  254.36
  4715.2  255.11  4738.6  252.03    4744  252.33  4761.9  248.46  4767.4  248.35
  4785.3  245.01  4814.1   241.4    4983  243.03    4991  240.82  4993.7  240.32
    4997  240.82  5017.3  242.75  5058.6  242.74    5064  243.55  5179.5  241.32
  5285.2  241.05  5331.9  242.71  5343.4  244.18  5366.2   245.4  5486.2  244.57
#Mann= 3 ,-1 , 0
  4201.6     .05       0    4991     .03       0    4997     .05       0
Bank Sta=4991,4997
XS Rating Curve= 0 ,0
Exp/Cntr=0.3,0.1

Type RM Length L Ch R = 1 ,17536   ,542,542,542
BEGIN DESCRIPTION:
Mapping XS 68cbe25d
END DESCRIPTION:
XS GIS Cut Line= 3
       3587318.2      10244665.1      3586210.55      10244533.3
      3585717.01     10245239.96
#Sta/Elev= 30
  4380.2  260.28  4451.8  258.54  4517.3  254.08  4534.4  251.47  4587.7  250.75
  4688.5  244.55  4704.6  245.09  4709.6  243.65  4723.6  242.61  4758.9  241.85
  4779.1  240.11  4822.5  239.91  4930.1  238.71  4970.4  239.61  4980.5  239.42
  4997.6  236.68  5000.4  236.18  5003.6  236.68  5010.7  238.21  5030.8  239.25
  5071.1  239.92    5333  240.24    5484   238.6  5759.8   241.4  5995.3  241.15
  6161.9  244.05  6203.7  241.79  6233.4  242.45  6254.3  241.08  6357.6  242.81
#Mann= 5 ,-1 , 0
  4380.2     .05       0  4723.6     .16       0  4822.5     .05       0
  4997.6     .03       0  5003.6     .05       0
Bank Sta=4997.6,5003.6
XS Rating Curve= 0 ,0
Exp/Cntr=0.3,0.1

Type RM Length L Ch R = 1 ,16994   ,1214,1214,1214
BEGIN DESCRIPTION:
Mapping XS 7badab10
END DESCRIPTION:
XS GIS Cut Line= 4
      3587522.24     10244508.99      3587154.19     10244092.34
      3585751.41     10244377.06      3585584.75     10245245.09
#Sta/Elev= 30
  3995.9  260.03  4085.8  254.99  4220.5  240.72  4305.8  235.52  4504.1  235.32
  4680.5  236.85    4758  236.02  4779.1  237.42  4870.2  236.62  4971.4  238.34
  4982.5  237.89  4999.9  234.19  5002.7  233.69  5005.9  234.19  5024.1  237.86
    5105  236.63    5258  238.55  5432.4  238.79  5533.7  236.88    5605  237.79
  5686.6   236.5  5717.2  237.87  5933.7  239.53  6160.5  240.02  6191.5  238.92
  6232.3  240.05  6326.6  238.72  6378.6  241.32  6700.7  241.87  6867.1  244.04
#Mann= 5 ,-1 , 0
  3995.9     .05       0  4680.5     .12       0  4999.9     .07       0
  5005.9     .12       0  5024.1     .05       0
Bank Sta=4999.9,5005.9
XS Rating Curve= 0 ,0
Exp/Cntr=0.3,0.1

Type RM Length L Ch R = 1 ,15780   ,0,0,0
BEGIN DESCRIPTION:
UNT0505 IN WICK 1.0
END DESCRIPTION:
XS GIS Cut Line= 3
       3589079.5     10243262.48      3585442.38     10243870.11
      3585355.58     10245041.98
#Sta/Elev= 30
    3063  261.24  3395.8  255.11  3557.1  245.45  3668.7  232.08  3699.6  235.17
    3841  228.24  3944.6  233.47  4961.2  235.74  4996.8   231.9  5017.1  235.58
  5213.5  234.49  5237.2  226.48  5239.9  225.98  5243.2  226.48  5269.2  235.28
  5274.3  232.43  5456.1  235.38  5947.4  232.71  5958.3  232.67  6456.8  235.59
  6537.9  232.98  6720.4  236.51  6892.4  233.16  7032.8  238.18  7090.3  235.73
  7191.2  241.57  7271.3  244.97    7454  246.05  7754.8  241.64  7925.6  245.68
#Mann= 10 ,-1 , 0
    3063     .16       0  3944.6     .05       0  4961.2     .12       0
  5237.2     .07       0  5243.2     .12       0  5456.1     .05       0
  5947.4     .12       0  5958.3     .05       0  7191.2     .16       0
  7271.3     .05       0
Bank Sta=5237.2,5243.2
XS Rating Curve= 0 ,0
Exp/Cntr=0.3,0.1

Chan Stop Cuts=-1
Use User Specified Reach Order=0
Composite Channel Slope=5