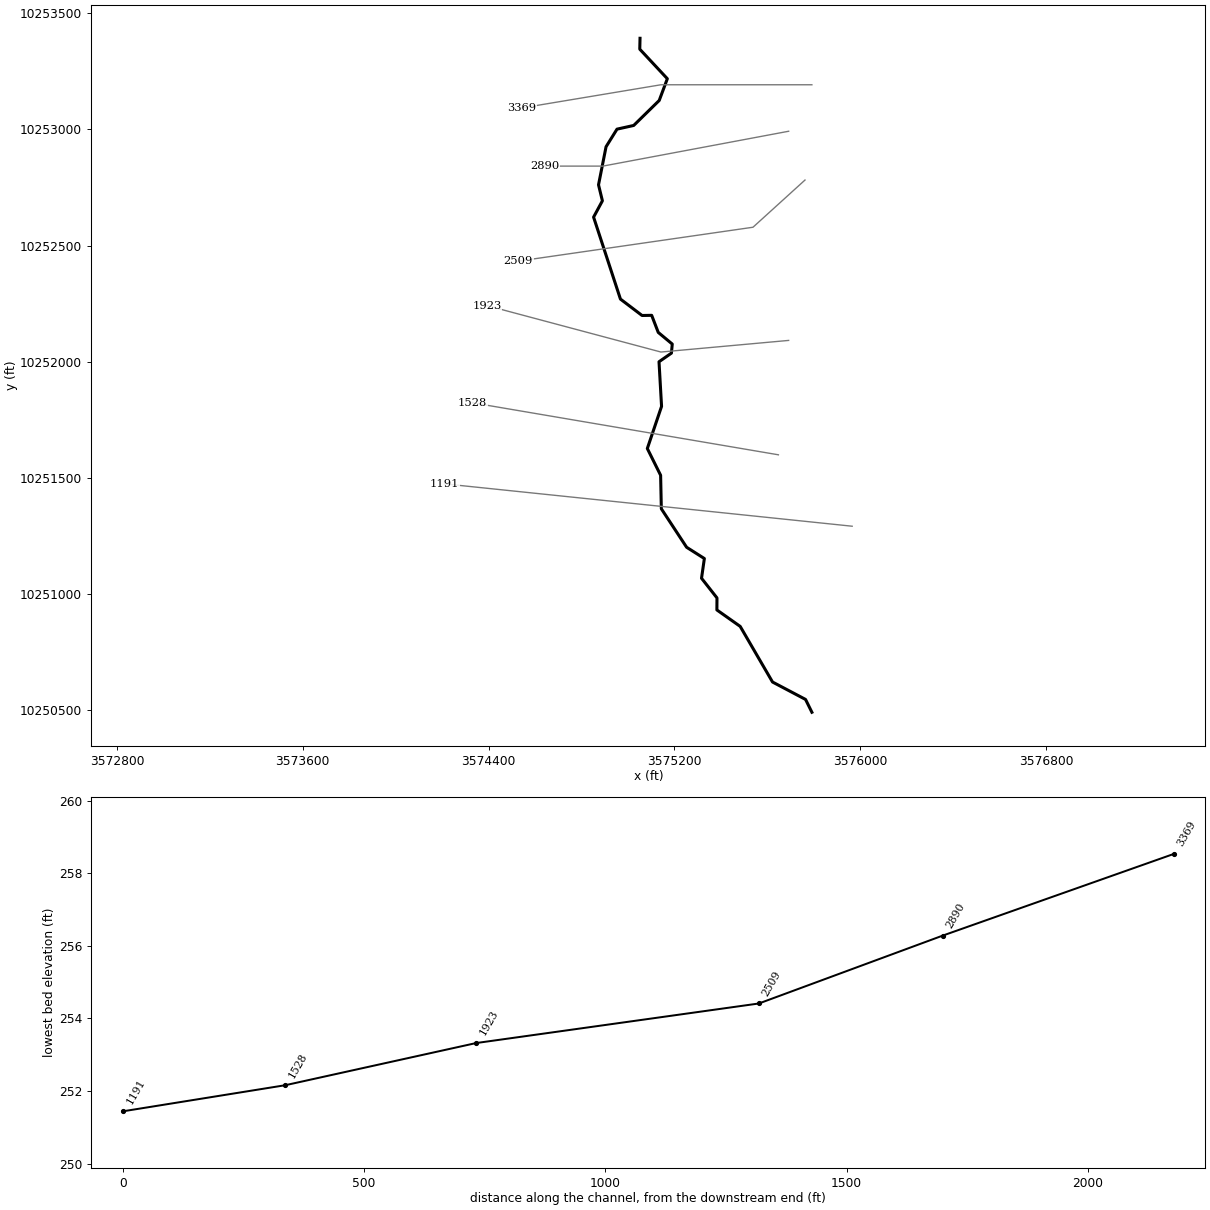
--- WICKSONCREEKTRIB.prj (project) ---

Proj Title=WICKSON CREEK TRIB 19
Current Plan=p01
Default Exp/Contr=0.3,0.1
English Units
Geom File=g01
Flow File=f01
Plan File=p01
Y Axis Title=Elevation
X Axis Title(PF)=Main Channel Distance
X Axis Title(XS)=Station
BEGIN DESCRIPTION:
UNT0503 IN WICK
END DESCRIPTION:
DSS Export Rating Curves= 0
DSS Export Rating Curve Sorted= 0
DSS Export Volume Flow Curves= 0
DXF OffsetX= 0
DXF OffsetY= 0
DXF ScaleX= 1
DXF ScaleY= 10

--- WICKSONCREEKTRIB.p01 (plan) ---

Plan Title=Multiple Run
Short Identifier=Multiple
Geom File=g01
Flow File=f01
Subcritical Flow
K Sum by GR= 0
Std Step Tol= 0.01
Critical Tol= 0.01
Num of Std Step Trials= 20
Max Error Tol= 0.3
Flow Tol Ratio= 0.001
Split Flow NTrial= 30
Split Flow Tol= 0.02
Split Flow Ratio= 0.02
Log Output Level= 0
Friction Slope Method= 1
Unsteady Friction Slope Method= 2
Unsteady Bridges Friction Slope Method= 1
Parabolic Critical Depth
Global Vel Dist=  1 , 1 , 1
Global Log Level= 0
CheckData=True
Encroach Param= -1, 0, 0, 0
BEGIN DESCRIPTION:
Multiple Run
END DESCRIPTION:

--- WICKSONCREEKTRIB.f01 (steady flow) ---

Flow Title=Multiple
Program Version=4.10
Number of Profiles= 7
Profile Names=10-year,25-year,50-year,1pct_min,100-year,1pct_plu,500-year
River Rch & RM=UNT0503 IN WICK,Reach-1         ,3369
     724     983    1195    1064    1439    1946    2090
River Rch & RM=WICKSONCRTR19,Reach-1         ,3369
     724     983    1195    1064    1439    1946    2090
Boundary for River Rch & Prof#=WICKSONCRTR19,Reach-1         , 1
Up Type= 0
Dn Type= 3
Dn Slope=0.005
Boundary for River Rch & Prof#=WICKSONCRTR19,Reach-1         , 2
Up Type= 0
Dn Type= 3
Dn Slope=0.005
Boundary for River Rch & Prof#=WICKSONCRTR19,Reach-1         , 3
Up Type= 0
Dn Type= 3
Dn Slope=0.005
Boundary for River Rch & Prof#=WICKSONCRTR19,Reach-1         , 4
Up Type= 0
Dn Type= 3
Dn Slope=0.005
Boundary for River Rch & Prof#=WICKSONCRTR19,Reach-1         , 5
Up Type= 0
Dn Type= 3
Dn Slope=0.005
Boundary for River Rch & Prof#=WICKSONCRTR19,Reach-1         , 6
Up Type= 0
Dn Type= 3
Dn Slope=0.005
Boundary for River Rch & Prof#=WICKSONCRTR19,Reach-1         , 7
Up Type= 0
Dn Type= 3
Dn Slope=0.005
DSS Import GetInterval= 0
DSS Import GetPeak= 0
DSS Import FillOption= 0

--- WICKSONCREEKTRIB.g01 (geometry) ---

Geom Title=Existing Conditions
Program Version=4.10

River Reach=WICKSONCRTR19   ,Reach-1
Reach XY= 30
      3575052.11     10253391.64      3575051.03     10253344.78
      3575169.74     10253217.62      3575134.73     10253124.04
      3575024.93     10253016.57      3574953.01     10253000.67
      3574905.83     10252924.86       3574873.4     10252761.01
      3574890.13     10252692.29      3574852.17     10252622.07
      3574967.81     10252269.44      3575060.86     10252198.89
       3575102.3     10252199.59      3575130.61     10252126.06
      3575190.88     10252075.98       3575187.3     10252036.89
       3575133.9     10251999.84      3575144.84     10251807.78
      3575083.54     10251626.53      3575140.78      10251511.4
      3575143.87     10251367.22      3575252.68     10251201.64
      3575329.14     10251153.12      3575316.91     10251068.29
      3575383.45     10250983.61      3575383.06      10250931.9
      3575483.45     10250861.05      3575622.64     10250621.78
      3575764.83     10250546.85      3575792.11     10250491.64

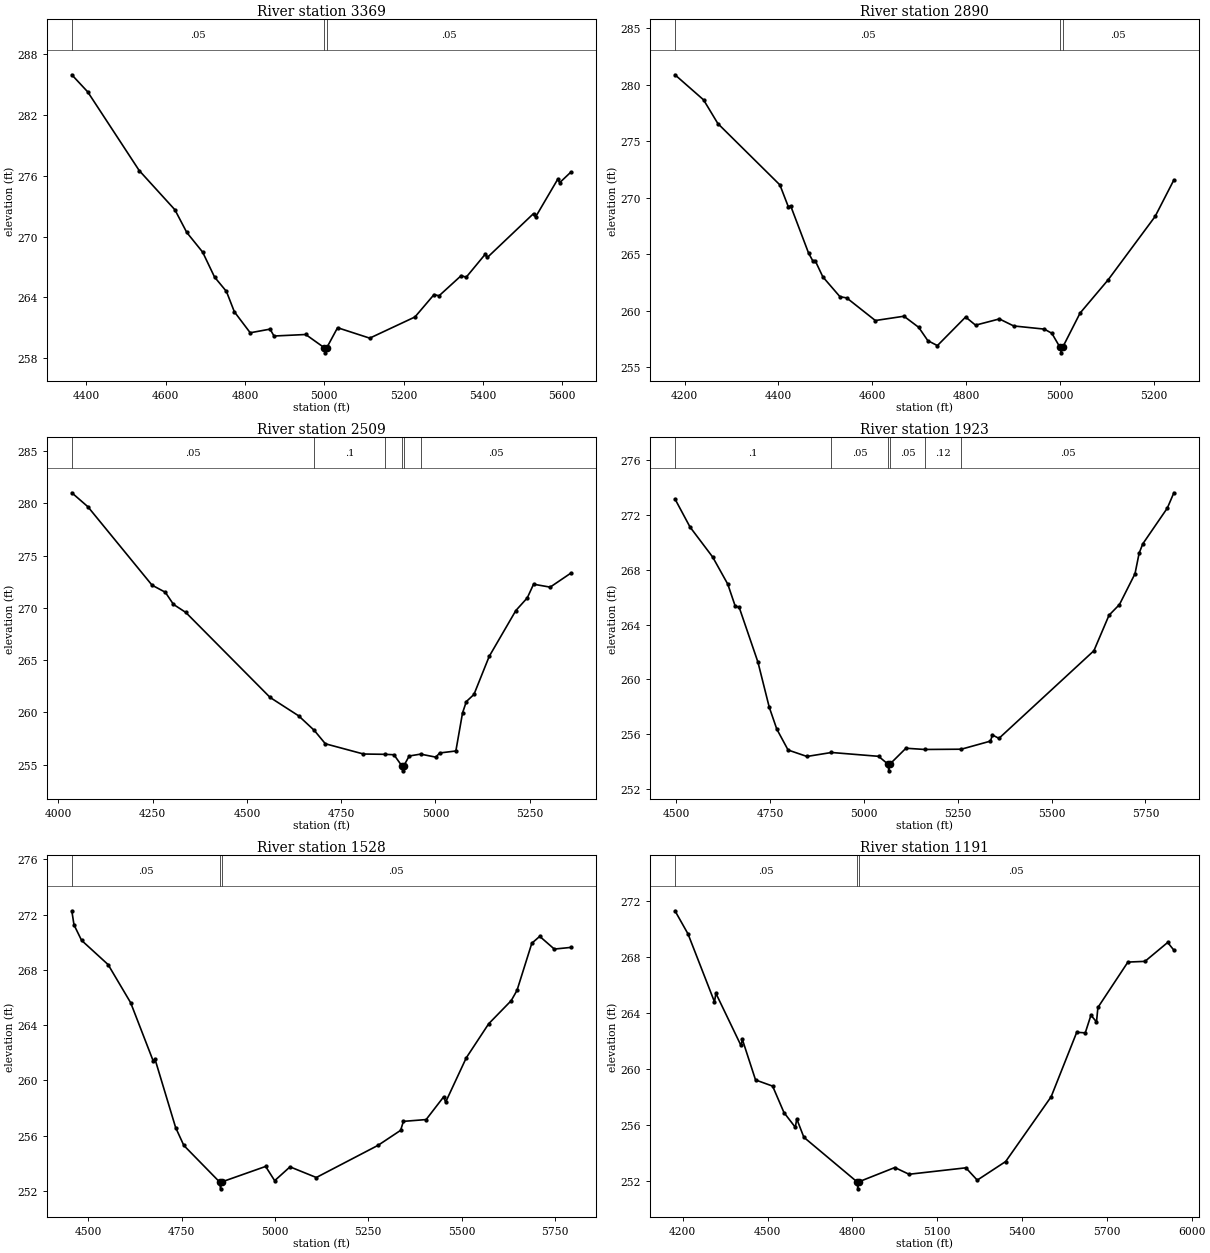
Type RM Length L Ch R = 1 ,3369    ,479,479,479
BEGIN DESCRIPTION:
UNT0503 IN WICK 7.0
END DESCRIPTION:
XS GIS Cut Line= 3
      3575792.15     10253191.64      3575142.11     10253191.64
      3574542.13     10253091.65
#Sta/Elev= 30
  4363.2  285.97  4403.2  284.29  4533.2  276.52  4623.2  272.65  4653.2  270.41
  4693.2  268.47  4723.2  266.01  4753.2  264.59  4773.2  262.58  4813.2  260.51
  4863.2  260.87  4873.2  260.19  4953.2  260.34  5000.2  259.03    5003  258.53
  5006.2  259.03  5033.5  261.01  5114.6  259.98  5228.7  262.07  5276.8  264.28
  5289.5  264.16  5345.3  266.15  5357.9  265.99  5406.1  268.27  5411.2  267.94
  5527.7  272.27  5532.8  271.93  5588.6  275.65  5593.6  275.32  5621.5  276.35
#Mann= 3 ,-1 , 0
  4363.2     .05       0  5000.2     .03       0  5006.2     .05       0
Bank Sta=5000.2,5006.2
XS Rating Curve= 0 ,0
Exp/Cntr=0.3,0.1

Type RM Length L Ch R = 1 ,2890    ,381,381,381
BEGIN DESCRIPTION:
UNT0503 IN WICK 6.0
END DESCRIPTION:
XS GIS Cut Line= 3
      3575692.08     10252991.64      3574892.11     10252841.64
      3574642.12     10252841.64
#Sta/Elev= 30
  4179.4  280.89  4240.4  278.67  4270.9  276.57  4403.2  271.14    4421  269.22
  4426.1  269.29  4464.3  265.11  4473.6   264.4  4478.7  264.41  4494.8     263
  4531.2  261.25  4545.7  261.14  4606.7  259.14  4667.7  259.52  4699.1  258.54
  4718.6  257.36    4739  256.92  4799.2  259.45  4820.4  258.73  4871.2  259.28
  4901.7  258.66    4967  258.38  4983.1  258.01  5000.3  256.78  5003.1  256.28
  5006.3  256.78  5043.3   259.8  5103.3  262.75  5203.3  268.35  5243.3  271.58
#Mann= 3 ,-1 , 0
  4179.4     .05       0  5000.3     .03       0  5006.3     .05       0
Bank Sta=5000.3,5006.3
XS Rating Curve= 0 ,0
Exp/Cntr=0.3,0.1

Type RM Length L Ch R = 1 ,2509    ,586,586,586
BEGIN DESCRIPTION:
UNT0503 IN WICK 5.0
END DESCRIPTION:
XS GIS Cut Line= 3
      3575762.47     10252781.72      3575538.53     10252578.61
      3574528.13     10252432.78
#Sta/Elev= 30
  4035.6  281.02  4078.1  279.69  4248.4  272.18  4283.6   271.5  4305.2  270.34
  4337.9  269.57  4561.7  261.43  4637.4  259.67  4678.7  258.28  4708.1     257
  4809.2  256.02  4865.9  255.99    4890  255.95  4910.5  254.91  4913.2  254.41
  4916.5  254.91  4930.4  255.83  4960.7  256.01  5001.2  255.72  5011.3  256.12
  5054.2  256.31  5071.9  259.95    5082  261.04  5102.2  261.72  5142.6  265.36
  5213.3  269.75  5243.6  270.96  5260.3  272.27  5304.3  271.99  5358.8  273.32
#Mann= 6 ,-1 , 0
  4035.6     .05       0  4678.7      .1       0  4865.9     .12       0
  4910.5     .03       0  4916.5     .12       0  4960.7     .05       0
Bank Sta=4910.5,4916.5
XS Rating Curve= 0 ,0
Exp/Cntr=0.3,0.1

Type RM Length L Ch R = 1 ,1923    ,395,395,395
BEGIN DESCRIPTION:
UNT0503 IN WICK 4.0
END DESCRIPTION:
XS GIS Cut Line= 3
      3575692.09     10252091.64      3575142.11     10252041.64
      3574392.06     10252241.65
#Sta/Elev= 30
  4497.2  273.17  4537.3  271.12  4597.6  268.93  4637.8  266.95  4657.8  265.33
  4667.9  265.28  4718.1  261.26  4748.2  257.97  4768.3  256.37  4798.4  254.84
  4848.6  254.37    4914  254.66  5039.4  254.38  5063.9  253.82  5066.7  253.32
  5069.9  253.82  5112.2  254.97  5162.4  254.88  5259.7   254.9  5337.3  255.49
  5342.5  255.94  5359.9  255.69  5612.8  262.09    5653  264.68  5680.8  265.46
  5722.2  267.71  5733.2  269.21  5742.9  269.89  5808.2   272.5  5825.7  273.62
#Mann= 6 ,-1 , 0
  4497.2      .1       0    4914     .05       0  5063.9    .035       0
  5069.9     .05       0  5162.4     .12       0  5259.7     .05       0
Bank Sta=5063.9,5069.9
XS Rating Curve= 0 ,0
Exp/Cntr=0.3,0.1

Type RM Length L Ch R = 1 ,1528    ,337,337,337
BEGIN DESCRIPTION:
UNT0503 IN WICK 2.0
END DESCRIPTION:
XS GIS Cut Line= 2
      3575647.94     10251599.44      3574330.23     10251823.39
#Sta/Elev= 30
  4455.9  272.27  4461.8  271.25  4482.1  270.13  4553.1  268.38  4613.6  265.62
  4673.8  261.42  4678.9  261.53  4734.1  256.59    4756   255.3  4851.7  252.66
  4854.4  252.16  4857.7  252.66  4975.2  253.78  4999.4  252.75  5040.5  253.75
    5111  252.98  5276.6  255.31  5336.8  256.39  5344.3  257.04  5405.2  257.17
  5452.3  258.82  5457.4  258.43  5512.6  261.63  5572.8   264.1  5633.1  265.77
  5648.6  266.51  5688.3  269.92  5709.5  270.42  5748.6   269.5  5792.5  269.62
#Mann= 3 ,-1 , 0
  4455.9     .05       0  4851.7     .03       0  4857.7     .05       0
Bank Sta=4851.7,4857.7
XS Rating Curve= 0 ,0
Exp/Cntr=0.3,0.1

Type RM Length L Ch R = 1 ,1191    ,0,0,0
BEGIN DESCRIPTION:
UNT0503 IN WICK 1.0
END DESCRIPTION:
XS GIS Cut Line= 2
      3575965.61     10251292.15      3574210.35     10251474.45
#Sta/Elev= 30
  4172.4  271.28  4218.5  269.63  4312.2  264.78  4317.2  265.39  4405.8  261.67
  4410.8   262.1  4457.4  259.21  4517.8  258.77    4558  256.88  4598.1  255.83
  4603.2  256.43  4628.3  255.12  4816.4  251.94  4819.1  251.44  4822.4  251.94
  4950.1  252.96  5000.3  252.48  5201.4  252.94  5241.6  252.06  5342.2  253.39
    5503  258.01  5593.5  262.61  5623.7  262.57  5643.8  263.83  5663.4  263.35
  5668.4  264.38  5774.5  267.62  5834.8  267.67  5915.2  269.02  5937.1  268.47
#Mann= 3 ,-1 , 0
  4172.4     .05       0  4816.4    .035       0  4822.4     .05       0
Bank Sta=4816.4,4822.4
XS Rating Curve= 0 ,0
Exp/Cntr=0.3,0.1

Chan Stop Cuts=-1
Use User Specified Reach Order=0
Composite Channel Slope=5