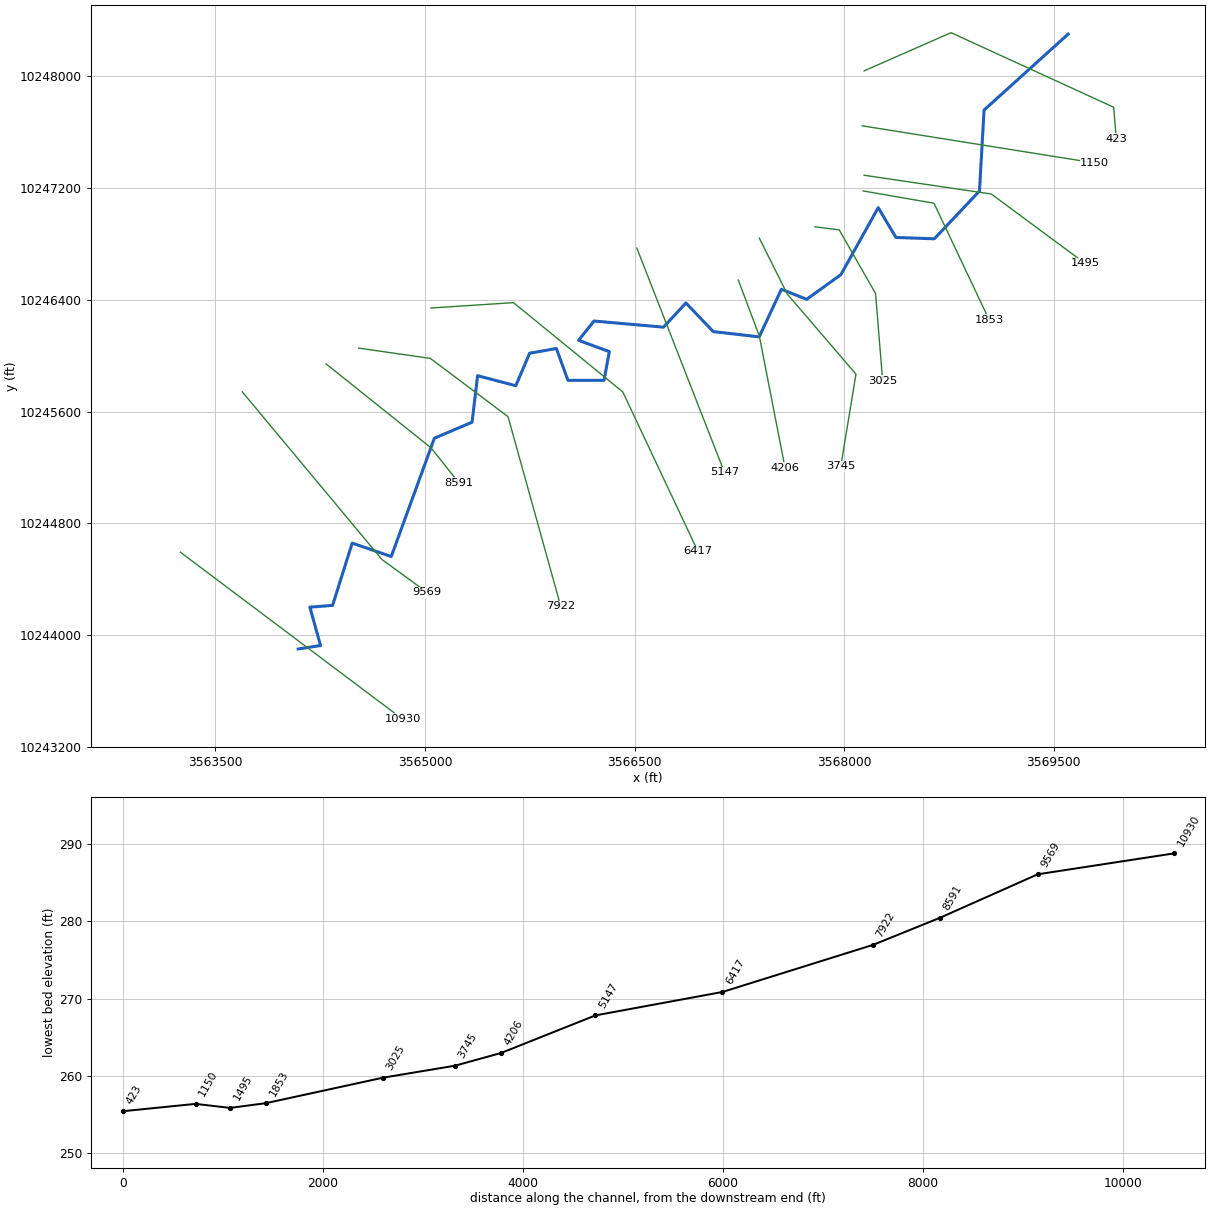
--- WICKSONCREEKTRIB.prj (project) ---

Proj Title=WICKSON CREEK TRIB 22
Current Plan=p01
Default Exp/Contr=0.3,0.1
English Units
Geom File=g01
Flow File=f01
Plan File=p01
Y Axis Title=Elevation
X Axis Title(PF)=Main Channel Distance
X Axis Title(XS)=Station
BEGIN DESCRIPTION:
UNT0500 IN WICK
END DESCRIPTION:
DSS Export Rating Curves= 0
DSS Export Rating Curve Sorted= 0
DSS Export Volume Flow Curves= 0
DXF Filename=UNT0500 IN WICK.
DXF OffsetX= 0
DXF OffsetY= 0
DXF ScaleX= 1
DXF ScaleY= 10

--- WICKSONCREEKTRIB.p01 (plan) ---

Plan Title=Multiple Run
Short Identifier=Multiple
Geom File=g01
Flow File=f01
Subcritical Flow
K Sum by GR= 0
Std Step Tol= 0.01
Critical Tol= 0.01
Num of Std Step Trials= 20
Max Error Tol= 0.3
Flow Tol Ratio= 0.001
Split Flow NTrial= 30
Split Flow Tol= 0.02
Split Flow Ratio= 0.02
Log Output Level= 0
Friction Slope Method= 1
Unsteady Friction Slope Method= 2
Unsteady Bridges Friction Slope Method= 1
Parabolic Critical Depth
Global Vel Dist=  1 , 1 , 1
Global Log Level= 0
CheckData=True
Encroach Param= -1, 0, 0, 0
BEGIN DESCRIPTION:
Multiple Run
END DESCRIPTION:

--- WICKSONCREEKTRIB.f01 (steady flow) ---

Flow Title=Multiple
Program Version=4.10
Number of Profiles= 7
Profile Names=10-year,25-year,50-year,1pct_min,100-year,1pct_plu,500-year
River Rch & RM=UNT0500 IN WICK,Reach-1         ,10930
     866    1186    1449    1296    1752    2370    2569
River Rch & RM=WICKSONCRTRB22,Reach-1         ,10930
     866    1186    1449    1296    1752    2370    2569
Boundary for River Rch & Prof#=WICKSONCRTRB22,Reach-1         , 1
Up Type= 0
Dn Type= 3
Dn Slope=0.005
Boundary for River Rch & Prof#=WICKSONCRTRB22,Reach-1         , 2
Up Type= 0
Dn Type= 3
Dn Slope=0.005
Boundary for River Rch & Prof#=WICKSONCRTRB22,Reach-1         , 3
Up Type= 0
Dn Type= 3
Dn Slope=0.005
Boundary for River Rch & Prof#=WICKSONCRTRB22,Reach-1         , 4
Up Type= 0
Dn Type= 3
Dn Slope=0.005
Boundary for River Rch & Prof#=WICKSONCRTRB22,Reach-1         , 5
Up Type= 0
Dn Type= 3
Dn Slope=0.005
Boundary for River Rch & Prof#=WICKSONCRTRB22,Reach-1         , 6
Up Type= 0
Dn Type= 3
Dn Slope=0.005
Boundary for River Rch & Prof#=WICKSONCRTRB22,Reach-1         , 7
Up Type= 0
Dn Type= 3
Dn Slope=0.005
DSS Import GetInterval= 0
DSS Import GetPeak= 0
DSS Import FillOption= 0

--- WICKSONCREEKTRIB.g01 (geometry) ---

Geom Title=Existing Conditions
Program Version=4.10

River Reach=WICKSONCRTRB22  ,Reach-1
Reach XY= 30
      3564092.11     10243901.64      3564252.19     10243926.34
      3564175.87      10244200.9      3564338.25     10244213.44
      3564478.74      10244659.1      3564758.32     10244563.39
      3565066.85     10245409.94      3565336.36     10245524.42
       3565376.3     10245857.19      3565649.62     10245785.52
      3565748.42     10246018.07       3565939.9     10246051.79
       3566022.8     10245823.94      3566281.09     10245824.29
      3566318.73     10246029.49      3566098.81     10246110.45
      3566209.02     10246248.49      3566706.39      10246204.6
      3566866.97     10246377.86      3567062.41     10246172.92
      3567391.08     10246135.11      3567550.38     10246475.84
      3567730.96     10246403.85        3567976.     10246580.45
      3568243.05     10247059.96      3568369.94     10246846.47
      3568644.67     10246836.99      3568967.75     10247178.85
      3569000.42     10247758.18      3569602.11     10248301.64

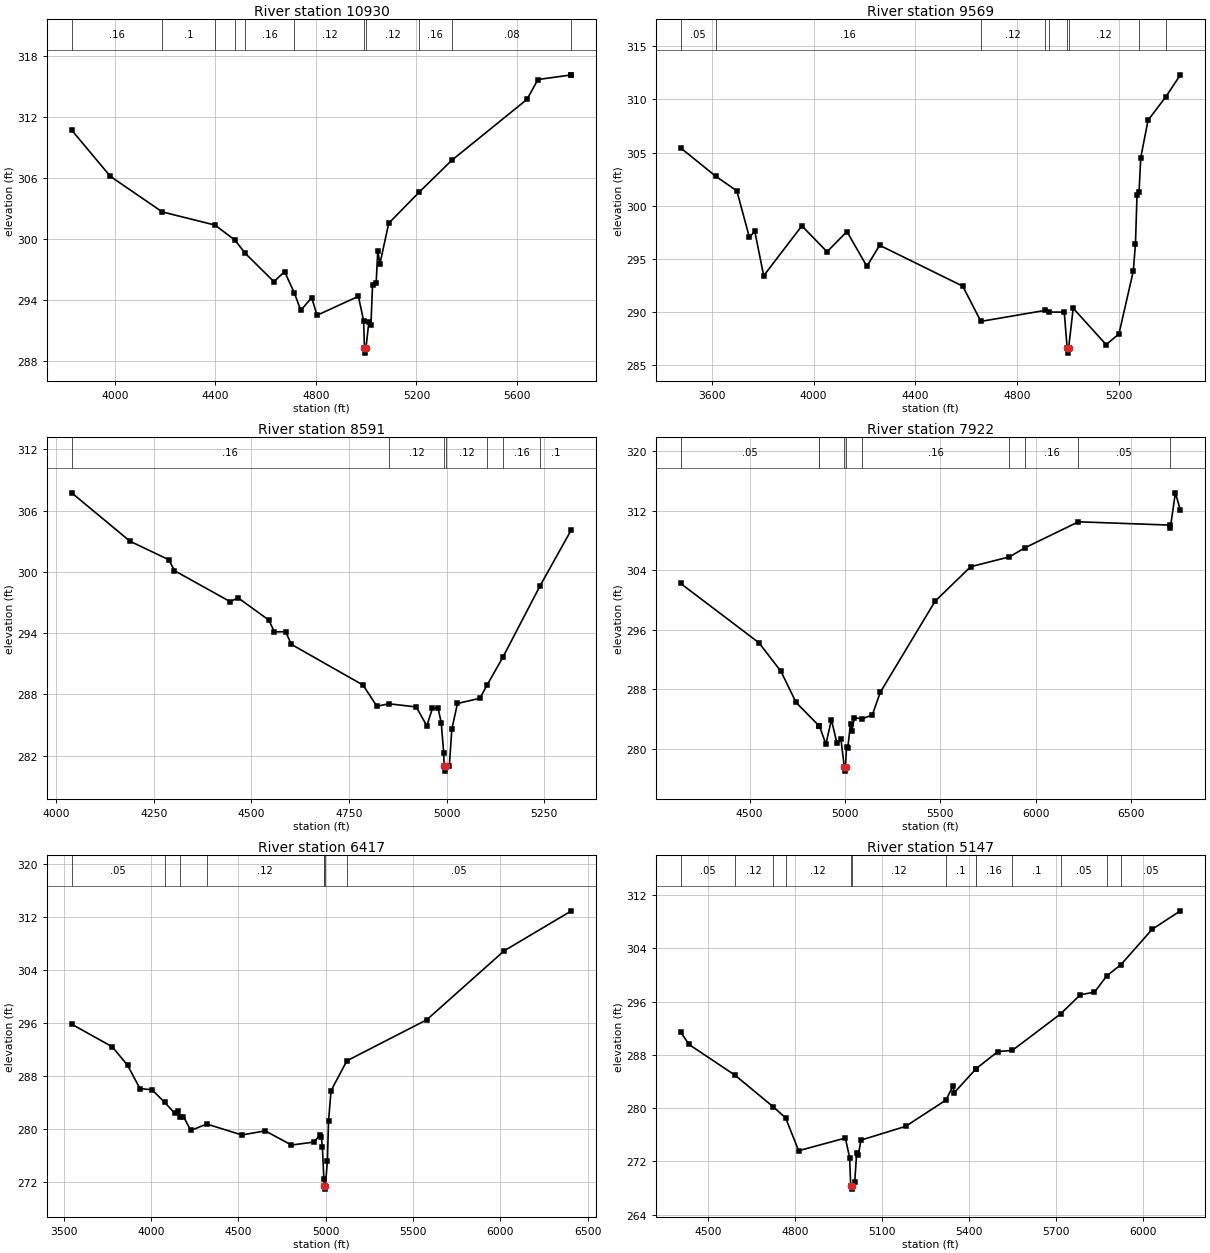
Type RM Length L Ch R = 1 ,10930   ,1361,1361,1361
BEGIN DESCRIPTION:
UNT0500 IN WICK 18.0
END DESCRIPTION:
XS GIS Cut Line= 2
      3563248.78     10244594.44      3564838.48     10243400.21
#Sta/Elev= 30
  3828.7  310.71  3982.9  306.16  4189.4  302.67    4399  301.38  4478.8  299.89
  4518.5  298.62  4633.3  295.82  4675.6  296.81  4714.5  294.71  4740.2     293
  4783.4  294.26  4804.8  292.52  4969.3  294.38  4990.1  291.99  4993.4   289.3
  4996.1   288.8  4999.4   289.3    5011  291.89  5019.3   291.6  5025.5  295.45
  5040.1  295.71  5046.4  298.88  5054.7  297.55  5090.1  301.56  5209.8  304.58
  5341.1  307.75    5640  313.73  5683.7  315.68  5816.4  316.13    5817  316.14
#Mann= 11 ,-1 , 0
  3828.7     .16       0  4189.4      .1       0    4399     .16       0
  4478.8      .1       0  4518.5     .16       0  4714.5     .12       0
  4993.4     .07       0  4999.4     .12       0  5209.8     .16       0
  5341.1     .08       0  5816.4     .16       0
Bank Sta=4993.4,4999.4
XS Rating Curve= 0 ,0
Exp/Cntr=0.3,0.1

Type RM Length L Ch R = 1 ,9569    ,978,978,978
BEGIN DESCRIPTION:
UNT0500 IN WICK 16.0
END DESCRIPTION:
XS GIS Cut Line= 3
      3563692.08     10245741.67      3564692.11     10244541.64
      3565014.68     10244306.27
#Sta/Elev= 30
  3478.4  305.44    3616  302.77  3699.1  301.39  3748.5     297  3769.4  297.59
  3804.5  293.39  3954.2  298.09  4053.1  295.65  4131.2  297.55  4209.3  294.28
  4259.5  296.26  4585.5  292.41  4656.8  289.09  4909.8  290.13  4925.5  289.97
  4983.9  289.96  4995.2   286.6  4997.9   286.1  5001.2   286.6    5019  290.33
  5148.2   286.9  5198.4   287.9  5254.8  293.82  5263.3  296.36  5269.5  301.03
  5277.4  301.27  5284.2  304.53  5312.8  308.04  5383.1  310.27  5439.8  312.32
#Mann= 9 ,-1 , 0
  3478.4     .05       0    3616     .16       0  4656.8     .12       0
  4909.8     .16       0  4925.5     .12       0  4995.2     .07       0
  5001.2     .12       0  5277.4      .1       0  5383.1     .05       0
Bank Sta=4995.2,5001.2
XS Rating Curve= 0 ,0
Exp/Cntr=0.3,0.1

Type RM Length L Ch R = 1 ,8591    ,669,669,669
BEGIN DESCRIPTION:
UNT0500 IN WICK 14.0
END DESCRIPTION:
XS GIS Cut Line= 3
      3564292.08     10245941.66      3565042.11     10245341.64
      3565242.13     10245091.61
#Sta/Elev= 30
  4039.5  307.75  4189.2     303  4288.5  301.19  4302.9  300.12  4445.3  297.09
  4466.1  297.45  4544.6  295.28    4559  294.12  4587.8  294.14  4602.2   292.9
  4786.3   288.9  4821.5  286.83  4852.6  287.07  4922.4  286.76  4949.6  284.91
    4964  286.64  4978.4  286.63  4986.4  285.23  4992.8  282.23  4993.8  280.97
  4996.6  280.47  4999.8  280.97  5007.2  280.97  5013.6  284.59    5028   287.1
  5085.6  287.61  5103.8   288.9  5144.8  291.66  5239.8  298.64  5320.2  304.15
#Mann= 7 ,-1 , 0
  4039.5     .16       0  4852.6     .12       0  4993.8     .07       0
  4999.8     .12       0  5103.8      .1       0  5144.8     .16       0
  5239.8      .1       0
Bank Sta=4993.8,4999.8
XS Rating Curve= 0 ,0
Exp/Cntr=0.3,0.1

Type RM Length L Ch R = 1 ,7922    ,1505,1505,1505
BEGIN DESCRIPTION:
UNT0500 IN WICK 12.0
END DESCRIPTION:
XS GIS Cut Line= 4
      3564526.17     10246054.66      3565038.37     10245980.87
      3565593.93      10245564.2      3565971.39     10244206.22
#Sta/Elev= 30
  4138.1  302.23  4549.1  294.24  4664.6  290.39  4743.7  286.21  4865.1  283.04
  4866.5  283.02    4900   280.6  4929.2  283.88  4958.3  280.71  4979.2  281.23
    4997  277.47  4999.7  276.97    5003  277.47  5008.3  280.24  5014.6  280.07
  5029.2   283.3  5035.4  282.37    5050  284.17  5089.8     284  5143.7  284.54
  5185.4  287.58    5473  299.84  5659.7  304.48  5862.7   305.8  5944.6  307.03
  6224.6  310.52  6702.8  310.08  6706.7  309.73  6733.1  314.42  6759.5  312.05
#Mann= 10 ,-1 , 0
  4138.1     .05       0  4865.1     .16       0  4866.5     .12       0
    4997     .07       0    5003     .12       0  5089.8     .16       0
  5862.7      .1       0  5944.6     .16       0  6224.6     .05       0
  6702.8      .1       0
Bank Sta=4997,5003
XS Rating Curve= 0 ,0
Exp/Cntr=0.3,0.1

Type RM Length L Ch R = 1 ,6417    ,1270,1270,1270
BEGIN DESCRIPTION:
UNT0500 IN WICK 11.0
END DESCRIPTION:
XS GIS Cut Line= 4
      3565042.13     10246341.64      3565632.99     10246380.17
      3566415.14     10245741.34      3566952.44     10244600.65
#Sta/Elev= 30
  3544.5  295.79  3777.5  292.37  3865.2  289.57  3935.3  286.07  4005.5  285.88
  4077.4  283.97  4133.7  282.38  4156.4  282.68    4164  281.81  4185.1  281.83
  4226.8  279.74  4318.8  280.71    4519  279.06  4653.2  279.68  4803.3  277.54
  4931.1  277.98  4966.3  278.99  4974.2   278.8  4980.6  277.25  4989.1  272.41
    4992  271.38  4994.7  270.88    4998  271.38  5009.3  275.17  5015.8  281.16
  5030.1  285.74  5120.8  290.26  5578.2  296.45  6022.2  306.88  6407.4  312.91
#Mann= 8 ,-1 , 0
  3544.5     .05       0  4077.4      .1       0    4164     .16       0
  4318.8     .12       0  4989.1     .16       0    4992     .07       0
    4998     .16       0  5120.8     .05       0
Bank Sta=4992,4998
XS Rating Curve= 0 ,0
Exp/Cntr=0.3,0.1

Type RM Length L Ch R = 1 ,5147    ,941,941,941
BEGIN DESCRIPTION:
Mapping XS 78c89818
END DESCRIPTION:
XS GIS Cut Line= 2
      3566515.64     10246770.91      3567142.46     10245165.43
#Sta/Elev= 30
  4404.8  291.46  4433.6  289.58  4592.6  284.95    4724  280.22  4766.9  278.54
  4811.9  273.62    4973  275.52  4987.7  272.57  4991.4  268.35  4994.2  267.85
  4997.4  268.35  5005.2  268.92  5012.1  273.33  5017.5  272.94  5026.6  275.21
  5180.5  277.27  5319.6  281.22  5343.5  283.27  5348.9  282.35  5423.5  285.92
  5424.4  285.96    5499  288.51  5548.6  288.68  5714.8  294.15  5783.6  297.05
  5831.8  297.42  5874.2  299.86  5923.6  301.58  6030.7  306.86  6128.3  309.64
#Mann= 13 ,-1 , 0
  4404.8     .05       0  4592.6     .12       0    4724     .05       0
  4766.9     .12       0  4991.4     .07       0  4997.4     .12       0
  5319.6      .1       0  5423.5     .05       0  5424.4     .16       0
  5548.6      .1       0  5714.8     .05       0  5874.2      .1       0
  5923.6     .05       0
Bank Sta=4991.4,4997.4
XS Rating Curve= 0 ,0
Exp/Cntr=0.3,0.1

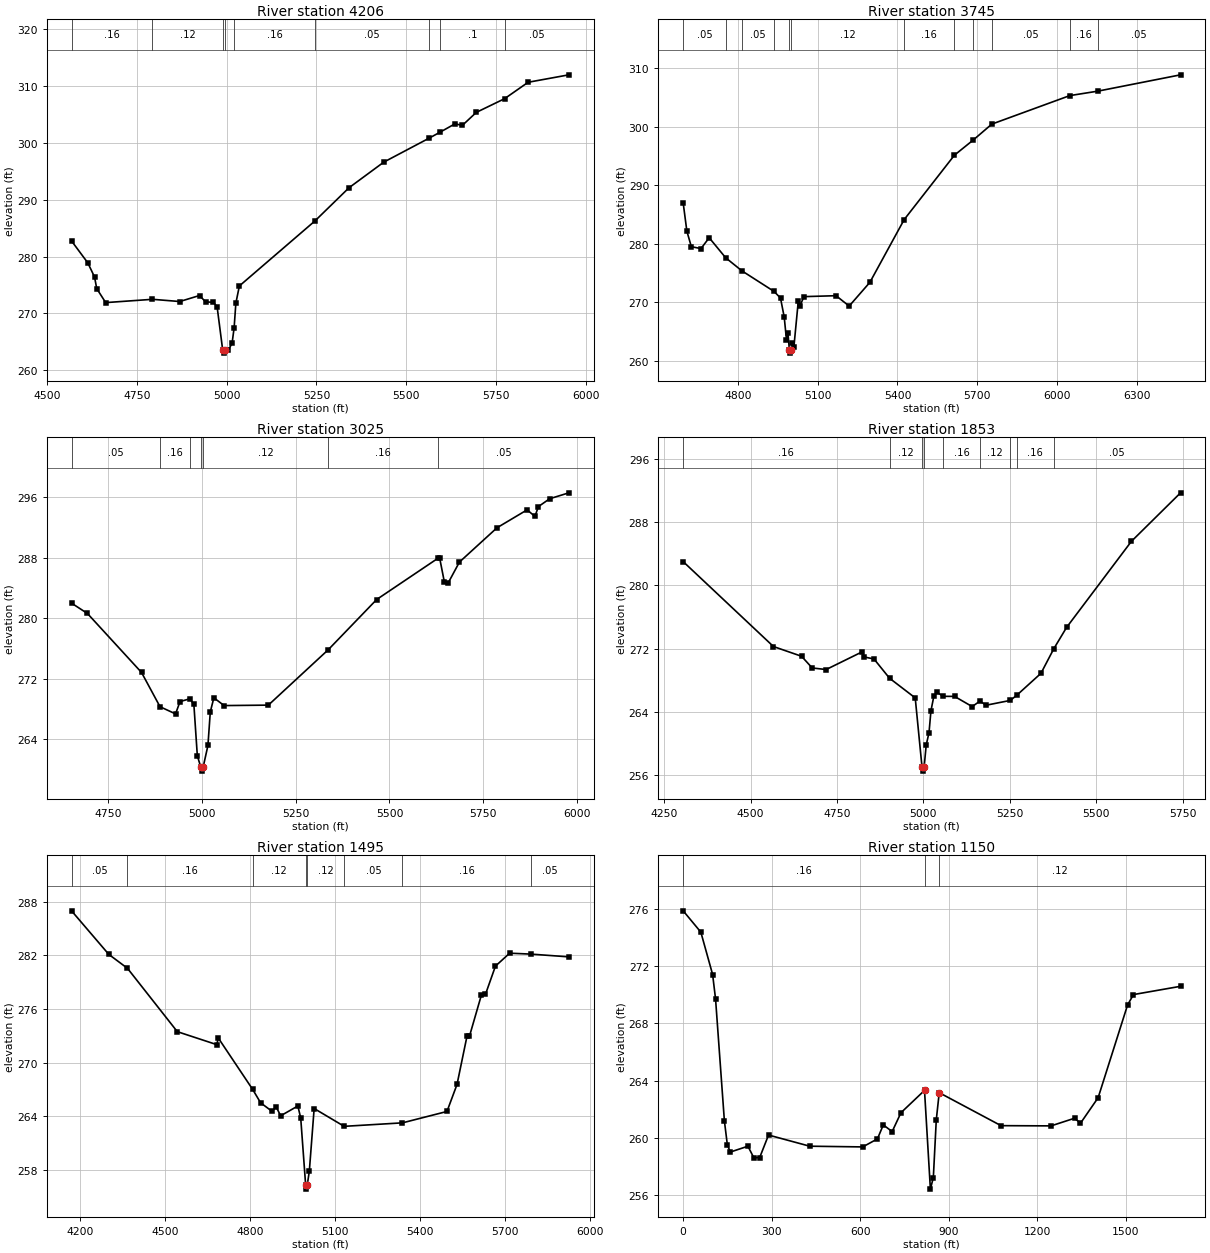
Type RM Length L Ch R = 1 ,4206    ,461,461,461
BEGIN DESCRIPTION:
UNT0500 IN WICK 7.0
END DESCRIPTION:
XS GIS Cut Line= 3
      3567242.11     10246541.63      3567392.11     10246141.64
      3567575.98     10245200.01
#Sta/Elev= 30
  4567.1  282.74  4612.5  278.88  4631.2   276.4  4637.4  274.35  4662.3  271.89
  4792.8  272.47  4868.8  272.08    4924  273.14  4940.9  272.01  4962.2  271.95
  4972.9  271.18  4988.6   263.5  4991.4     263  4994.6   263.5  5004.5  263.56
  5014.7  264.75  5020.4  267.47  5025.2  271.78    5035  274.82  5245.7  286.26
  5340.7   292.1  5437.7  296.61  5564.2  300.83  5595.4  301.91  5636.2  303.35
  5656.6  303.07  5695.5  305.36  5774.4  307.77    5840  310.66  5953.7  311.97
#Mann= 9 ,-1 , 0
  4567.1     .16       0  4792.8     .12       0  4988.6     .07       0
  4994.6     .12       0  5020.4     .16       0  5245.7     .05       0
  5564.2     .16       0  5595.4      .1       0  5774.4     .05       0
Bank Sta=4988.6,4994.6
XS Rating Curve= 0 ,0
Exp/Cntr=0.3,0.1

Type RM Length L Ch R = 1 ,3745    ,720,720,720
BEGIN DESCRIPTION:
UNT0500 IN WICK 6.0
END DESCRIPTION:
XS GIS Cut Line= 4
      3567392.12     10246841.61      3567592.11     10246441.64
       3568083.8     10245868.37      3567975.29     10245208.66
#Sta/Elev= 30
  4593.8     287  4607.7  282.17  4624.5  279.53  4660.8  279.21  4691.6  281.06
  4753.4  277.65  4814.6  275.41  4935.9  271.88  4959.9  270.76  4973.9   267.5
  4982.3  263.67  4987.9  264.81  4993.3  261.85    4996  261.35  4999.3  261.85
  5004.6  263.13  5010.2  262.38    5027  270.33  5032.6  269.38  5048.1     271
  5168.8  271.16  5218.2  269.39  5296.1  273.44  5425.1  284.16  5614.1  295.16
  5685.9  297.79  5754.8  300.47  6048.1  305.34  6153.4   306.1  6464.8  308.89
#Mann= 12 ,-1 , 0
  4593.8     .05       0  4753.4     .16       0  4814.6     .05       0
  4935.9     .12       0  4993.3     .07       0  4999.3     .12       0
  5425.1     .16       0  5614.1     .05       0  5685.9     .16       0
  5754.8     .05       0  6048.1     .16       0  6153.4     .05       0
Bank Sta=4993.3,4999.3
XS Rating Curve= 0 ,0
Exp/Cntr=0.3,0.1

Type RM Length L Ch R = 1 ,3025    ,1172,1172,1172
BEGIN DESCRIPTION:
UNT0500 IN WICK 4.0
END DESCRIPTION:
XS GIS Cut Line= 4
      3567790.08     10246922.71      3567963.72     10246901.01
      3568224.14     10246445.28      3568274.77     10245820.61
#Sta/Elev= 30
    4652  282.02  4694.4  280.65  4838.7  272.85    4888  268.32  4929.4  267.37
  4941.4     269  4967.7  269.37  4978.3  268.63  4987.5  261.84  4996.9   260.3
  4999.7   259.8  5002.9   260.3  5015.8  263.19  5022.1  267.63  5031.6   269.5
    5059  268.47    5177  268.53  5336.8  275.86  5465.9   282.5  5629.5  287.96
  5633.8  288.01  5646.5   284.8  5656.5  284.68  5686.6  287.45  5786.9  291.99
  5867.2  294.36    5888  293.49  5897.3  294.79  5927.4  295.83  5978.6  296.61
#Mann= 7 ,-1 , 0
    4652     .05       0    4888     .16       0  4967.7     .12       0
  4996.9     .07       0  5002.9     .12       0  5336.8     .16       0
  5629.5     .05       0
Bank Sta=4996.9,5002.9
XS Rating Curve= 0 ,0
Exp/Cntr=0.3,0.1

Type RM Length L Ch R = 1 ,1853    ,358,358,358
BEGIN DESCRIPTION:
UNT0500 IN WICK 3.0
END DESCRIPTION:
XS GIS Cut Line= 3
      3568134.69     10247179.48      3568642.11     10247091.64
      3569037.11     10246256.62
#Sta/Elev= 30
  4305.2  283.02  4566.4  272.27  4647.6  271.04  4678.4  269.56  4718.7  269.36
  4822.9   271.6  4828.8  270.95  4857.1   270.7  4902.1  268.26  4976.4  265.77
  4996.1     257  4998.9   256.5  5002.1     257  5008.2  259.81  5016.3  261.37
  5021.9  264.14  5030.3  265.99  5039.1  266.49    5057  265.97  5090.1  265.96
  5141.2  264.67  5163.7  265.37  5181.2  264.84  5251.3  265.45  5269.5  266.08
  5340.1  268.88  5377.1  271.98  5414.2  274.69  5601.8  285.59  5743.9  291.73
#Mann= 9 ,-1 , 0
  4305.2     .16       0  4902.1     .12       0  4996.1     .07       0
  5002.1     .12       0    5057     .16       0  5163.7     .12       0
  5251.3     .05       0  5269.5     .16       0  5377.1     .05       0
Bank Sta=4996.1,5002.1
XS Rating Curve= 0 ,0
Exp/Cntr=0.3,0.1

Type RM Length L Ch R = 1 ,1495    ,345,345,345
BEGIN DESCRIPTION:
UNT0500 IN WICK 2.0
END DESCRIPTION:
XS GIS Cut Line= 3
       3568142.1     10247291.64      3569052.25     10247157.58
      3569723.43     10246661.14
#Sta/Elev= 30
  4169.4  286.96  4300.8   282.1  4366.8  280.54  4542.6  273.47    4682  272.02
    4687  272.77  4808.5  267.02  4836.5  265.53    4877  264.57    4891  265.09
  4907.3  264.08  4967.9  265.17    4978  263.83  4995.3  256.39    4998  255.89
  5001.3  256.39  5008.4   257.9  5025.4  264.89  5131.3   262.9    5337  263.29
    5494  264.56  5529.5  267.58  5564.9     273  5573.3  272.95    5615  277.51
  5629.7  277.62  5665.1  280.79  5715.2  282.23  5789.1  282.13  5924.2  281.82
#Mann= 8 ,-1 , 0
  4169.4     .05       0  4366.8     .16       0  4808.5     .12       0
  4995.3     .07       0  5001.3     .12       0  5131.3     .05       0
    5337     .16       0  5789.1     .05       0
Bank Sta=4995.3,5001.3
XS Rating Curve= 0 ,0
Exp/Cntr=0.3,0.1

Type RM Length L Ch R = 1 ,1150    ,728,728,728
XS GIS Cut Line= 2
     3568128.819    10247645.408     3569792.882    10247379.783
#Sta/Elev= 30
       0  275.86   59.84  274.37   99.74  271.41  109.71   269.7  139.63  261.18
   149.6  259.52  159.58     259  219.42  259.41  239.37   258.6  259.31  258.62
  289.23  260.19  428.87  259.41  608.39  259.36  658.26  259.92  678.21   260.9
  708.13  260.43  738.05  261.75  817.84  263.31  837.78  256.41  847.76  257.22
  857.73  261.25   867.7  263.151077.151260.84631246.703  260.831326.491261.3655
1346.439261.0141 1406.28262.80181506.017269.28081525.964270.00711685.542 270.585
#Mann= 3 ,-1 , 0
       0     .16       0  817.84     .07       0   867.7     .12       0
Bank Sta=817.84,867.7
XS Rating Curve= 0 ,0
Exp/Cntr=0.3,0.1

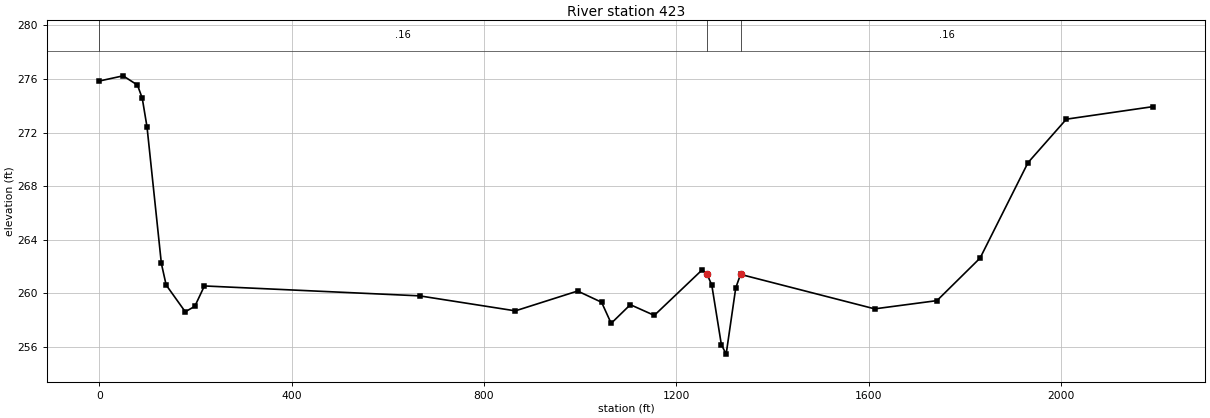
Type RM Length L Ch R = 1 ,423     ,,,
XS GIS Cut Line= 4
      3568141.84    10248038.637     3568764.236    10248312.075
     3569928.298     10247778.22     3569946.528    10247551.658
#Sta/Elev= 30
       0  275.85   49.71  276.24   79.54  275.55   89.48  274.57   99.43  272.42
  129.26  262.23   139.2  260.62  178.97  258.62  198.85  259.03  218.74  260.55
  666.16  259.81  865.43  258.69  994.96  260.17 1044.78259.3321 1064.71257.7565
 1104.57259.1507 1154.39258.3516 1254.03261.7545 1263.99261.4379 1273.96260.6146
 1293.88256.1682 1303.85255.4587 1323.78260.4008 1333.74 261.413 1612.74258.8395
 1742.27259.4536 1831.95262.6309 1931.59269.7571 2011.38 273.003 2191.02273.9374
#Mann= 3 ,-1 , 0
       0     .16       0 1263.99     .07       0 1333.74     .16       0
Bank Sta=1263.99,1333.74
XS Rating Curve= 0 ,0
Exp/Cntr=0.3,0.1

Chan Stop Cuts=-1
Use User Specified Reach Order=0
Composite Channel Slope=5