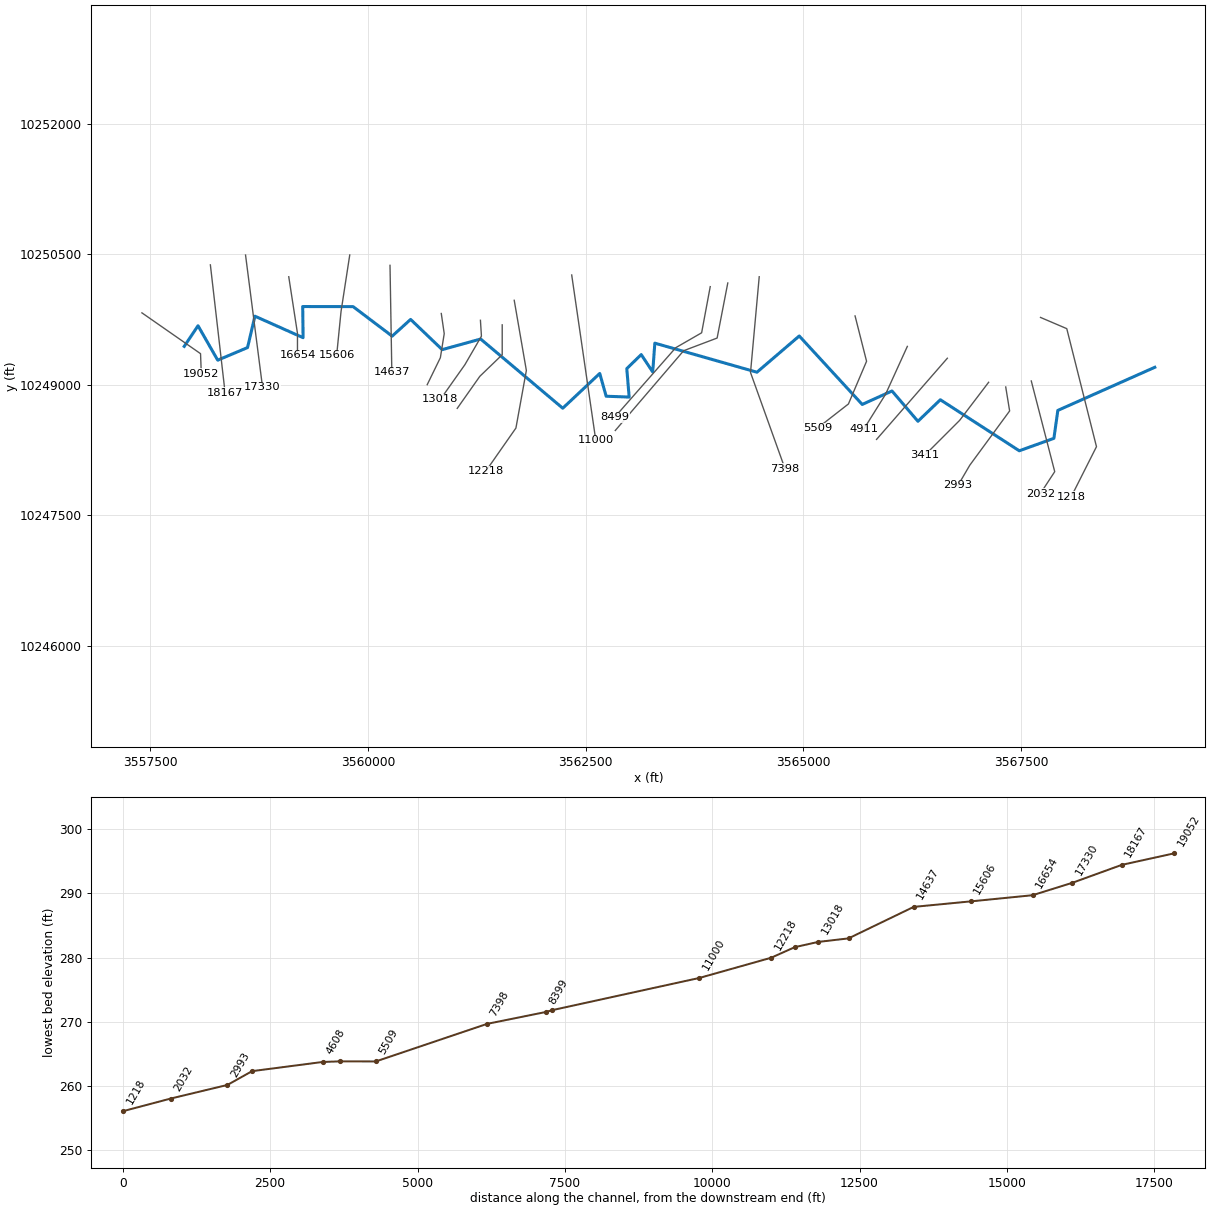
--- WICKSONCREEKTRIB.prj (project) ---

Proj Title=WICKSON CREEK TRIB 23
Current Plan=p01
Default Exp/Contr=0.3,0.1
English Units
Geom File=g01
Flow File=f01
Plan File=p01
Y Axis Title=Elevation
X Axis Title(PF)=Main Channel Distance
X Axis Title(XS)=Station
BEGIN DESCRIPTION:
UNT0499 IN WICK
END DESCRIPTION:
DSS Export Rating Curves= 0
DSS Export Rating Curve Sorted= 0
DSS Export Volume Flow Curves= 0
DXF OffsetX= 0
DXF OffsetY= 0
DXF ScaleX= 1
DXF ScaleY= 10

--- WICKSONCREEKTRIB.p01 (plan) ---

Plan Title=Multiple Run
Short Identifier=Multiple
Geom File=g01
Flow File=f01
Subcritical Flow
K Sum by GR= 0
Std Step Tol= 0.01
Critical Tol= 0.01
Num of Std Step Trials= 20
Max Error Tol= 0.3
Flow Tol Ratio= 0.001
Split Flow NTrial= 30
Split Flow Tol= 0.02
Split Flow Ratio= 0.02
Log Output Level= 0
Friction Slope Method= 1
Unsteady Friction Slope Method= 2
Unsteady Bridges Friction Slope Method= 1
Parabolic Critical Depth
Global Vel Dist=  1 , 1 , 1
Global Log Level= 0
CheckData=True
Encroach Param= -1, 0, 0, 0
BEGIN DESCRIPTION:
Multiple Run
END DESCRIPTION:

--- WICKSONCREEKTRIB.f01 (steady flow) ---

Flow Title=Multiple
Program Version=4.10
Number of Profiles= 7
Profile Names=10-year,25-year,50-year,1pct_min,100-year,1pct_plu,500-year
River Rch & RM=UNT0499 IN WICK,Reach-1         ,19052
     758    1032    1256    1118    1512    2045    2199
River Rch & RM=UNT0499 IN WICK,Reach-1         ,11000
     960    1318    1612    1441    1949    2636    2859
River Rch & RM=UNT0499 IN WICK,Reach-1         ,5509
    1035    1425    1747    1565    2117    2863    3117
River Rch & RM=WICKSONCRTRB23,Reach-1         ,19052
     758    1032    1256    1118    1512    2045    2199
River Rch & RM=WICKSONCRTRB23,Reach-1         ,11000
     960    1318    1612    1441    1949    2636    2859
River Rch & RM=WICKSONCRTRB23,Reach-1         ,5509
    1035    1425    1747    1565    2117    2863    3117
Boundary for River Rch & Prof#=WICKSONCRTRB23,Reach-1         , 1
Up Type= 0
Dn Type= 3
Dn Slope=0.005
Boundary for River Rch & Prof#=WICKSONCRTRB23,Reach-1         , 2
Up Type= 0
Dn Type= 3
Dn Slope=0.005
Boundary for River Rch & Prof#=WICKSONCRTRB23,Reach-1         , 3
Up Type= 0
Dn Type= 3
Dn Slope=0.005
Boundary for River Rch & Prof#=WICKSONCRTRB23,Reach-1         , 4
Up Type= 0
Dn Type= 3
Dn Slope=0.005
Boundary for River Rch & Prof#=WICKSONCRTRB23,Reach-1         , 5
Up Type= 0
Dn Type= 3
Dn Slope=0.005
Boundary for River Rch & Prof#=WICKSONCRTRB23,Reach-1         , 6
Up Type= 0
Dn Type= 3
Dn Slope=0.005
Boundary for River Rch & Prof#=WICKSONCRTRB23,Reach-1         , 7
Up Type= 0
Dn Type= 3
Dn Slope=0.005
DSS Import GetInterval= 0
DSS Import GetPeak= 0
DSS Import FillOption= 0

--- WICKSONCREEKTRIB.g01 (geometry) ---

Geom Title=Existing Conditions
Program Version=4.10

River Reach=WICKSONCRTRB23  ,Reach-1
Reach XY= 30
      3557892.11     10249441.64      3558050.71      10249678.7
      3558276.71     10249283.27      3558619.03     10249428.15
      3558703.57     10249788.52      3559256.77     10249541.65
      3559252.24     10249899.31      3559830.81      10249898.4
      3560278.91     10249559.46      3560490.95     10249751.57
      3560853.28     10249404.47      3561294.91      10249526.3
      3562237.14     10248731.49      3562661.65     10249130.92
      3562735.19     10248869.26      3562999.01     10248859.72
      3562972.13     10249186.63      3563137.72     10249347.68
       3563269.2     10249148.19       3563294.2     10249478.82
      3564465.85     10249145.07       3564951.5      10249561.1
      3565674.17     10248774.96      3566016.08     10248929.64
      3566313.43     10248581.45      3566570.93     10248828.86
      3567477.14     10248242.63      3567874.34     10248385.87
      3567919.45     10248706.63      3569032.11     10249201.64

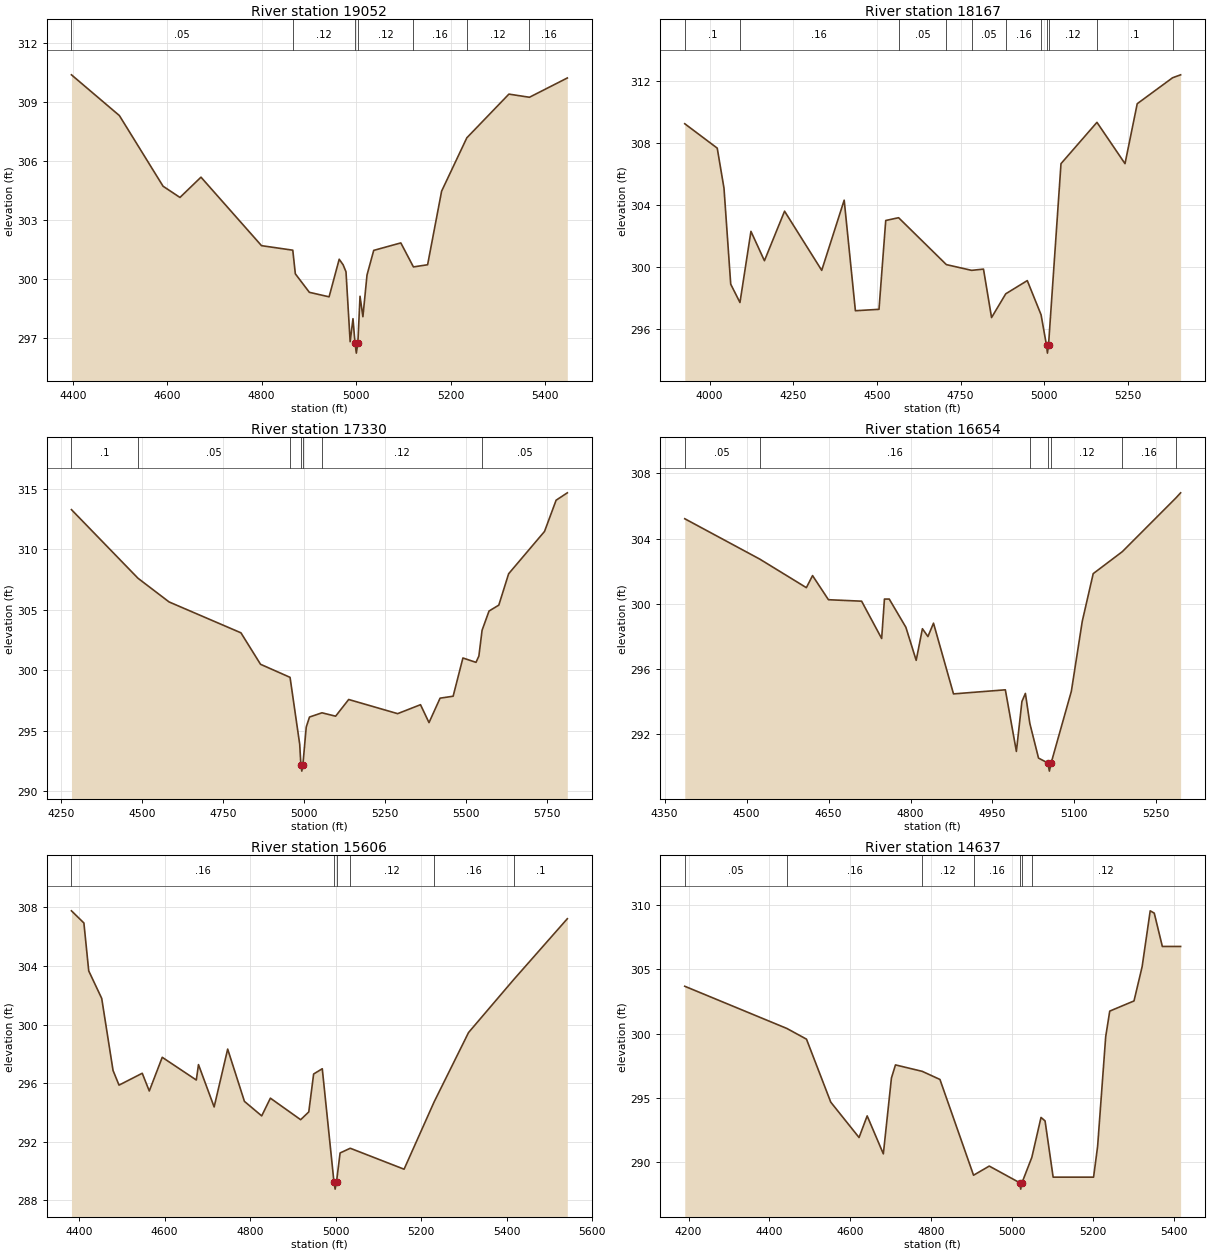
Type RM Length L Ch R = 1 ,19052   ,885,885,885
BEGIN DESCRIPTION:
UNT0499 IN WICK 33.0
END DESCRIPTION:
XS GIS Cut Line= 3
      3557406.92     10249826.82      3558079.64     10249358.08
      3558088.32     10249128.07
#Sta/Elev= 30
  4397.3  310.39  4498.8  308.32  4591.3  304.73  4627.1  304.16  4671.6  305.19
  4799.8  301.71    4866  301.48  4871.4  300.28  4901.1  299.34  4942.9  299.11
  4964.3  301.02  4972.6  300.74  4978.7  300.38  4987.5  296.83  4993.5     298
  4997.8  296.75  5000.6  296.25  5003.8  296.75  5008.4  299.14  5014.5   298.1
  5023.2  300.22  5037.4  301.47  5094.8  301.85  5121.5  300.63  5151.5  300.74
  5181.2  304.48  5234.6  307.19  5323.7  309.41  5367.2  309.25  5447.4  310.23
#Mann= 7 ,-1 , 0
  4397.3     .05       0    4866     .12       0  4997.8     .07       0
  5003.8     .12       0  5121.5     .16       0  5234.6     .12       0
  5367.2     .16       0
Bank Sta=4997.8,5003.8
XS Rating Curve= 0 ,0
Exp/Cntr=0.3,0.1

Type RM Length L Ch R = 1 ,18167   ,837,837,837
BEGIN DESCRIPTION:
Mapping XS 3373c8e3
END DESCRIPTION:
XS GIS Cut Line= 2
      3558192.49     10250378.05      3558361.77     10248906.65
#Sta/Elev= 30
    3926  309.23    4023  307.66  4043.2  305.08  4063.3   298.9  4090.9  297.72
  4123.7   302.3    4164  300.41  4224.1   303.6  4335.1  299.79  4402.2  304.31
  4435.7  297.19  4506.2  297.28  4526.3     303  4564.7  303.18  4707.4  300.16
  4782.7  299.79  4818.3  299.87  4842.4  296.75  4884.8  298.28  4949.1  299.13
  4990.3  296.93  5006.5  294.96  5009.3  294.46  5012.5  294.96  5049.8  306.66
  5157.2  309.32    5241  306.66  5277.5  310.52    5383  312.19  5407.1  312.38
#Mann= 11 ,-1 , 0
    3926      .1       0  4090.9     .16       0  4564.7     .05       0
  4707.4     .16       0  4782.7     .05       0  4884.8     .16       0
  4990.3     .12       0  5006.5     .07       0  5012.5     .12       0
  5157.2      .1       0    5383     .05       0
Bank Sta=5006.5,5012.5
XS Rating Curve= 0 ,0
Exp/Cntr=0.3,0.1

Type RM Length L Ch R = 1 ,17330   ,676,676,676
BEGIN DESCRIPTION:
Mapping XS e2848182
END DESCRIPTION:
XS GIS Cut Line= 2
      3558596.14     10250490.91      3558791.45     10248971.81
#Sta/Elev= 30
  4282.4  313.28  4487.9  307.61  4584.1  305.65  4805.9   303.1  4866.4   300.5
  4957.6  299.42  4987.4  293.89  4991.1  292.17  4993.9  291.67  4997.1  292.17
  5007.6  295.32  5017.7  296.14  5056.1  296.49  5098.3  296.21  5138.7  297.59
  5289.9  296.42  5360.5  297.16  5386.8  295.68    5421   297.7  5461.3  297.86
  5491.5  301.02  5531.9  300.66  5540.8  301.18  5550.7  303.31  5572.2   304.9
  5602.4  305.39  5632.7  307.98  5743.6  311.48  5779.4  314.06    5814  314.67
#Mann= 7 ,-1 , 0
  4282.4      .1       0  4487.9     .05       0  4957.6     .16       0
  4991.1     .07       0  4997.1     .16       0  5056.1     .12       0
  5550.7     .05       0
Bank Sta=4991.1,4997.1
XS Rating Curve= 0 ,0
Exp/Cntr=0.3,0.1

Type RM Length L Ch R = 1 ,16654   ,1048,1048,1048
BEGIN DESCRIPTION:
UNT0499 IN WICK 31.0
END DESCRIPTION:
XS GIS Cut Line= 3
      3559092.11     10250241.61      3559192.11     10249591.64
      3559192.11     10249341.66
#Sta/Elev= 30
  4386.8  305.22  4524.2  302.74  4609.4  300.99  4620.7  301.73  4649.8  300.25
  4710.5  300.16  4747.2  297.87  4752.3  300.29  4761.1  300.29  4791.5  298.56
  4810.4  296.53  4821.8  298.47  4831.9  297.99  4842.1  298.81  4878.7  294.47
  4973.6  294.72  4993.8  290.94  5003.9     294  5010.3   294.5  5018.4  292.66
  5034.3  290.53  5051.4  290.23  5054.2  289.73  5057.4  290.23  5094.4  294.63
  5114.4  298.93  5134.4  301.85  5187.7   303.2  5285.9   306.5  5294.4  306.81
#Mann= 7 ,-1 , 0
  4386.8     .05       0  4524.2     .16       0  5018.4     .12       0
  5051.4     .07       0  5057.4     .12       0  5187.7     .16       0
  5285.9     .05       0
Bank Sta=5051.4,5057.4
XS Rating Curve= 0 ,0
Exp/Cntr=0.3,0.1

Type RM Length L Ch R = 1 ,15606   ,969,969,969
BEGIN DESCRIPTION:
UNT0499 IN WICK 29.0
END DESCRIPTION:
XS GIS Cut Line= 3
       3559792.1     10250491.61      3559692.11     10249841.64
      3559642.11     10249341.65
#Sta/Elev= 30
  4382.1  307.77  4411.2  306.94  4422.5  303.67  4452.9  301.79  4479.4  296.87
  4493.4  295.87  4547.7  296.68  4564.2  295.47  4594.5  297.77  4674.2  296.22
  4679.3  297.27  4715.9  294.38  4747.6  298.33  4786.8  294.76  4827.2  293.77
  4847.5  294.98  4918.3  293.51  4937.3  294.04  4948.7  296.63  4968.9  296.99
  4996.2  289.27    4999  288.77  5002.2  289.27  5010.6  291.24  5034.4  291.56
  5160.3  290.13  5230.5  294.72  5311.1  299.46  5416.6  303.07  5542.2  307.23
#Mann= 6 ,-1 , 0
  4382.1     .16       0  4996.2     .07       0  5002.2     .16       0
  5034.4     .12       0  5230.5     .16       0  5416.6      .1       0
Bank Sta=4996.2,5002.2
XS Rating Curve= 0 ,0
Exp/Cntr=0.3,0.1

Type RM Length L Ch R = 1 ,14637   ,1106,1106,1106
BEGIN DESCRIPTION:
UNT0499 IN WICK 27.0
END DESCRIPTION:
XS GIS Cut Line= 2
      3560254.36     10250372.73      3560275.19     10249146.41
#Sta/Elev= 30
  4190.6  303.67  4443.3  300.39  4491.7  299.56  4551.7  294.67  4621.7  291.92
  4641.8   293.6  4681.8  290.65  4701.8  296.54  4711.8  297.56    4778  297.06
  4821.8  296.43  4904.9  288.99  4943.8   289.7  5018.8  288.41  5021.6  287.91
  5024.8  288.41  5049.1  290.38  5071.8  293.48  5081.8  293.21  5101.8  288.84
  5201.8  288.84  5211.8  291.23  5231.8  299.76  5241.8  301.74  5301.8  302.53
  5321.9  305.19  5341.9  309.53  5351.9  309.35  5371.9  306.76  5417.1  306.76
#Mann= 7 ,-1 , 0
  4190.6     .05       0  4443.3     .16       0    4778     .12       0
  4904.9     .16       0  5018.8     .07       0  5024.8     .16       0
  5049.1     .12       0
Bank Sta=5018.8,5024.8
XS Rating Curve= 0 ,0
Exp/Cntr=0.3,0.1

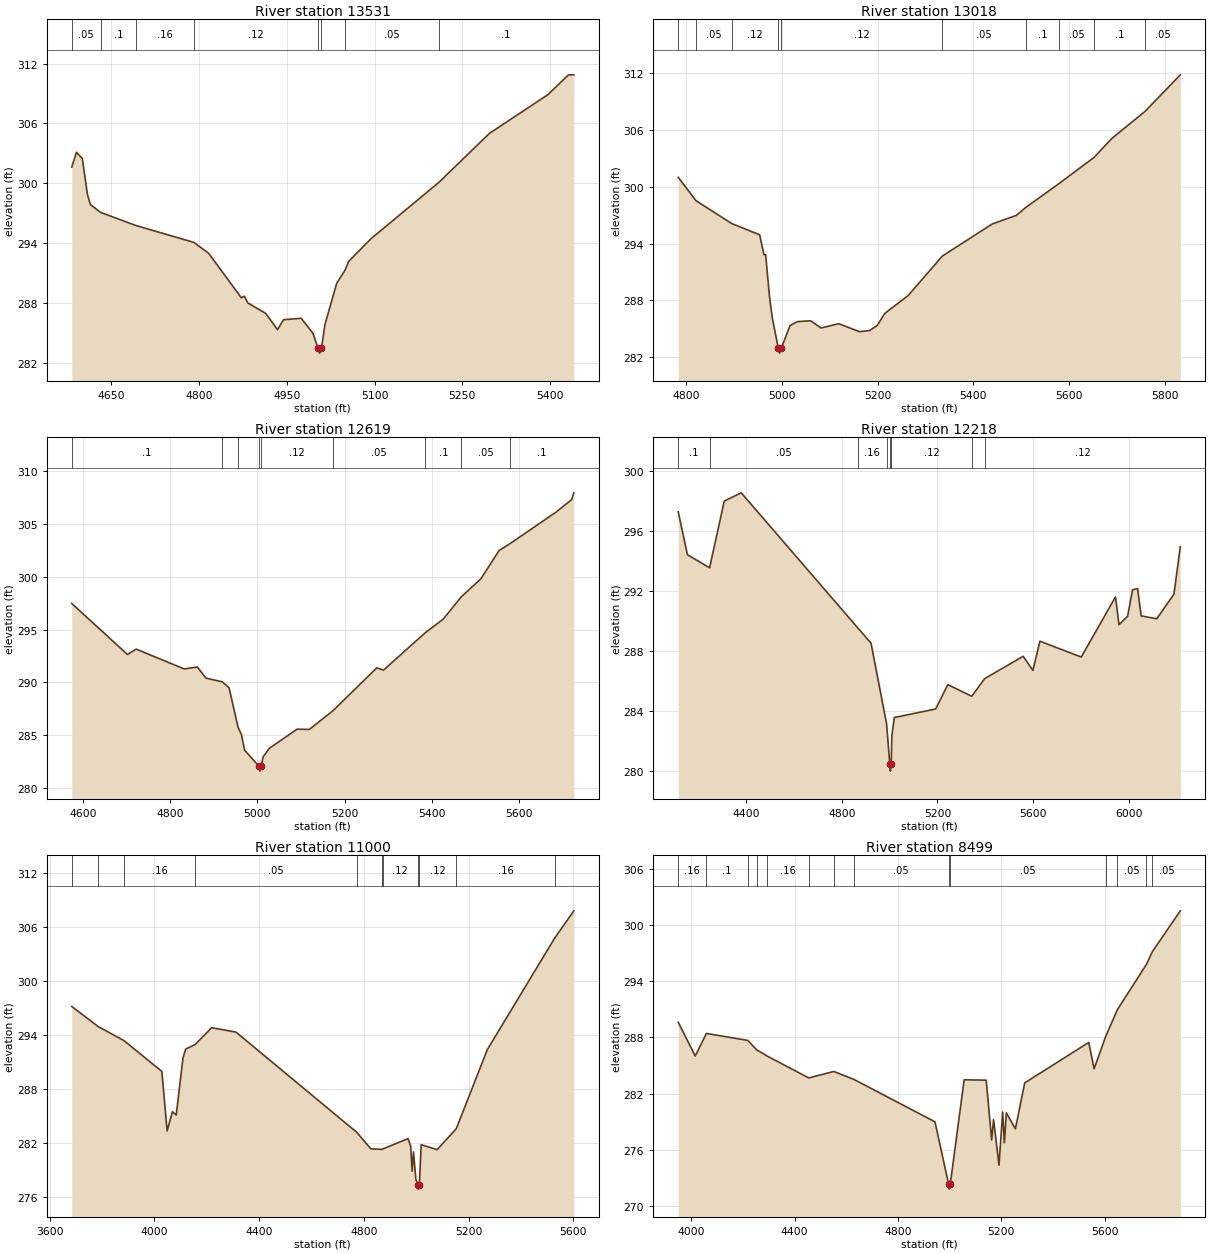
Type RM Length L Ch R = 1 ,13531   ,513,513,513
BEGIN DESCRIPTION:
UNT0499 IN WICK 25.0
END DESCRIPTION:
XS GIS Cut Line= 4
      3560842.72     10249819.54      3560876.57     10249587.81
       3560832.3     10249311.77      3560681.25     10249001.88
#Sta/Elev= 30
  4582.3  301.63  4590.3  303.11  4600.4  302.48    4609  298.92  4614.1  297.88
  4631.7  297.09  4692.4  295.77  4791.1  294.09  4816.5  292.99  4872.3  288.54
  4877.3   288.7  4883.5  288.02  4913.9  286.98  4934.1  285.35  4944.4  286.35
  4974.7  286.49  4994.9  284.97  5003.3   283.5  5006.1     283  5009.3   283.5
  5015.2  285.86  5035.4  290.01  5049.5  291.29  5055.7  292.18  5093.6  294.44
  5209.6  300.08  5296.4     305  5396.6  308.89  5431.5  310.86  5440.8  310.87
#Mann= 8 ,-1 , 0
  4582.3     .05       0  4631.7      .1       0  4692.4     .16       0
  4791.1     .12       0  5003.3     .07       0  5009.3     .12       0
  5049.5     .05       0  5209.6      .1       0
Bank Sta=5003.3,5009.3
XS Rating Curve= 0 ,0
Exp/Cntr=0.3,0.1

Type RM Length L Ch R = 1 ,13018   ,399,399,399
BEGIN DESCRIPTION:
UNT0499 IN WICK 24.0
END DESCRIPTION:
XS GIS Cut Line= 4
      3561292.11     10249741.61      3561303.65     10249559.17
      3561113.55     10249231.04      3560832.31     10248832.63
#Sta/Elev= 30
  4783.1  300.98  4820.1  298.52  4895.2   296.1  4953.4  294.92  4962.2  292.82
  4965.9  292.82  4973.9  288.41  4979.7  286.18  4992.4  282.95  4995.2  282.45
  4998.4  282.95    5017  285.37  5032.4  285.77    5060  285.86  5081.5   285.1
  5118.8  285.55  5161.9  284.71  5183.4  284.83  5199.2  285.37  5214.9  286.63
  5263.8  288.52  5335.3  292.68  5439.6  296.06  5490.1  296.97  5510.1  297.82
  5578.7   300.3  5652.6  303.08  5689.5  305.07  5758.7  307.91  5832.8  311.78
#Mann= 10 ,-1 , 0
  4783.1      .1       0  4820.1     .05       0  4895.2     .12       0
  4992.4     .07       0  4998.4     .12       0  5335.3     .05       0
  5510.1      .1       0  5578.7     .05       0  5652.6      .1       0
  5758.7     .05       0
Bank Sta=4992.4,4998.4
XS Rating Curve= 0 ,0
Exp/Cntr=0.3,0.1

Type RM Length L Ch R = 1 ,12619   ,401,401,401
BEGIN DESCRIPTION:
UNT0499 IN WICK 23.0
END DESCRIPTION:
XS GIS Cut Line= 4
      3561542.11     10249689.33      3561542.11     10249345.63
      3561285.42     10249098.23      3561026.04      10248729.9
#Sta/Elev= 30
  4574.9  297.46  4702.6  292.64  4722.6  293.15  4832.6  291.28  4862.6  291.46
  4882.6  290.41  4920.2  290.06  4935.5  289.49  4955.9  285.79  4963.8  285.08
    4971  283.61  5003.2  282.13    5006  281.63  5009.2  282.13  5013.4  282.97
  5027.6  283.78  5091.1  285.59  5119.4  285.57  5173.7  287.34  5273.9  291.38
  5289.4  291.17  5385.4  294.71  5426.2  295.98  5467.4  298.08  5512.4  299.78
  5554.2  302.46  5579.3  303.11  5684.8  306.09  5720.6  307.27  5725.6  307.91
#Mann= 9 ,-1 , 0
  4574.9      .1       0  4920.2     .16       0  4955.9     .12       0
  5003.2     .07       0  5009.2     .12       0  5173.7     .05       0
  5385.4      .1       0  5467.4     .05       0  5579.3      .1       0
Bank Sta=5003.2,5009.2
XS Rating Curve= 0 ,0
Exp/Cntr=0.3,0.1

Type RM Length L Ch R = 1 ,12218   ,1218,1218,1218
BEGIN DESCRIPTION:
UNT0499 IN WICK 22.0
END DESCRIPTION:
XS GIS Cut Line= 4
      3561679.98     10249971.14      3561819.29     10249165.31
       3561699.5     10248503.85      3561351.53     10248005.27
#Sta/Elev= 30
  4116.8   297.3  4155.2  294.44  4247.8  293.56  4309.1  298.02  4380.1  298.57
  4865.9  289.57  4922.4  288.53  4987.4  283.14  5000.7  280.48  5003.4  279.98
  5006.7  280.48  5009.4  282.33  5019.6  283.56  5192.4  284.13  5243.2  285.76
  5343.3  284.98  5397.3  286.16  5558.2  287.65  5598.9  286.71  5628.1  288.66
  5800.8   287.6  5943.9  291.62  5958.7  289.76  5994.5  290.32  6015.4   292.1
  6036.4  292.17  6051.2  290.35  6116.6  290.16  6188.2   291.8  6214.8  294.97
#Mann= 8 ,-1 , 0
  4116.8      .1       0  4247.8     .05       0  4865.9     .16       0
  4987.4     .12       0  5000.7     .07       0  5006.7     .12       0
  5343.3      .1       0  5397.3     .12       0
Bank Sta=5000.7,5006.7
XS Rating Curve= 0 ,0
Exp/Cntr=0.3,0.1

Type RM Length L Ch R = 1 ,11000   ,2501,2501,2501
BEGIN DESCRIPTION:
UNT0499 IN WICK 20.0
END DESCRIPTION:
XS GIS Cut Line= 2
      3562339.71     10250261.92      3562615.91     10248364.92
#Sta/Elev= 30
  3684.9  297.17  3785.3  294.94    3884  293.37  4028.8  289.94    4049  283.31
  4069.2  285.45  4083.8  285.08  4109.6  291.46  4119.7  292.42  4155.7  292.93
  4218.9   294.8  4311.7  294.32  4772.5  283.17  4827.1  281.31  4871.2  281.26
  4873.1  281.31  4968.6  282.45  4978.7  281.64  4984.6  278.82  4989.7  280.97
  4998.9  277.88    5006  277.33  5008.7  276.83    5012  277.33  5019.1  281.78
  5079.7  281.22  5153.1  283.56  5271.7  292.37  5528.3  304.76  5601.9  307.82
#Mann= 11 ,-1 , 0
  3684.9     .05       0  3785.3      .1       0    3884     .16       0
  4155.7     .05       0  4772.5     .12       0  4871.2     .16       0
  4873.1     .12       0    5006     .07       0    5012     .12       0
  5153.1     .16       0  5528.3     .05       0
Bank Sta=5006,5012
XS Rating Curve= 0 ,0
Exp/Cntr=0.3,0.1

Type RM Length L Ch R = 1 ,8499    ,100,100,100
BEGIN DESCRIPTION:
UNT0499 IN WICK 19.0
END DESCRIPTION:
XS GIS Cut Line= 4
      3563929.76     10250127.97        3563831.     10249597.82
      3563533.94     10249426.63      3562834.05     10248629.39
#Sta/Elev= 30
  3949.6  289.63  4015.4  286.02  4058.7  288.43  4218.5  287.69  4253.2  286.68
  4294.8     286  4454.6  283.68  4551.7  284.37  4628.1  283.54  4943.2  278.99
  4996.2   272.3  4998.9   271.8  5002.2   272.3  5056.1  283.48  5141.5  283.44
  5162.4  277.06    5170  279.23  5190.9  274.36  5205.1  280.04  5211.7  276.75
  5219.3  279.95  5254.4  278.24  5290.5  283.15  5538.2  287.47    5559  284.66
    5604  288.12  5649.1  290.97  5760.9  295.78  5784.5  297.17  5892.6  301.53
#Mann= 14 ,-1 , 0
  3949.6     .16       0  4058.7      .1       0  4218.5     .16       0
  4253.2      .1       0  4294.8     .16       0  4454.6     .05       0
  4551.7     .16       0  4628.1     .05       0  4996.2     .04       0
  5002.2     .05       0    5604     .12       0  5649.1     .05       0
  5760.9     .16       0  5784.5     .05       0
Bank Sta=4996.2,5002.2
XS Rating Curve= 0 ,0
Exp/Cntr=0.3,0.1

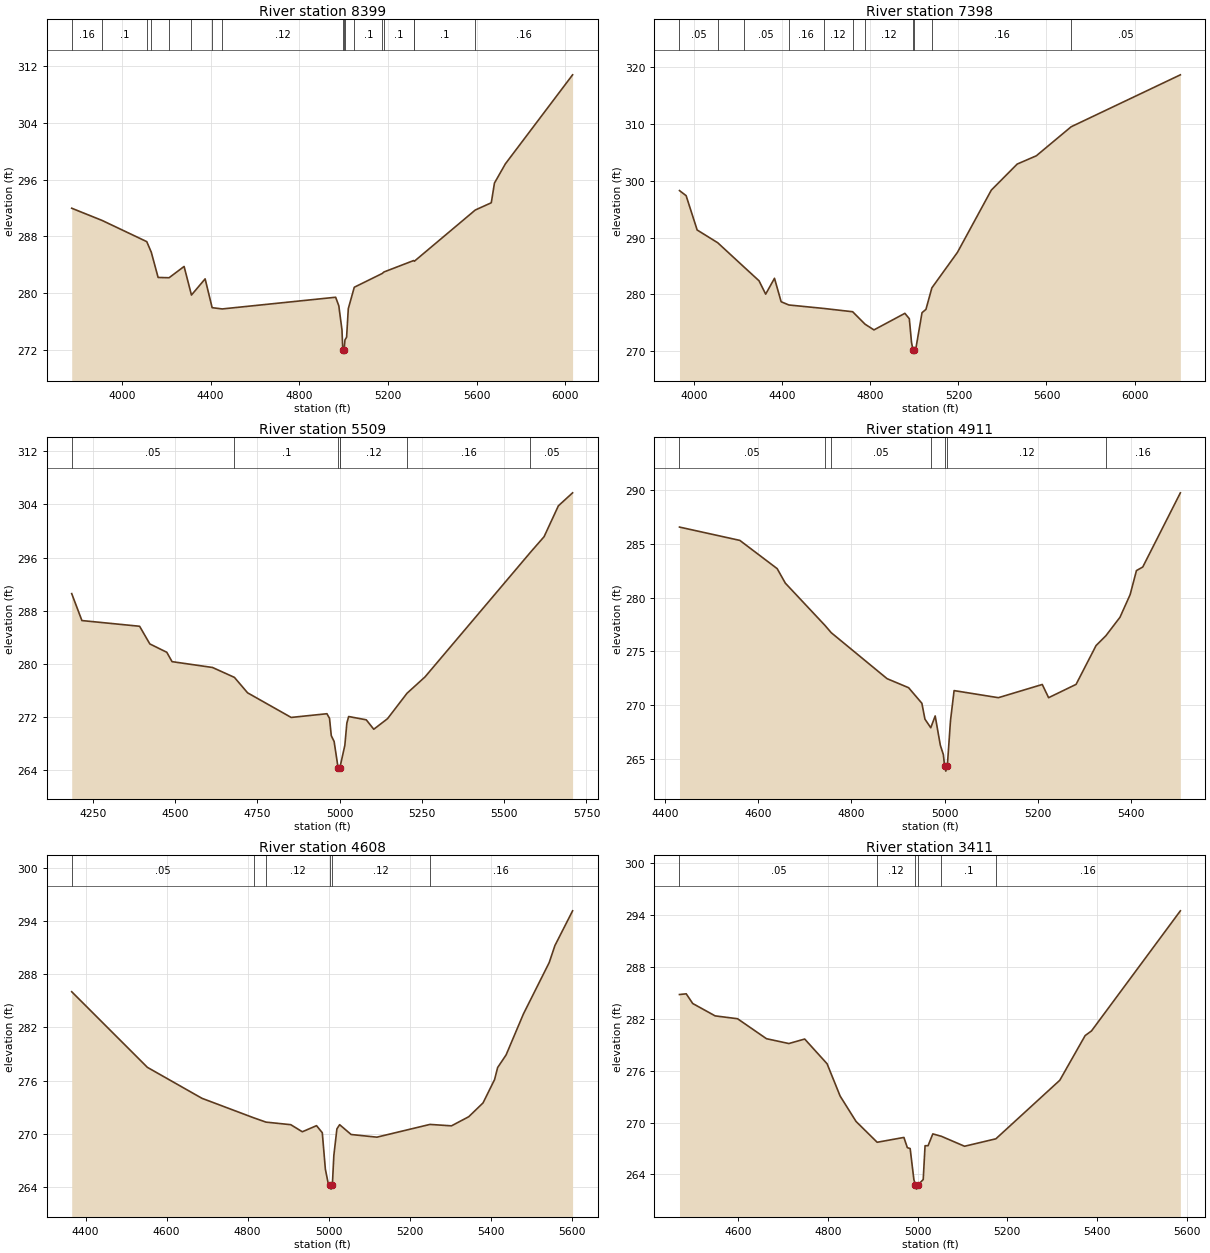
Type RM Length L Ch R = 1 ,8399    ,1001,1001,1001
BEGIN DESCRIPTION:
UNT0499 IN WICK 17.0
END DESCRIPTION:
XS GIS Cut Line= 4
      3564131.16     10250169.71      3564008.84      10249537.6
      3563624.22      10249391.9      3562840.09     10248475.93
#Sta/Elev= 30
  3772.7  291.96  3909.8  290.24  4111.5  287.25    4132  285.75  4162.7   282.2
  4212.3  282.16    4280  283.75  4313.2  279.72  4374.9     282  4406.6  277.94
    4452  277.76  4964.1  279.41  4978.4   278.2  4992.6  274.81  4996.3  272.03
  4999.1  271.53  5002.3  272.03  5006.2   273.4  5013.5  273.77  5021.2   277.8
  5048.2  280.82  5174.3  282.76    5182  282.97  5315.9  284.58  5319.5  284.49
  5594.4  291.71  5666.6  292.73  5680.9  295.51  5730.3  298.22  6033.6  310.77
#Mann= 17 ,-1 , 0
  3772.7     .16       0  3909.8      .1       0  4111.5     .16       0
    4132      .1       0  4212.3     .16       0  4313.2     .05       0
  4406.6     .16       0    4452     .12       0  4996.3     .07       0
  5002.3     .12       0  5006.2     .05       0  5048.2      .1       0
  5174.3     .05       0    5182      .1       0  5315.9     .16       0
  5319.5      .1       0  5594.4     .16       0
Bank Sta=4996.3,5002.3
XS Rating Curve= 0 ,0
Exp/Cntr=0.3,0.1

Type RM Length L Ch R = 1 ,7398    ,1889,1889,1889
BEGIN DESCRIPTION:
UNT0499 IN WICK 14.0
END DESCRIPTION:
XS GIS Cut Line= 3
       3564492.1     10250241.61      3564392.11     10249141.64
      3564787.22     10248038.89
#Sta/Elev= 30
  3932.4   298.3  3962.5  297.41  4012.7  291.36  4106.2  289.11  4224.2  284.89
  4293.9  282.41    4324  280.06  4364.1  282.85  4394.3  278.72  4429.5  278.15
    4588  277.54  4719.2  276.96  4775.5  274.77    4816  273.76  4956.6  276.68
  4976.7  275.73  4986.7  271.56  4993.7  270.17  4996.5  269.67  4999.7  270.17
  5006.8  270.56  5034.4  276.79  5052.3  277.38  5079.1  281.16  5195.4  287.42
  5349.2  298.38  5466.9  302.97  5553.9  304.43    5712  309.54  6208.3  318.69
#Mann= 11 ,-1 , 0
  3932.4     .05       0  4106.2     .16       0  4224.2     .05       0
  4429.5     .16       0    4588     .12       0  4719.2     .16       0
  4775.5     .12       0  4993.7     .07       0  4999.7     .12       0
  5079.1     .16       0    5712     .05       0
Bank Sta=4993.7,4999.7
XS Rating Curve= 0 ,0
Exp/Cntr=0.3,0.1

Type RM Length L Ch R = 1 ,5509    ,598,598,598
BEGIN DESCRIPTION:
UNT0499 IN WICK 10.0
END DESCRIPTION:
XS GIS Cut Line= 4
      3565592.11     10249791.64      3565724.14      10249270.8
       3565515.8     10248780.35      3565159.86     10248502.54
#Sta/Elev= 30
  4186.1  290.56  4217.1   286.5  4392.4  285.64  4423.4  282.98    4475  281.72
  4490.9  280.31  4613.8  279.43  4680.4  277.94  4720.4  275.61  4852.9   271.9
  4961.5  272.46  4969.3  271.77  4974.7  269.15  4983.3  268.28  4995.4  264.31
  4998.1  263.81  5001.4  264.31  5002.6  264.73  5015.9   267.7    5022  271.05
  5027.5  272.04    5081  271.54  5103.8  270.12  5145.7  271.72  5204.7  275.54
  5259.3     278  5579.8  296.79  5621.2  299.14  5664.6  303.79  5707.8  305.75
#Mann= 7 ,-1 , 0
  4186.1     .05       0  4680.4      .1       0  4995.4     .07       0
  5001.4      .1       0  5002.6     .12       0  5204.7     .16       0
  5579.8     .05       0
Bank Sta=4995.4,5001.4
XS Rating Curve= 0 ,0
Exp/Cntr=0.3,0.1

Type RM Length L Ch R = 1 ,4911    ,303,303,303
BEGIN DESCRIPTION:
UNT0499 IN WICK 9.0
END DESCRIPTION:
XS GIS Cut Line= 3
      3566192.09      10249441.6      3565942.11     10248891.64
      3565692.11     10248491.65
#Sta/Elev= 30
  4430.7  286.56  4560.3  285.32  4640.5  282.69    4658  281.34    4743  277.41
  4756.7  276.72  4876.6  272.44  4922.8   271.6  4951.3  270.15  4957.9  268.67
  4970.4  267.87  4979.9  268.97  4990.9  266.25  4997.5  265.36    5000  264.33
  5002.7  263.83    5006  264.33  5012.8  268.55  5020.5  271.33  5115.6  270.67
  5209.9   271.9  5223.5  270.67  5282.5  271.91  5325.5  275.53  5346.5  276.44
  5376.8  278.16  5398.6  280.27  5412.2  282.51  5425.7  282.84  5506.5  289.75
#Mann= 7 ,-1 , 0
  4430.7     .05       0    4743     .16       0  4756.7     .05       0
  4970.4     .12       0    5000     .07       0    5006     .12       0
  5346.5     .16       0
Bank Sta=5000,5006
XS Rating Curve= 0 ,0
Exp/Cntr=0.3,0.1

Type RM Length L Ch R = 1 ,4608    ,1197,1197,1197
BEGIN DESCRIPTION:
UNT0499 IN WICK 8.0
END DESCRIPTION:
XS GIS Cut Line= 2
      3566651.34      10249305.7      3565838.81     10248373.37
#Sta/Elev= 30
  4365.6  286.03  4552.4  277.49  4687.2  273.99  4814.8  271.79  4845.3   271.3
  4906.5  271.01    4935  270.21  4970.1   270.9  4984.3   270.1  4991.9  265.98
  4998.6  264.45  5003.2  264.23  5005.9  263.73  5009.2  264.23  5012.8  267.52
  5020.4  270.54  5027.1  271.01  5055.5   269.9  5119.1   269.6  5250.1  271.04
  5303.3  270.88  5345.9  271.91  5381.2  273.47  5409.6   276.1  5417.3  277.47
  5438.1  278.89  5480.9  283.52  5544.5  289.32  5558.7  291.25  5602.3  295.17
#Mann= 6 ,-1 , 0
  4365.6     .05       0  4814.8     .16       0  4845.3     .12       0
  5003.2     .07       0  5009.2     .12       0  5250.1     .16       0
Bank Sta=5003.2,5009.2
XS Rating Curve= 0 ,0
Exp/Cntr=0.3,0.1

Type RM Length L Ch R = 1 ,3411    ,418,418,418
BEGIN DESCRIPTION:
UNT0499 IN WICK 6.0
END DESCRIPTION:
XS GIS Cut Line= 3
      3567125.32     10249029.68      3566792.11     10248591.64
      3566392.07     10248191.61
#Sta/Elev= 30
  4469.6  284.81  4484.6  284.89  4499.1  283.77    4549  282.34  4598.9  282.01
  4663.4   279.7  4713.3  279.14  4748.6  279.66  4798.5   276.8  4827.6  273.06
    4863  270.13  4910.1  267.72  4969.7  268.28  4977.3   267.1  4983.6  266.99
  4991.9   263.4  4995.2   262.8  4997.9   262.3  5001.2   262.8  5012.7  263.41
  5016.8  267.32  5023.5  267.32  5034.1  268.69  5053.2  268.41  5104.8  267.26
  5174.6  268.12    5317  274.89  5373.5  280.06  5387.7   280.6  5585.7  294.49
#Mann= 6 ,-1 , 0
  4469.6     .05       0  4910.1     .12       0  4995.2     .07       0
  5001.2     .12       0  5053.2      .1       0  5174.6     .16       0
Bank Sta=4995.2,5001.2
XS Rating Curve= 0 ,0
Exp/Cntr=0.3,0.1

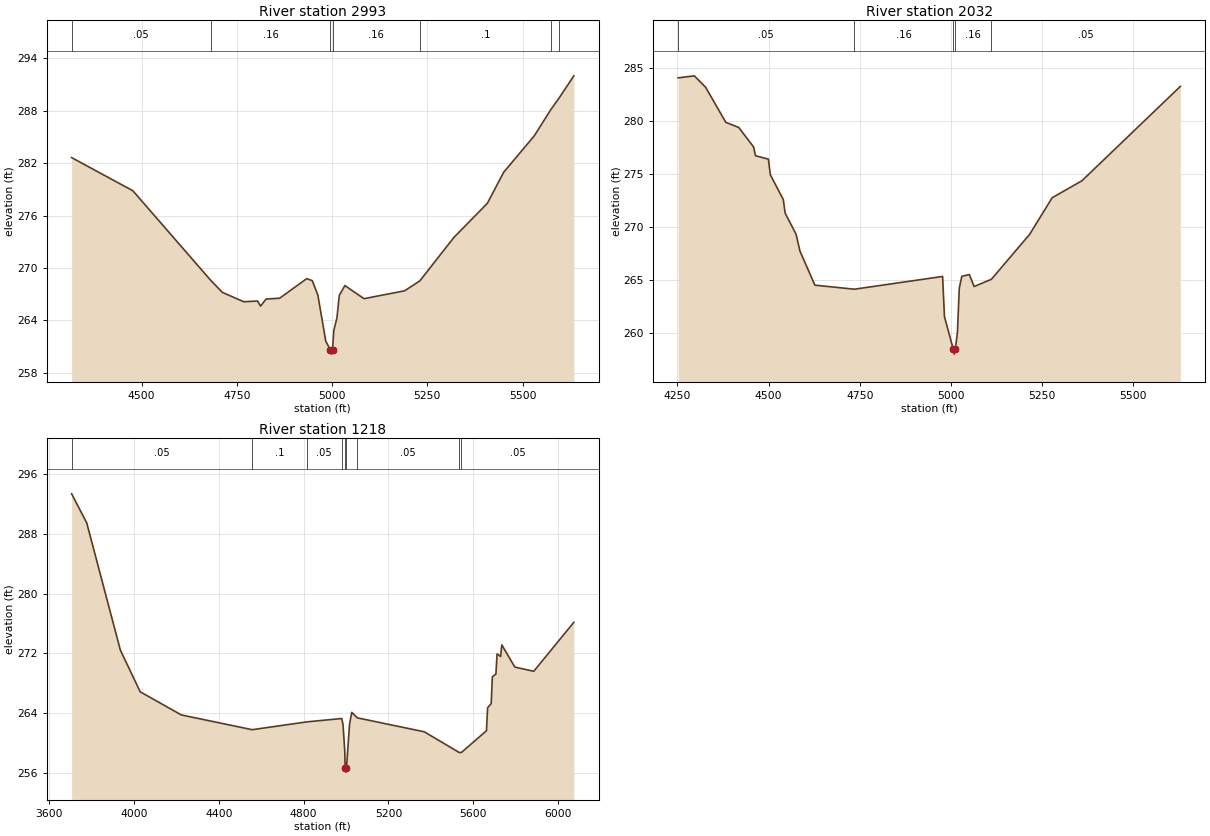
Type RM Length L Ch R = 1 ,2993    ,961,961,961
BEGIN DESCRIPTION:
UNT0499 IN WICK 5.0
END DESCRIPTION:
XS GIS Cut Line= 4
      3567321.35      10248975.7      3567366.22     10248700.23
      3566909.03     10248077.22      3566774.46     10247847.15
#Sta/Elev= 30
  4316.2  282.62  4476.9  278.83  4681.1   268.6  4711.8  267.21  4768.1  266.14
  4804.4  266.22  4812.1  265.64  4826.7  266.45  4862.2  266.54  4933.3  268.78
  4947.9  268.55  4962.6   266.9  4983.4  261.63  4995.1  260.65  4997.8  260.15
  5001.1  260.65  5004.3  262.82  5012.7  264.31  5018.9  266.87  5033.6  267.99
  5083.7  266.49  5190.3  267.39  5230.2  268.52  5319.9   273.5  5407.5  277.39
  5450.5  280.95  5530.6   285.1    5575  288.16  5594.8  289.36  5634.6  291.97
#Mann= 7 ,-1 , 0
  4316.2     .05       0  4681.1     .16       0  4995.1     .07       0
  5001.1     .16       0  5230.2      .1       0    5575     .05       0
  5594.8      .1       0
Bank Sta=4995.1,5001.1
XS Rating Curve= 0 ,0
Exp/Cntr=0.3,0.1

Type RM Length L Ch R = 1 ,2032    ,814,814,814
BEGIN DESCRIPTION:
Mapping XS 44db7b2d
END DESCRIPTION:
XS GIS Cut Line= 3
      3567614.73     10249044.69      3567883.83     10248002.99
      3567718.93     10247751.29
#Sta/Elev= 30
  4251.9  284.03  4296.3  284.22  4327.3  283.15  4382.7  279.84  4418.2  279.36
  4458.9  277.52    4464   276.7  4499.5  276.38  4504.7  274.91  4540.2  272.58
  4545.3   271.3  4575.2  269.32    4586  267.72  4626.9  264.52  4735.3  264.14
    4977  265.34  4982.1  261.56    5006  258.53  5008.8  258.03    5012  258.53
  5017.6  260.05  5022.8  264.25  5029.7  265.35  5050.3  265.52  5063.4  264.39
  5110.7  265.07  5215.6   269.3  5277.5  272.75  5358.8  274.34  5628.7  283.22
#Mann= 5 ,-1 , 0
  4251.9     .05       0  4735.3     .16       0    5006     .07       0
    5012     .16       0  5110.7     .05       0
Bank Sta=5006,5012
XS Rating Curve= 0 ,0
Exp/Cntr=0.3,0.1

Type RM Length L Ch R = 1 ,1218    ,0,0,0
BEGIN DESCRIPTION:
UNT0499 IN WICK 1.0
END DESCRIPTION:
XS GIS Cut Line= 4
       3567720.7     10249774.26      3568022.06     10249645.43
      3568363.02      10248289.9      3568073.28     10247714.98
#Sta/Elev= 30
  3705.7  293.37  3776.9  289.47  3935.6  272.41  4029.2  266.82  4223.1  263.72
  4557.6  261.74  4815.4  262.79  4979.8  263.24    4986  262.45  4994.1  258.96
  4996.2  256.55    4999  256.05  5002.2  256.55  5016.9  262.49  5027.3  264.06
  5053.3  263.33  5369.3  261.46  5534.4  258.68  5544.8  258.69  5662.7   261.6
  5668.3  264.69    5685  265.23  5690.6  268.84  5707.3  269.19  5712.9  271.91
  5729.6  271.56  5735.2  273.11  5796.5  270.14  5885.8  269.57    6075  276.14
#Mann= 9 ,-1 , 0
  3705.7     .05       0  4557.6      .1       0  4815.4     .05       0
  4979.8     .16       0  4996.2     .07       0  5002.2     .16       0
  5053.3     .05       0  5534.4     .16       0  5544.8     .05       0
Bank Sta=4996.2,5002.2
XS Rating Curve= 0 ,0
Exp/Cntr=0.3,0.1

Chan Stop Cuts=-1
Use User Specified Reach Order=0
Composite Channel Slope=5