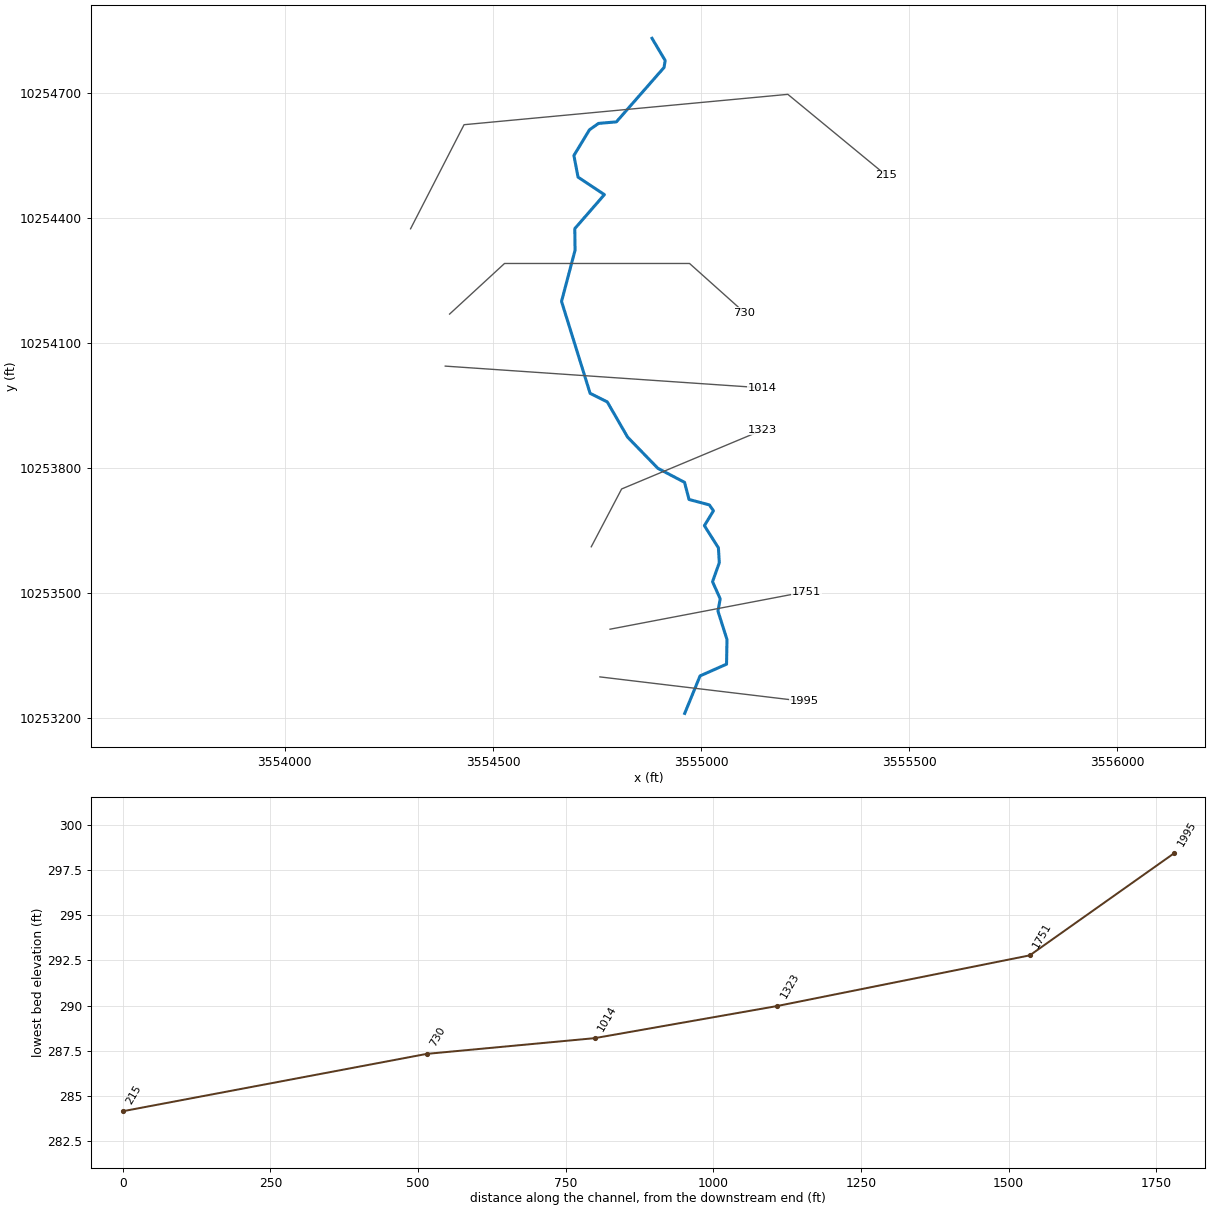
--- WICKSONCREEKTRIB.prj (project) ---

Proj Title=WICKSON CREEK TRIB 31 1
Current Plan=p01
Default Exp/Contr=0.3,0.1
English Units
Geom File=g01
Flow File=f01
Plan File=p01
Y Axis Title=Elevation
X Axis Title(PF)=Main Channel Distance
X Axis Title(XS)=Station
BEGIN DESCRIPTION:
UNT012 IN WICK
END DESCRIPTION:
DSS Export Rating Curves= 0
DSS Export Rating Curve Sorted= 0
DSS Export Volume Flow Curves= 0
DXF OffsetX= 0
DXF OffsetY= 0
DXF ScaleX= 1
DXF ScaleY= 10

--- WICKSONCREEKTRIB.p01 (plan) ---

Plan Title=Multiple Run
Short Identifier=Multiple
Geom File=g01
Flow File=f01
Subcritical Flow
K Sum by GR= 0
Std Step Tol= 0.01
Critical Tol= 0.01
Num of Std Step Trials= 20
Max Error Tol= 0.3
Flow Tol Ratio= 0.001
Split Flow NTrial= 30
Split Flow Tol= 0.02
Split Flow Ratio= 0.02
Log Output Level= 0
Friction Slope Method= 1
Unsteady Friction Slope Method= 2
Unsteady Bridges Friction Slope Method= 1
Parabolic Critical Depth
Global Vel Dist=  1 , 1 , 1
Global Log Level= 0
CheckData=True
Encroach Param= -1, 0, 0, 0
BEGIN DESCRIPTION:
Multiple Run
END DESCRIPTION:

--- WICKSONCREEKTRIB.f01 (steady flow) ---

Flow Title=Multiple
Program Version=4.10
Number of Profiles= 7
Profile Names=10-year,25-year,50-year,1pct_min,100-year,1pct_plu,500-year
River Rch & RM=UNT012 IN WICK,Reach-1         ,1995
     222     286     336     291     393     532     539
River Rch & RM=WICKSONCRTRIB311,Reach-1         ,1995
     222     286     336     291     393     532     539
Boundary for River Rch & Prof#=WICKSONCRTRIB311,Reach-1         , 1
Up Type= 0
Dn Type= 3
Dn Slope=0.005
Boundary for River Rch & Prof#=WICKSONCRTRIB311,Reach-1         , 2
Up Type= 0
Dn Type= 3
Dn Slope=0.005
Boundary for River Rch & Prof#=WICKSONCRTRIB311,Reach-1         , 3
Up Type= 0
Dn Type= 3
Dn Slope=0.005
Boundary for River Rch & Prof#=WICKSONCRTRIB311,Reach-1         , 4
Up Type= 0
Dn Type= 3
Dn Slope=0.005
Boundary for River Rch & Prof#=WICKSONCRTRIB311,Reach-1         , 5
Up Type= 0
Dn Type= 3
Dn Slope=0.005
Boundary for River Rch & Prof#=WICKSONCRTRIB311,Reach-1         , 6
Up Type= 0
Dn Type= 3
Dn Slope=0.005
Boundary for River Rch & Prof#=WICKSONCRTRIB311,Reach-1         , 7
Up Type= 0
Dn Type= 3
Dn Slope=0.005
DSS Import GetInterval= 0
DSS Import GetPeak= 0
DSS Import FillOption= 0

--- WICKSONCREEKTRIB.g01 (geometry) ---

Geom Title=Existing Conditions
Program Version=4.10

River Reach=WICKSONCRTRIB311,Reach-1
Reach XY= 30
      3554960.64     10253210.16      3554997.53     10253300.22
      3555061.12     10253328.35      3555062.19     10253387.57
      3555040.48     10253455.93      3555045.91     10253485.22
      3555027.46     10253526.46      3555043.74     10253572.03
      3555041.57     10253607.84      3555007.93       10253661.
      3555029.63     10253696.81      3555019.87     10253710.92
      3554971.04     10253723.94      3554960.19     10253765.17
      3554896.17     10253798.81      3554823.47     10253873.68
      3554774.64     10253958.31      3554733.41     10253978.93
      3554664.78     10254199.76      3554697.23     10254322.58
      3554696.61     10254374.56      3554767.71     10254456.19
      3554704.42     10254498.28      3554694.47     10254550.23
      3554731.91     10254611.98      3554753.46     10254627.22
       3554796.6     10254631.05      3554911.01     10254761.65
      3554913.72     10254778.31      3554882.11     10254831.64

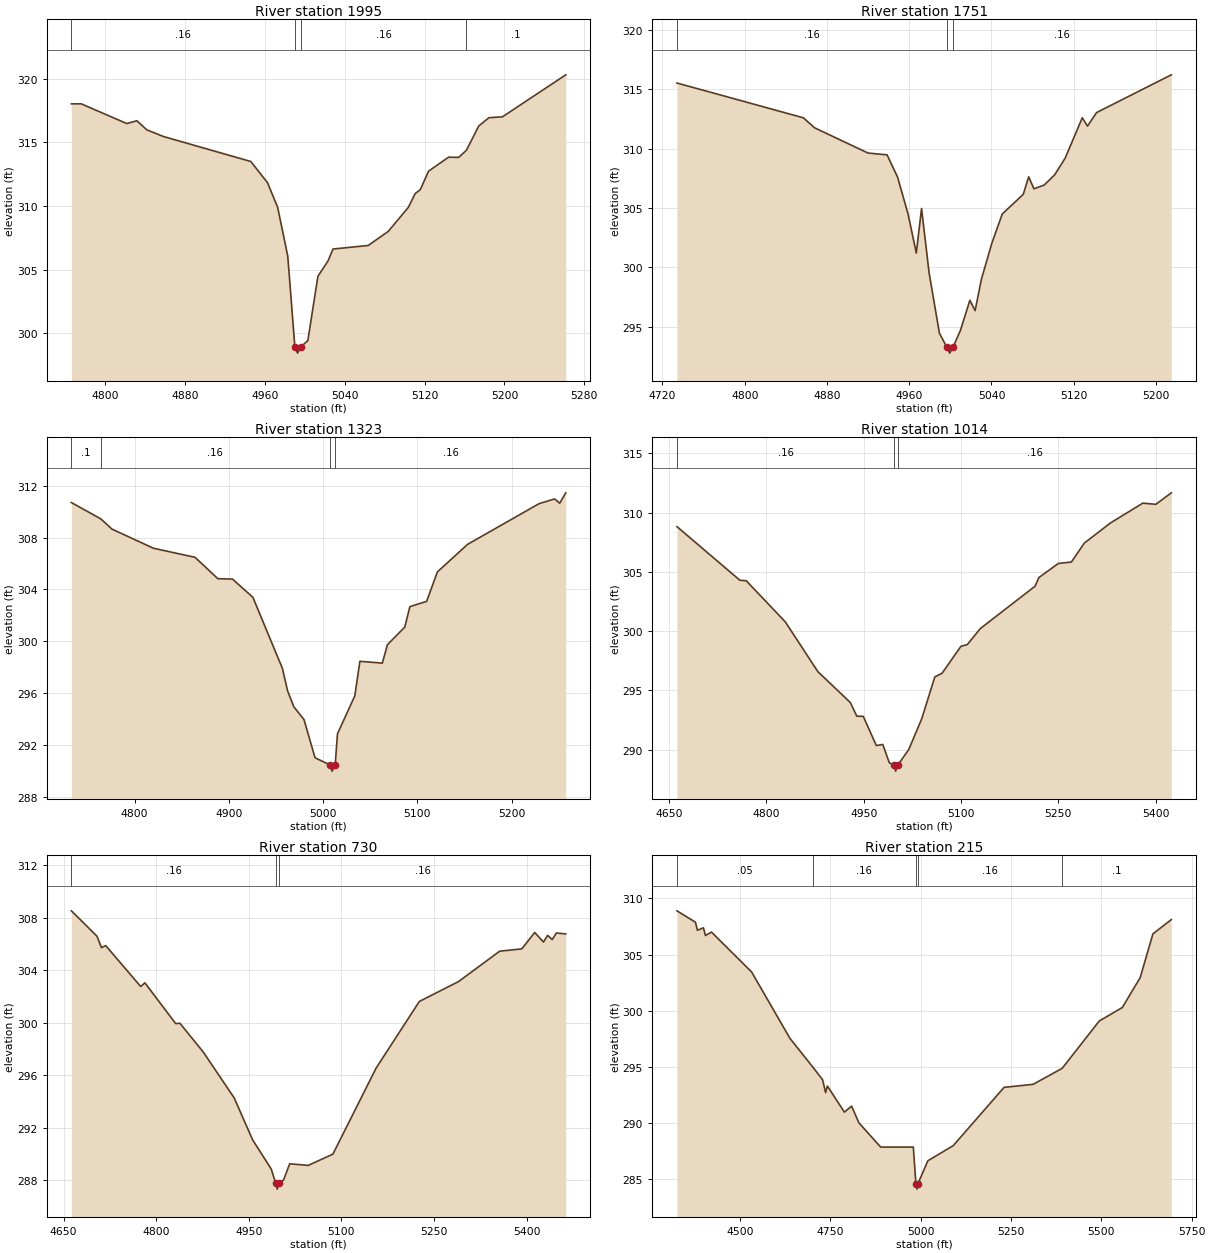
Type RM Length L Ch R = 1 ,1995    ,244,244,244
BEGIN DESCRIPTION:
UNT012 IN WICK 3.0
END DESCRIPTION:
XS GIS Cut Line= 2
      3554756.95     10253297.79      3555248.54     10253238.93
#Sta/Elev= 30
  4766.3  318.02  4776.2  318.02  4821.8  316.47  4831.9  316.69    4842  315.97
  4858.6  315.45    4946  313.49  4962.8  311.81  4972.9  309.88    4983  306.05
  4990.1  298.93  4992.8  298.43  4996.1  298.93  5003.1  299.41  5013.2  304.47
  5023.3  305.67  5028.3  306.61  5063.6  306.89  5083.7     308  5103.8  309.89
  5110.6  310.97  5115.7  311.27    5124  312.73  5144.1  313.83  5154.2  313.81
  5161.9  314.37  5174.3  316.28  5184.4  316.93    5198     317  5261.4   320.3
#Mann= 4 ,-1 , 0
  4766.3     .16       0  4990.1     .07       0  4996.1     .16       0
  5161.9      .1       0
Bank Sta=4990.1,4996.1
XS Rating Curve= 0 ,0
Exp/Cntr=0.3,0.1

Type RM Length L Ch R = 1 ,1751    ,428,428,428
BEGIN DESCRIPTION:
Mapping XS 6f46bc4f
END DESCRIPTION:
XS GIS Cut Line= 2
       3554781.3     10253412.36      3555253.55     10253502.65
#Sta/Elev= 30
  4734.1  315.53  4857.1   312.6  4867.9  311.76    4920  309.63  4938.5  309.48
  4948.7   307.6  4958.9  304.49  4966.9  301.21    4972  304.96  4979.3  299.57
  4989.4  294.45  4996.6  293.28  4999.4  292.78  5002.6  293.28  5009.8  294.69
    5019  297.23  5024.1  296.36  5030.2     299  5040.3  302.02  5050.5   304.5
  5070.9  306.15  5076.2  307.63  5081.3  306.62  5091.3  306.94  5101.4  307.79
  5111.6  309.19  5128.3   312.6  5133.4   311.9  5142.2  313.04  5214.9  316.22
#Mann= 3 ,-1 , 0
  4734.1     .16       0  4996.6     .07       0  5002.6     .16       0
Bank Sta=4996.6,5002.6
XS Rating Curve= 0 ,0
Exp/Cntr=0.3,0.1

Type RM Length L Ch R = 1 ,1323    ,309,309,309
BEGIN DESCRIPTION:
Mapping XS 5d45a5a5
END DESCRIPTION:
XS GIS Cut Line= 3
      3554736.18     10253610.31      3554809.08     10253749.17
      3555148.26     10253891.07
#Sta/Elev= 30
  4732.9  310.71  4764.3  309.44  4775.9  308.66    4820  307.18  4864.1  306.48
  4888.3  304.83  4903.8   304.8  4925.5  303.39  4956.8   297.9  4962.2  296.19
  4968.9  294.94  4979.7  293.95  4991.4     291  5006.8  290.47  5009.5  289.97
  5012.8  290.47  5015.2  292.85  5033.6  295.78    5039  298.45  5062.8  298.31
  5068.2  299.73  5086.6  301.09    5092  302.67  5109.8  303.08  5121.2  305.35
  5153.2  307.48    5229  310.62  5245.6  310.99    5251  310.66  5257.4  311.46
#Mann= 4 ,-1 , 0
  4732.9      .1       0  4764.3     .16       0  5006.8     .07       0
  5012.8     .16       0
Bank Sta=5006.8,5012.8
XS Rating Curve= 0 ,0
Exp/Cntr=0.3,0.1

Type RM Length L Ch R = 1 ,1014    ,284,284,284
BEGIN DESCRIPTION:
UNT012 IN WICK 2.0
END DESCRIPTION:
XS GIS Cut Line= 2
      3554385.44     10254044.31      3555145.86     10253992.23
#Sta/Elev= 30
  4662.1  308.82    4759   304.3    4769  304.25  4829.2  300.78  4879.3  296.59
  4929.4  293.98  4939.4  292.83  4949.4  292.81  4969.5  290.35  4979.5  290.44
  4989.5   288.9  4996.5  288.69  4999.3  288.19  5002.5  288.69  5019.6  290.02
  5039.6  292.62  5059.7  296.14  5070.9  296.45  5099.8  298.71  5109.8  298.87
  5129.9  300.22  5214.2  303.79  5220.1  304.52  5250.1  305.71  5270.2  305.83
  5290.2  307.43  5330.3  309.12  5380.4   310.8  5400.5   310.7  5424.3  311.67
#Mann= 3 ,-1 , 0
  4662.1     .16       0  4996.5     .07       0  5002.5     .16       0
Bank Sta=4996.5,5002.5
XS Rating Curve= 0 ,0
Exp/Cntr=0.3,0.1

Type RM Length L Ch R = 1 ,730     ,515,515,515
BEGIN DESCRIPTION:
Mapping XS 4982f8b2
END DESCRIPTION:
XS GIS Cut Line= 4
      3554395.88      10254169.3      3554527.83     10254290.84
      3554972.27     10254290.84      3555104.23     10254172.77
#Sta/Elev= 30
  4662.6  308.54    4704  306.61  4711.4  305.73  4718.2  305.89  4774.9  302.77
  4781.7  303.05  4831.6  299.94  4838.4  299.97  4876.3  297.77  4926.3  294.28
  4956.3  291.07  4986.3  288.86  4993.3  287.82    4996  287.32  4999.3  287.82
  5006.3  288.02  5016.3  289.25  5046.3  289.13  5086.3  289.99  5156.3  296.55
  5226.3  301.63  5289.6  303.14  5356.4  305.46  5392.3  305.64  5413.2  306.89
  5427.4  306.16  5434.1  306.67  5441.6  306.35  5448.3  306.85  5463.5  306.78
#Mann= 3 ,-1 , 0
  4662.6     .16       0  4993.3     .07       0  4999.3     .16       0
Bank Sta=4993.3,4999.3
XS Rating Curve= 0 ,0
Exp/Cntr=0.3,0.1

Type RM Length L Ch R = 1 ,215     ,0,0,0
BEGIN DESCRIPTION:
UNT012 IN WICK 1.0
END DESCRIPTION:
XS GIS Cut Line= 4
      3554302.14     10254374.18      3554430.61     10254624.17
      3555208.39     10254697.09      3555444.48     10254502.66
#Sta/Elev= 30
  4325.6  308.89  4376.8  307.88  4382.4  307.16    4399  307.38  4404.6  306.69
  4421.1     307  4532.1  303.46  4638.3  297.55  4700.8  295.03  4728.7  293.87
    4737  292.73    4742  293.31    4789  290.99    4809  291.52  4829.1  290.04
  4889.4  287.88  4979.8  287.88  4986.8  284.64  4989.6  284.14  4992.8  284.64
    5020  286.66  5090.3  288.01  5230.9  293.19  5311.2  293.46  5391.7  294.88
  5494.2  299.09  5558.1  300.29  5607.6  302.95  5642.8  306.84  5693.7  308.11
#Mann= 5 ,-1 , 0
  4325.6     .05       0  4700.8     .16       0  4986.8     .07       0
  4992.8     .16       0  5391.7      .1       0
Bank Sta=4986.8,4992.8
XS Rating Curve= 0 ,0
Exp/Cntr=0.3,0.1

Chan Stop Cuts=-1
Use User Specified Reach Order=0
Composite Channel Slope=5