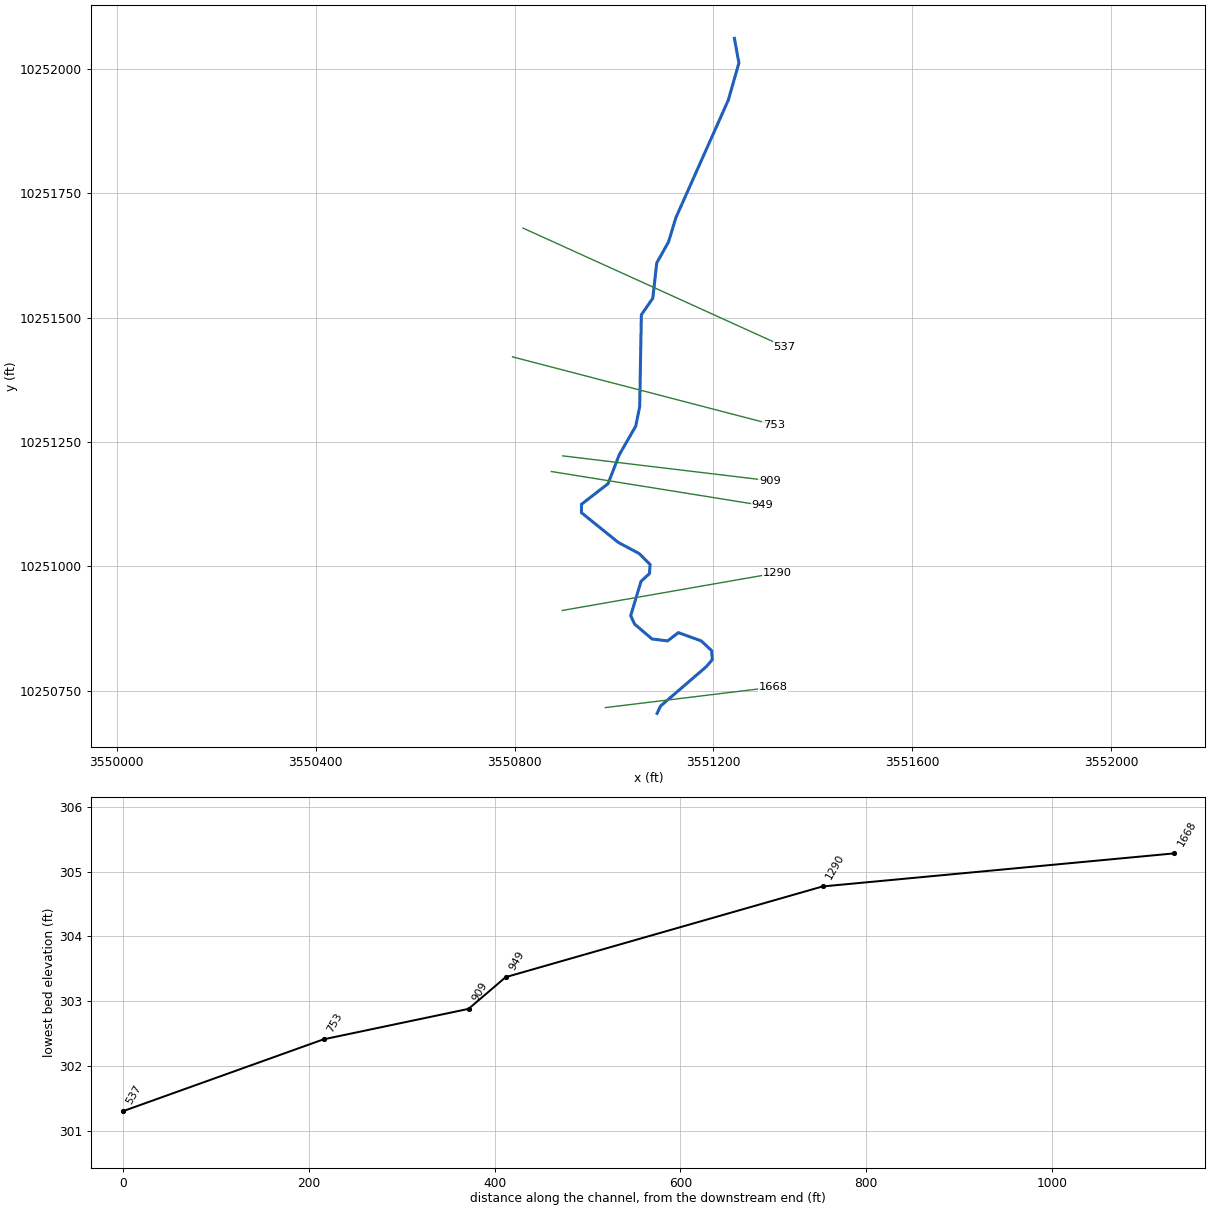
--- WICKSONCREEKTRIB.prj (project) ---

Proj Title=WICKSON CREEK TRIB 31 3 2
Current Plan=p01
Default Exp/Contr=0.3,0.1
English Units
Geom File=g01
Flow File=f01
Plan File=p01
Y Axis Title=Elevation
X Axis Title(PF)=Main Channel Distance
X Axis Title(XS)=Station
BEGIN DESCRIPTION:
UNT011 IN WICK
END DESCRIPTION:
DSS Export Rating Curves= 0
DSS Export Rating Curve Sorted= 0
DSS Export Volume Flow Curves= 0
DXF OffsetX= 0
DXF OffsetY= 0
DXF ScaleX= 1
DXF ScaleY= 10

--- WICKSONCREEKTRIB.p01 (plan) ---

Plan Title=Multiple Run
Program Version=4.10
Short Identifier=Multiple
Geom File=g01
Flow File=f01
Subcritical Flow
K Sum by GR= 0
Std Step Tol= 0.01
Critical Tol= 0.01
Num of Std Step Trials= 20
Max Error Tol= 0.3
Flow Tol Ratio= 0.001
Split Flow NTrial= 30
Split Flow Tol= 0.02
Split Flow Ratio= 0.02
Log Output Level= 0
Friction Slope Method= 1
Unsteady Friction Slope Method= 2
Unsteady Bridges Friction Slope Method= 1
Parabolic Critical Depth
Global Vel Dist= 1 , 1 , 1
Global Log Level= 0
CheckData=True
Encroach Param=-1 ,0,0, 0
BEGIN DESCRIPTION:
Multiple Run
END DESCRIPTION:
Computation Interval=1HOUR
Output Interval=1HOUR
Run HTab= 0
Run UNet= 0
Run PostProcess= 0
Run WQNet= 0
UNET Theta= 1
UNET Theta Warmup= 1
UNET ZTol= 0.02
UNET ZSATol= 0.05
UNET MxIter= 20
UNET MaxInSteps= 0
UNET DtIC= 0
UNET DtMin= 0
UNET MaxCRTS= 20
UNET WFStab= 2
UNET SFStab= 1
UNET WFX= 1
UNET SFX= 1
UNET DSS MLevel= 4
UNET DZMax Abort= 100
UNET Convert EG Bridges= 0
UNET Use Existing IB Tables=-1
UNET Froude Reduction=False
UNET Froude Limit= 1
UNET Froude Power= 10
UNET Time Slicing=0,0, 5
UNET Junction Losses=0
Instantaneous Interval=1HOUR
Write IC File= 0
Write IC File at Sim End=0
Echo Input=False
Echo Parameters=False
Echo Output=False
Write Detailed= 0
WQ AD Non Conservative
WQ ULTIMATE=-1
WQ Max Comp Step=1HOUR
WQ Output Interval=15MIN
WQ Output Selected Increments= 0
WQ Output face flow=0
WQ Output face velocity=0
WQ Output face area=0
WQ Output face dispersion=0
WQ Output cell volume=0
WQ Output cell surface area=0
WQ Output cell continuity=0
WQ Output cumulative cell continuity=0
WQ Output face conc=0
WQ Output face dconc_dx=0
WQ Output face courant=0
WQ Output face peclet=0
WQ Output face adv mass=0
WQ Output face disp mass=0
WQ Output cell mass=0
WQ Output cell source sink temp=0
WQ Output cell source sink nsm=0
WQ Output MaxMinRange=-1
WQ Daily Max Min Mean=-1
WQ Daily Range=0
WQ Daily Time=0
WQ Create Restart=0
WQ Fixed Restart=0
WQ System Summary=0
WQ Use Fixed Temperature=0
Sorting and Armoring Iterations= 10
XS Update Threshold= 0.02
Hydraulics Update Threshold= 0.02
Energy Slope Method= 1
Volume Change Method= 0
XS Weighting Method= 0
Number of US Weighted Cross Sections= 1
Number of DS Weighted Cross Sections= 1
Upstream XS Weight=0.25
Main XS Weight=0.5
Downstream XS Weight=0.25
Number of DS XS's Weighted with US Boundary= 1
Upstream Boundary Weight= 1
Weight of XSs Associated with US Boundary= 0
Number of US XS's Weighted with DS Boundary= 1
Downstream Boundary Weight= 0.5
Weight of XSs Associated with DS Boundary= 0.5
Sediment Output Level= 4
Mass or Volume Output= 0
Output Increment Type= 1
Profile and TS Output Increment= 10
XS Output Flag= 0
XS Output Increment= 10
Disregard all LS=0
Disregard all Conn=0
Disregard all Breaches=0
Disregard all Pumps=0

--- WICKSONCREEKTRIB.f01 (steady flow) ---

Flow Title=Multiple
Program Version=4.10
Number of Profiles= 7
Profile Names=10-year,25-year,50-year,1pct_min,100-year,1pct_plu,500-year
River Rch & RM=UNT011 IN WICK,Reach-1         ,1668
     187     236     272     232     314     424     415
River Rch & RM=WICKSONCRTRB312,Reach-1         ,1668
     187     236     272     232     314     424     415
River Rch & RM=WICKSONCRTRB3132,Reach-1         ,1668
     187     236     272     232     314     424     415
Boundary for River Rch & Prof#=WICKSONCRTRB3132,Reach-1         , 1
Up Type= 0
Dn Type= 3
Dn Slope=0.005
Boundary for River Rch & Prof#=WICKSONCRTRB3132,Reach-1         , 2
Up Type= 0
Dn Type= 3
Dn Slope=0.005
Boundary for River Rch & Prof#=WICKSONCRTRB3132,Reach-1         , 3
Up Type= 0
Dn Type= 3
Dn Slope=0.005
Boundary for River Rch & Prof#=WICKSONCRTRB3132,Reach-1         , 4
Up Type= 0
Dn Type= 3
Dn Slope=0.005
Boundary for River Rch & Prof#=WICKSONCRTRB3132,Reach-1         , 5
Up Type= 0
Dn Type= 3
Dn Slope=0.005
Boundary for River Rch & Prof#=WICKSONCRTRB3132,Reach-1         , 6
Up Type= 0
Dn Type= 3
Dn Slope=0.005
Boundary for River Rch & Prof#=WICKSONCRTRB3132,Reach-1         , 7
Up Type= 0
Dn Type= 3
Dn Slope=0.005
DSS Import GetInterval= 0
DSS Import GetPeak= 0
DSS Import FillOption= 0

--- WICKSONCREEKTRIB.g01 (geometry) ---

Geom Title=Existing Conditions
Program Version=4.10

River Reach=WICKSONCRTRB3132,Reach-1
Reach XY= 30
      3551086.65     10250704.18      3551093.57     10250718.86
      3551185.62     10250798.17      3551197.58     10250812.13
      3551196.28     10250830.36      3551175.45     10250849.89
      3551129.45     10250866.55      3551107.74     10250849.89
      3551076.49      10250853.8      3551041.33     10250883.75
      3551033.52     10250900.67      3551054.35     10250969.68
      3551071.28     10250985.31      3551072.58     10251003.54
      3551050.45     10251025.67      3551008.78     10251047.81
      3550934.56      10251107.7      3550934.56     10251124.63
      3550987.95       10251166.       3551010.5     10251224.16
      3551043.58     10251281.58      3551051.64     10251321.22
      3551054.97     10251505.71      3551077.98       10251539.
      3551085.92     10251609.98      3551109.69     10251652.42
      3551124.35     10251700.91      3551229.88     10251937.59
      3551251.15     10252012.05      3551242.11     10252061.64

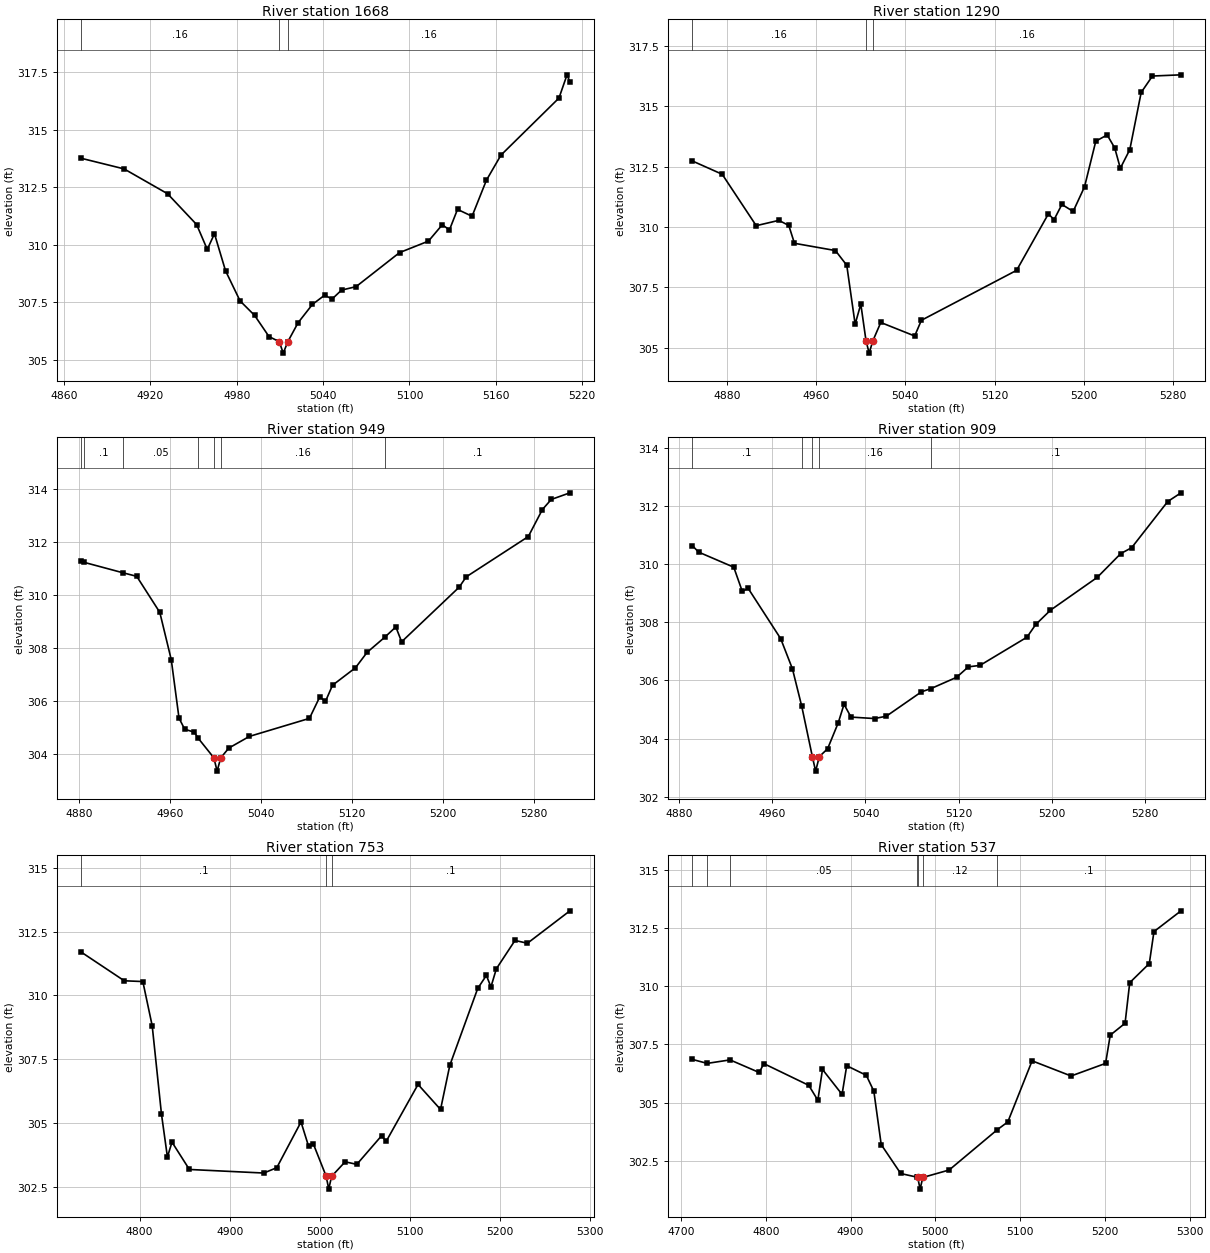
Type RM Length L Ch R = 1 ,1668    ,378,378,378
BEGIN DESCRIPTION:
UNT011 IN WICK 3.0
END DESCRIPTION:
XS GIS Cut Line= 2
      3550982.63     10250715.78      3551319.64     10250756.82
#Sta/Elev= 30
    4872  313.75  4901.7  313.29  4931.9  312.21  4952.1  310.87  4959.5  309.79
  4964.5  310.47  4972.2  308.86  4982.3  307.55  4992.4  306.92  5002.4     306
  5009.5  305.78  5012.3  305.28  5015.5  305.78  5022.6   306.6  5032.6   307.4
  5041.1   307.8  5046.2  307.63  5052.8  308.02  5062.9  308.17  5093.1  309.65
  5113.2  310.15  5122.8  310.86  5127.8  310.64  5133.4  311.53  5143.5  311.23
  5153.5   312.8  5163.6  313.89  5203.9  316.37  5209.5  317.38  5211.5  317.07
#Mann= 3 ,-1 , 0
    4872     .16       0  5009.5     .07       0  5015.5     .16       0
Bank Sta=5009.5,5015.5
XS Rating Curve= 0 ,0
Exp/Cntr=0.3,0.1

Type RM Length L Ch R = 1 ,1290    ,341,341,341
BEGIN DESCRIPTION:
Mapping XS e7a469a5
END DESCRIPTION:
XS GIS Cut Line= 2
      3550895.78     10250911.08      3551327.32      10250986.6
#Sta/Elev= 30
    4849  312.73  4875.7  312.18  4906.2  310.05  4926.5  310.27  4935.4  310.06
  4940.5  309.32  4977.2  309.02  4987.4  308.41  4994.9  305.97    5000   306.8
  5004.7  305.27  5007.5  304.77  5010.7  305.27  5017.9  306.04  5048.3  305.48
  5054.3  306.13  5139.7   308.2  5168.2  310.54  5173.3   310.3  5180.3  310.93
  5190.4  310.64  5200.6  311.66  5210.7  313.55  5220.9  313.81  5227.7  313.27
  5232.7  312.43  5241.2   313.2  5251.4  315.57  5261.5  316.25  5287.1   316.3
#Mann= 3 ,-1 , 0
    4849     .16       0  5004.7     .07       0  5010.7     .16       0
Bank Sta=5004.7,5010.7
XS Rating Curve= 0 ,0
Exp/Cntr=0.3,0.1

Type RM Length L Ch R = 1 ,949     ,40,40,40
BEGIN DESCRIPTION:
Mapping XS a29f725d
END DESCRIPTION:
XS GIS Cut Line= 2
      3550874.02     10251190.54      3551298.27     10251122.36
#Sta/Elev= 30
  4882.3  311.28  4884.5  311.25  4919.2  310.85    4931  310.72  4951.3  309.36
  4961.4  307.57  4968.2  305.37  4973.2  304.95  4981.6  304.84  4985.1  304.61
  4998.9  303.87  5001.7  303.37  5004.9  303.87    5012  304.24  5030.1  304.68
  5082.9  305.36    5092  306.17    5097     306  5103.2  306.61  5123.4  307.27
  5133.6  307.85  5149.1  308.42  5158.9  308.81    5164  308.25  5214.6  310.31
  5220.8   310.7  5275.4  312.22  5287.8  313.24  5295.6  313.62    5312  313.87
#Mann= 7 ,-1 , 0
  4882.3     .08       0  4884.5      .1       0  4919.2     .05       0
  4985.1     .16       0  4998.9     .07       0  5004.9     .16       0
  5149.1      .1       0
Bank Sta=4998.9,5004.9
XS Rating Curve= 0 ,0
Exp/Cntr=0.3,0.1

Type RM Length L Ch R = 1 ,909     ,156,156,156
BEGIN DESCRIPTION:
Mapping XS c642c058
END DESCRIPTION:
XS GIS Cut Line= 2
      3550896.83     10251222.01      3551313.45      10251172.1
#Sta/Elev= 30
  4891.4  310.64  4896.7  310.42  4926.9   309.9  4934.2  309.07  4939.3  309.17
  4967.2  307.44  4977.3   306.4  4985.3  305.11  4994.4  303.38  4997.2  302.88
  5000.4  303.38  5007.5  303.65  5016.6  304.54  5021.6  305.18  5027.6  304.74
  5047.8  304.69  5057.9  304.77  5088.1  305.61  5096.2  305.72  5118.3  306.11
  5128.4  306.47  5138.4  306.52  5178.7  307.49  5186.3  307.93  5198.9  308.42
  5239.1  309.55  5259.3  310.37  5268.6  310.57  5299.6  312.16    5311  312.46
#Mann= 5 ,-1 , 0
  4891.4      .1       0  4985.3     .16       0  4994.4     .07       0
  5000.4     .16       0  5096.2      .1       0
Bank Sta=4994.4,5000.4
XS Rating Curve= 0 ,0
Exp/Cntr=0.3,0.1

Type RM Length L Ch R = 1 ,753     ,216,216,216
BEGIN DESCRIPTION:
UNT011 IN WICK 2.0
END DESCRIPTION:
XS GIS Cut Line= 2
      3550795.97     10251421.07      3551321.17     10251284.35
#Sta/Elev= 30
  4735.2  311.69  4782.9  310.57  4803.5  310.54  4813.9  308.81  4824.2  305.35
  4830.8  303.67  4835.9  304.25  4855.2  303.18  4937.9  303.04  4952.3  303.25
  4979.2  305.04  4987.7  304.08  4992.8  304.19  5007.2  302.91    5010  302.41
  5013.2  302.91  5028.2  303.48  5041.2  303.38  5068.7   304.5  5073.8  304.28
  5109.2  306.51  5134.2  305.53  5144.5  307.26  5175.5  310.27  5185.1  310.78
  5190.2  310.33  5196.2  311.04  5216.9  312.15  5230.7  312.04  5277.9  313.31
#Mann= 3 ,-1 , 0
  4735.2      .1       0  5007.2     .07       0  5013.2      .1       0
Bank Sta=5007.2,5013.2
XS Rating Curve= 0 ,0
Exp/Cntr=0.3,0.1

Type RM Length L Ch R = 1 ,537     ,0,0,0
BEGIN DESCRIPTION:
UNT011 IN WICK 1.0
END DESCRIPTION:
XS GIS Cut Line= 2
      3550817.12     10251680.03      3551342.13     10251441.63
#Sta/Elev= 30
  4713.3  306.86  4730.7  306.69  4757.7  306.84  4792.1   306.3  4797.6  306.68
  4850.6  305.75  4861.3  305.11  4866.8  306.43  4889.9  305.36  4895.4  306.59
  4918.5  306.18  4927.4   305.5  4936.1  303.21  4959.1  301.97  4978.6  301.81
  4979.2   301.8    4982   301.3  4985.2   301.8  5016.3  302.12  5073.2  303.85
  5085.5  304.18  5114.2   306.8  5160.2  306.15  5200.9  306.69  5206.4   307.9
  5223.9  308.41  5229.4  310.15  5252.5  310.97    5258  312.34  5289.9  313.23
#Mann= 7 ,-1 , 0
  4713.3     .05       0  4730.7      .1       0  4757.7     .05       0
  4978.6     .12       0  4979.2     .07       0  4985.2     .12       0
  5073.2      .1       0
Bank Sta=4979.2,4985.2
XS Rating Curve= 0 ,0
Exp/Cntr=0.3,0.1

Chan Stop Cuts=-1
Use User Specified Reach Order=0
Composite Channel Slope=5