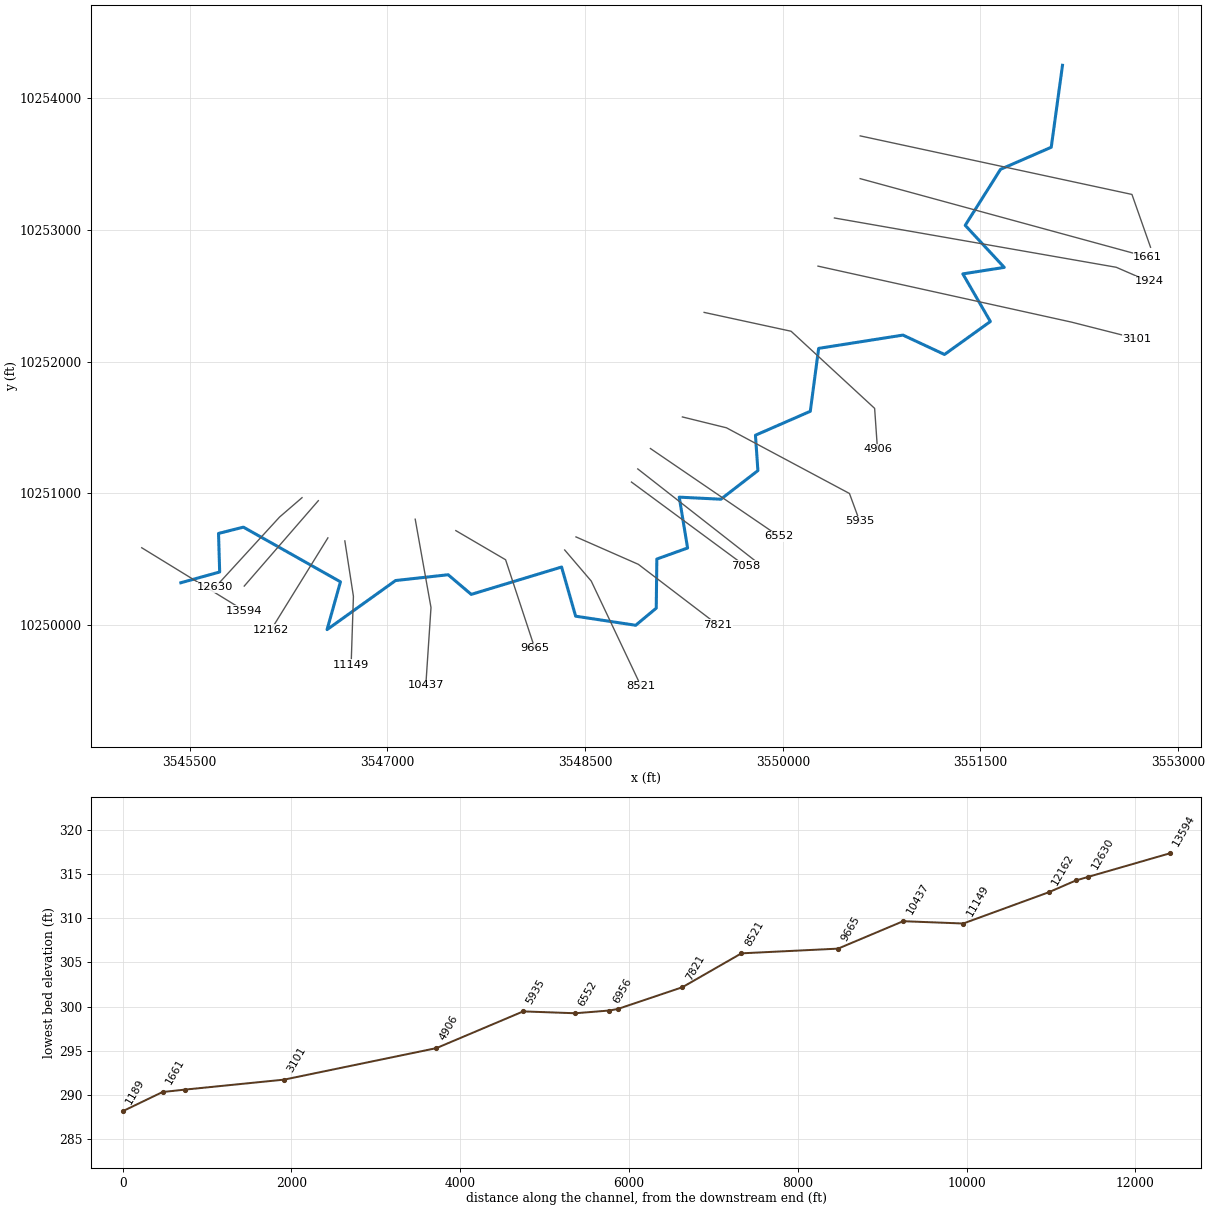
--- WICKSONCREEKTRIB.prj (project) ---

Proj Title=WICKSON CREEK TRIB 31 3
Current Plan=p01
Default Exp/Contr=0.3,0.1
English Units
Geom File=g01
Flow File=f01
Plan File=p01
Y Axis Title=Elevation
X Axis Title(PF)=Main Channel Distance
X Axis Title(XS)=Station
BEGIN DESCRIPTION:
UNT0497 IN WICK
END DESCRIPTION:
DSS Export Rating Curves= 0
DSS Export Rating Curve Sorted= 0
DSS Export Volume Flow Curves= 0
DXF Filename=UNT0497 IN WICK.
DXF OffsetX= 0
DXF OffsetY= 0
DXF ScaleX= 1
DXF ScaleY= 10

--- WICKSONCREEKTRIB.p01 (plan) ---

Plan Title=Multiple Run
Short Identifier=Multiple
Geom File=g01
Flow File=f01
Subcritical Flow
K Sum by GR= 0
Std Step Tol= 0.01
Critical Tol= 0.01
Num of Std Step Trials= 20
Max Error Tol= 0.3
Flow Tol Ratio= 0.001
Split Flow NTrial= 30
Split Flow Tol= 0.02
Split Flow Ratio= 0.02
Log Output Level= 0
Friction Slope Method= 1
Unsteady Friction Slope Method= 2
Unsteady Bridges Friction Slope Method= 1
Parabolic Critical Depth
Global Vel Dist=  1 , 1 , 1
Global Log Level= 0
CheckData=True
Encroach Param= -1, 0, 0, 0
BEGIN DESCRIPTION:
Multiple Run
END DESCRIPTION:

--- WICKSONCREEKTRIB.f01 (steady flow) ---

Flow Title=Multiple
Program Version=4.10
Number of Profiles= 7
Profile Names=10-year,25-year,50-year,1pct_min,100-year,1pct_plu,500-year
River Rch & RM=UNT0497 IN WICK,Reach-1         ,13594
     749    1016    1233    1096    1482    2004    2145
River Rch & RM=UNT0497 IN WICK,Reach-1         ,4906
     912    1250    1529    1367    1848    2500    2710
River Rch & RM=UNT0497 IN WICK,Reach-1         ,3101
     993    1363    1669    1493    2019    2730    2964
River Rch & RM=WICKSONCRTR313,Reach-1         ,13594
     749    1016    1233    1096    1482    2004    2145
River Rch & RM=WICKSONCRTR313,Reach-1         ,4906
     912    1250    1529    1367    1848    2500    2710
River Rch & RM=WICKSONCRTR313,Reach-1         ,3101
     993    1363    1669    1493    2019    2730    2964
Boundary for River Rch & Prof#=WICKSONCRTR313,Reach-1         , 1
Up Type= 0
Dn Type= 3
Dn Slope=0.005
Boundary for River Rch & Prof#=WICKSONCRTR313,Reach-1         , 2
Up Type= 0
Dn Type= 3
Dn Slope=0.005
Boundary for River Rch & Prof#=WICKSONCRTR313,Reach-1         , 3
Up Type= 0
Dn Type= 3
Dn Slope=0.005
Boundary for River Rch & Prof#=WICKSONCRTR313,Reach-1         , 4
Up Type= 0
Dn Type= 3
Dn Slope=0.005
Boundary for River Rch & Prof#=WICKSONCRTR313,Reach-1         , 5
Up Type= 0
Dn Type= 3
Dn Slope=0.005
Boundary for River Rch & Prof#=WICKSONCRTR313,Reach-1         , 6
Up Type= 0
Dn Type= 3
Dn Slope=0.005
Boundary for River Rch & Prof#=WICKSONCRTR313,Reach-1         , 7
Up Type= 0
Dn Type= 3
Dn Slope=0.005
DSS Import GetInterval= 0
DSS Import GetPeak= 0
DSS Import FillOption= 0

--- WICKSONCREEKTRIB.g01 (geometry) ---

Geom Title=Existing Conditions
Program Version=4.10

River Reach=WICKSONCRTR313  ,Reach-1
Reach XY= 30
      3545434.06     10250320.37      3545728.33     10250401.97
      3545719.65     10250694.94      3545908.45     10250742.68
      3546644.57     10250327.27      3546542.99     10249964.25
      3547062.88     10250337.14       3547461.5     10250381.03
      3547636.71     10250231.86        3548322.     10250439.72
      3548428.75     10250066.24      3548884.29     10249997.19
       3549040.3     10250127.27      3549044.69     10250500.35
        3549278.     10250584.31       3549214.6     10250970.61
      3549530.63     10250954.98      3549811.39     10251172.35
      3549792.87     10251441.05      3550208.89     10251622.97
      3550272.29     10252101.05      3550911.94     10252201.85
      3551227.08      10252054.6      3551574.91     10252304.94
      3551366.11     10252666.91      3551680.29      10252716.3
      3551384.16     10253035.73      3551651.96     10253461.26
      3552036.81     10253629.15      3552122.11     10254251.64

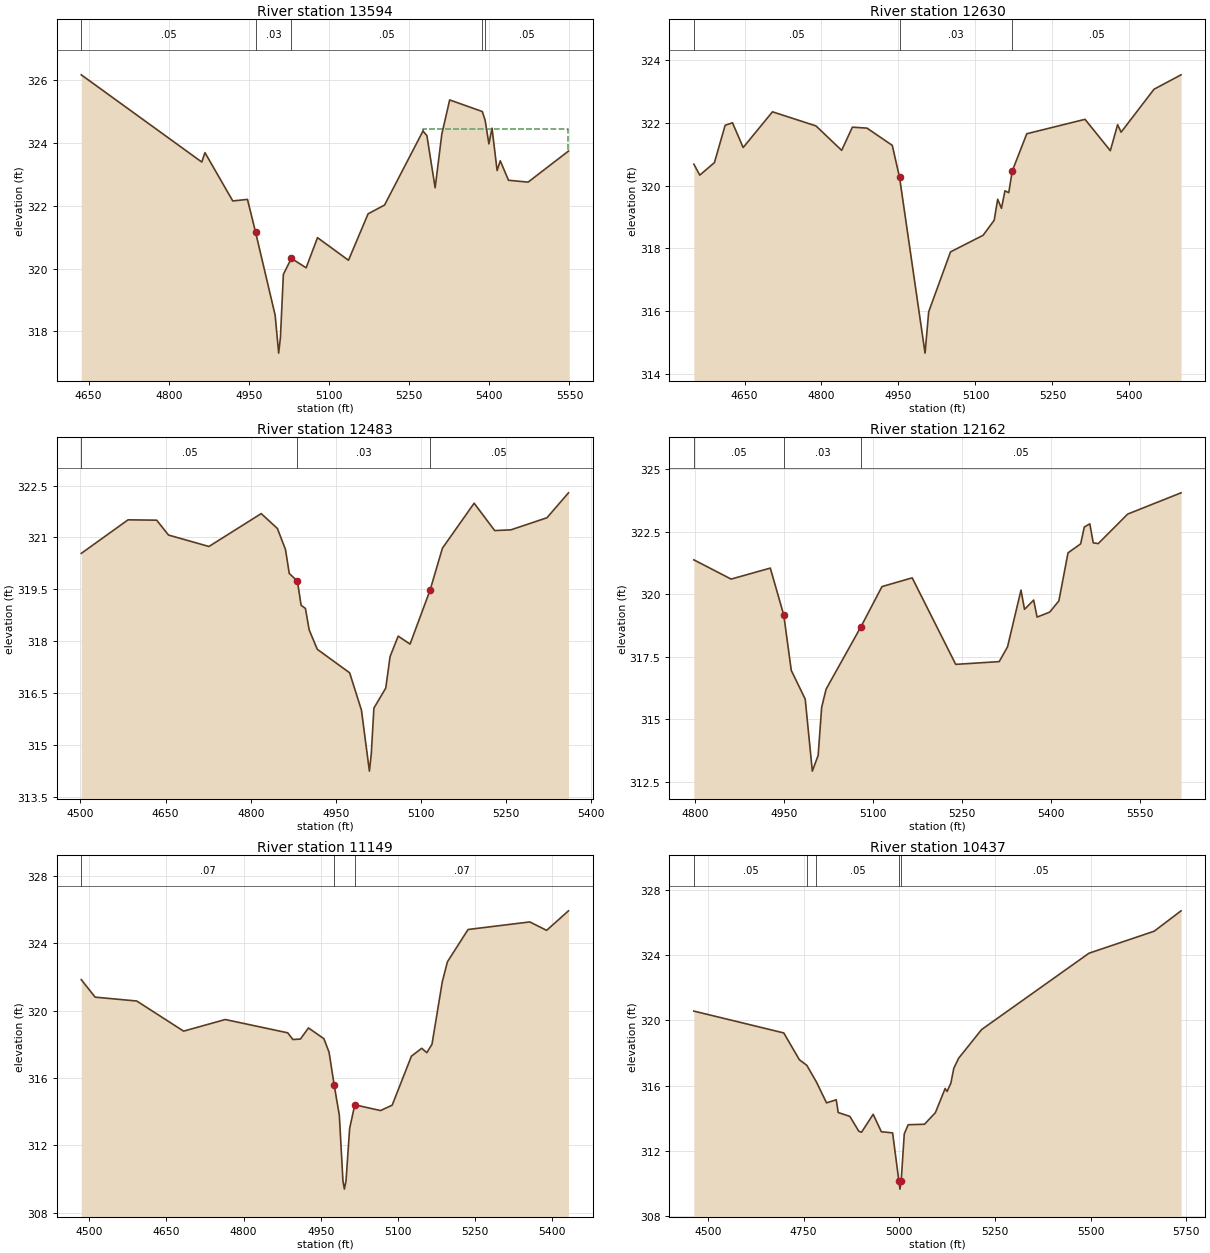
Type RM Length L Ch R = 1 ,13594   ,964,964,964
BEGIN DESCRIPTION:
UNT0497 IN WICK 14.0
END DESCRIPTION:
XS GIS Cut Line= 2
      3545137.06     10250586.12      3545914.08     10250108.63
#Sta/Elev= 30
  4636.2  326.18  4861.8   323.4  4867.7   323.7  4919.8  322.16  4947.3  322.21
  4962.4  321.17  4999.1  318.52  5005.7  317.31    5009  317.81  5014.5  319.82
  5029.4  320.33  5057.1  320.03  5078.4  320.99  5136.4  320.27  5173.1  321.75
  5203.9  322.03  5275.9  324.39  5283.2  324.24  5298.6  322.58  5311.1  324.29
  5325.8  325.38  5386.9  325.01  5392.2  324.73  5399.2  323.98  5405.1  324.48
  5414.6  323.13  5420.5  323.44  5435.9  322.82  5472.6  322.76  5548.2  323.75
#Mann= 5 ,-1 , 0
  4636.2     .05       0  4962.4     .03       0  5029.4     .05       0
  5386.9      .1       0  5392.2     .05       0
#XS Ineff= 2 , 0
                         5276.43          324.44
Permanent Ineff=
       F       F
Bank Sta=4962.4,5029.4
XS Rating Curve= 0 ,0
Exp/Cntr=0.3,0.1

Type RM Length L Ch R = 1 ,12630   ,147,147,147
BEGIN DESCRIPTION:
UNT0497 IN WICK 13.0
END DESCRIPTION:
XS GIS Cut Line= 3
       3546353.1     10250966.68      3546182.62     10250819.38
      3545693.91     10250285.21
#Sta/Elev= 30
  4551.3  320.69  4562.9  320.34  4591.4  320.74  4612.3  321.93  4626.6  322.01
  4647.4  321.22  4704.5  322.36  4789.3  321.91  4839.3  321.13  4860.2  321.87
  4888.6  321.84  4937.9  321.29  4952.1  320.27  5001.8  314.66  5008.9  315.98
  5051.4  317.89  5114.9  318.42  5136.5   318.9  5143.3  319.57  5150.7  319.28
  5157.5  319.84  5164.9  319.78  5171.7  320.47    5200  321.66  5313.5  322.12
  5362.8  321.12    5377  321.95  5383.8  321.71  5447.9  323.08  5500.6  323.54
#Mann= 3 , 0 , 0
  4551.3     .05       0  4952.1     .03       0  5171.7     .05       0
Bank Sta=4952.1,5171.7
XS Rating Curve= 0 ,0
Exp/Cntr=0.3,0.1

Type RM Length L Ch R = 1 ,12483   ,321,321,321
BEGIN DESCRIPTION:
UNT0497 IN WICK 12.0
END DESCRIPTION:
XS GIS Cut Line= 2
      3546476.77     10250943.87      3545914.79     10250295.13
#Sta/Elev= 30
  4501.5  320.54  4583.9  321.51  4634.3   321.5  4655.2  321.07  4726.4  320.74
  4818.5  321.69    4847  321.26  4861.3  320.65  4867.9  319.96  4882.2  319.74
  4888.8  319.04  4896.4  318.95    4903  318.33  4917.3  317.77  4974.3  317.09
  4995.1  316.01  5009.1  314.25  5012.4  314.75    5017  316.07  5037.9  316.65
  5045.5  317.56  5059.8  318.15  5080.7  317.92  5115.8  319.47  5137.7  320.69
  5193.6  321.99  5229.8   321.2  5258.3  321.22  5321.9  321.57  5359.8  322.29
#Mann= 3 , 0 , 0
  4501.5     .05       0  4882.2     .03       0  5115.8     .05       0
Bank Sta=4882.2,5115.8
XS Rating Curve= 0 ,0
Exp/Cntr=0.3,0.1

Type RM Length L Ch R = 1 ,12162   ,1013,1013,1013
BEGIN DESCRIPTION:
Mapping XS 0eb4c429
END DESCRIPTION:
XS GIS Cut Line= 2
      3546549.34     10250661.23      3546118.11     10249962.95
#Sta/Elev= 30
  4798.1  321.37  4860.9   320.6  4926.9  321.04  4949.6  319.16  4962.2  316.95
  4985.7   315.8  4997.7  312.92  5007.5  313.55  5013.4  315.47  5020.9   316.2
  5079.7   318.7    5115   320.3  5165.9  320.65  5239.2  317.19  5312.5   317.3
  5326.5  317.89  5349.2  320.16  5355.1  319.39  5370.5  319.76  5376.3  319.08
  5397.6  319.28    5413  319.73  5428.4  321.65  5449.7  322.01  5455.8  322.68
  5465.1  322.81  5470.9  322.05  5479.3  322.02  5528.9   323.2  5618.8  324.05
#Mann= 3 , 0 , 0
  4798.1     .05       0  4949.6     .03       0  5079.7     .05       0
Bank Sta=4949.6,5079.7
XS Rating Curve= 0 ,0
Exp/Cntr=0.3,0.1

Type RM Length L Ch R = 1 ,11149   ,712,712,712
BEGIN DESCRIPTION:
Mapping XS 2cc66d0d
END DESCRIPTION:
XS GIS Cut Line= 3
      3546677.86     10250638.22      3546742.96      10250217.2
      3546725.61     10249696.52
#Sta/Elev= 30
  4484.6  321.84  4511.5   320.8  4592.4  320.57  4683.5  318.78  4764.5  319.47
  4885.9  318.68    4896  318.28  4910.6  318.31  4926.2  318.97  4956.2  318.33
  4966.2  317.53  4976.2  315.57  4986.2  313.78  4993.2  309.89    4996  309.39
  4999.2  309.89  5006.2  312.99  5016.2   314.4  5066.3  314.06  5088.9  314.38
  5126.3  317.29  5146.3  317.76  5156.3   317.5  5166.3     318  5186.3  321.71
  5196.3   322.9  5236.4  324.82  5356.4  325.27  5389.1  324.77  5431.6  325.93
#Mann= 3 , 0 , 0
  4484.6     .07       0  4976.2     .05       0  5016.2     .07       0
Bank Sta=4976.2,5016.2
XS Rating Curve= 0 ,0
Exp/Cntr=0.3,0.1

Type RM Length L Ch R = 1 ,10437   ,772,772,772
BEGIN DESCRIPTION:
UNT0497 IN WICK 11.0
END DESCRIPTION:
XS GIS Cut Line= 3
      3547211.72     10250803.09      3547331.46     10250131.96
       3547292.1      10249541.6
#Sta/Elev= 30
  4463.2  320.57  4698.3  319.23  4738.9  317.59  4758.6  317.24  4783.6  316.22
    4810  314.94  4835.4  315.13  4840.5  314.35    4871  314.11  4894.4   313.2
  4901.5  313.14  4931.9  314.24  4953.3  313.17  4982.7   313.1  4999.1  310.15
  5001.9  309.65  5005.1  310.15  5013.2  313.04  5023.4   313.6  5066.1  313.63
  5094.5  314.34    5120  315.82  5125.1  315.64  5135.1  316.16  5142.6  317.06
  5155.3  317.68  5215.4  319.44    5496  324.12  5666.4  325.47  5736.6  326.72
#Mann= 5 ,-1 , 0
  4463.2     .05       0  4758.6      .1       0  4783.6     .05       0
  4999.1     .03       0  5005.1     .05       0
Bank Sta=4999.1,5005.1
XS Rating Curve= 0 ,0
Exp/Cntr=0.3,0.1

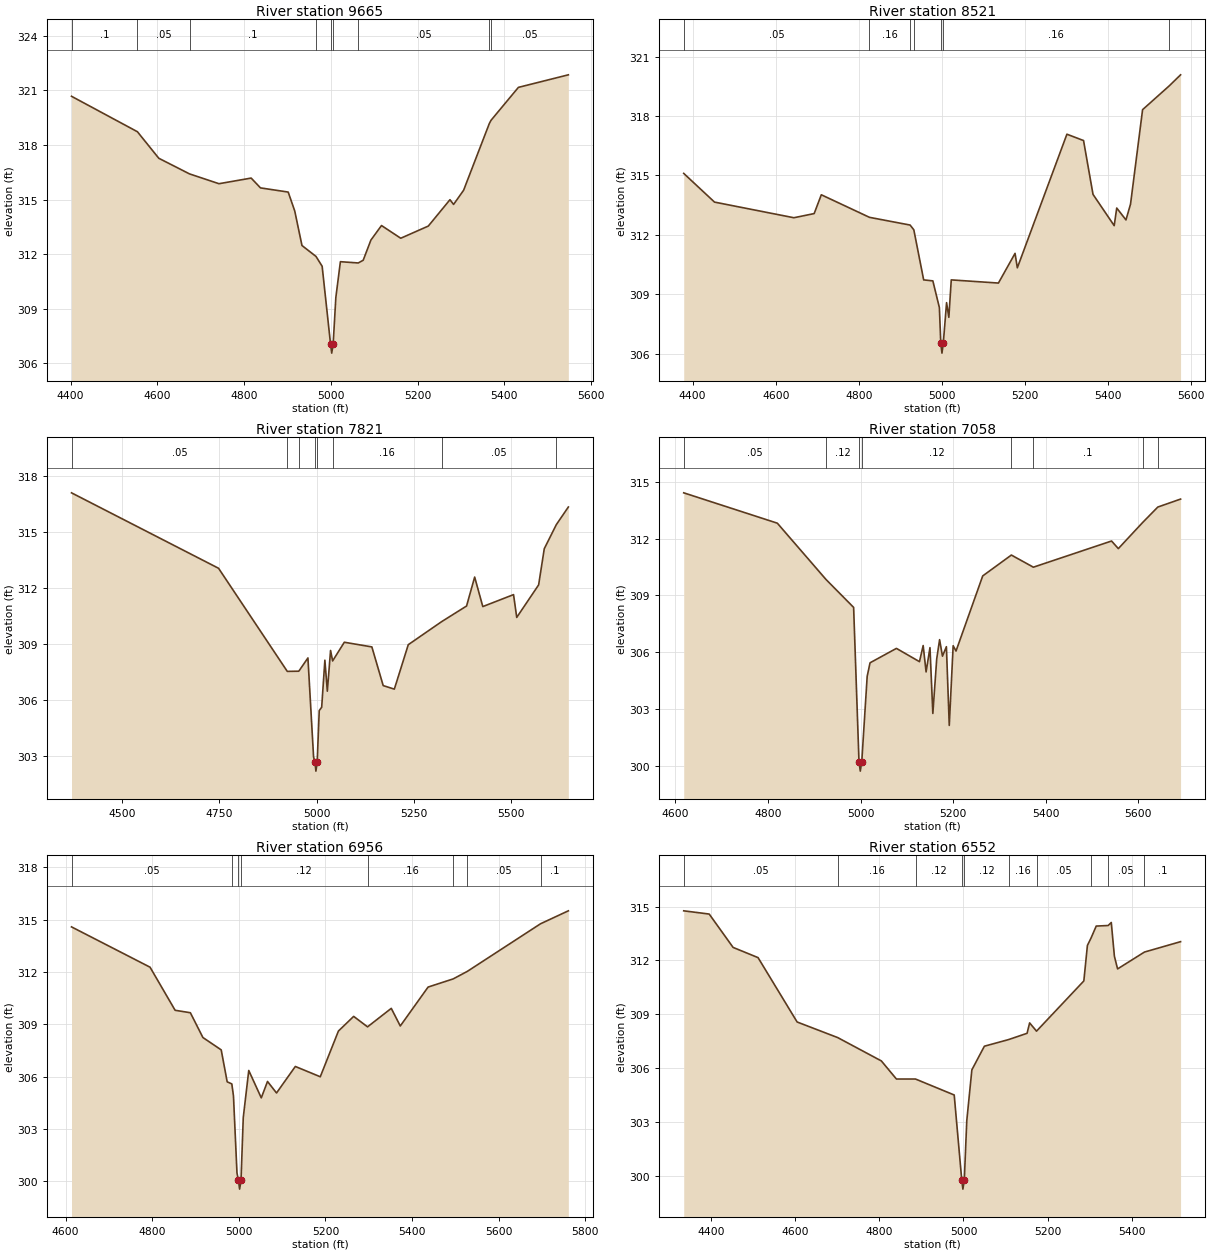
Type RM Length L Ch R = 1 ,9665    ,1144,1144,1144
BEGIN DESCRIPTION:
Mapping XS d219a644
END DESCRIPTION:
XS GIS Cut Line= 3
      3547519.85     10250716.34      3547897.48     10250494.97
      3548118.85     10249822.19
#Sta/Elev= 30
  4401.9  320.68  4553.9  318.73  4603.2  317.27  4674.1  316.41    4742  315.87
  4816.3  316.18  4837.8  315.64  4901.7  315.41  4916.8  314.37  4933.5  312.47
  4965.8  311.87    4980  311.33  4999.4  307.05  5002.1  306.55  5005.4  307.05
  5011.6  309.61  5022.1  311.58  5063.3  311.51  5074.7  311.66  5092.5  312.77
  5116.9  313.57  5161.3  312.87  5224.9  313.54  5274.8  314.99  5283.2  314.73
  5306.3  315.51  5365.6  319.18  5369.6  319.36  5432.7  321.17  5547.9  321.86
#Mann= 9 ,-1 , 0
  4401.9      .1       0  4553.9     .05       0  4674.1      .1       0
  4965.8     .05       0  4999.4     .07       0  5005.4     .05       0
  5063.3     .05       0  5365.6      .1       0  5369.6     .05       0
Bank Sta=4999.4,5005.4
XS Rating Curve= 0 ,0
Exp/Cntr=0.3,0.1

Type RM Length L Ch R = 1 ,8521    ,700,700,700
BEGIN DESCRIPTION:
Mapping XS adf4075f
END DESCRIPTION:
XS GIS Cut Line= 3
      3548345.77     10250569.19      3548547.12     10250333.11
      3548925.59     10249532.77
#Sta/Elev= 30
  4378.6   315.1  4452.7  313.65  4643.7  312.86  4692.5  313.07  4709.7  314.02
  4825.6  312.88  4923.4  312.49  4932.3  312.25    4956  309.72  4978.1  309.67
  4993.8  308.32  4997.2  306.52    5000  306.02  5003.2  306.52  5011.1  308.57
  5016.6  307.83  5022.4  309.72  5135.9  309.56  5175.9  311.06  5181.4  310.33
  5300.7  317.08  5340.7  316.76  5363.5  314.04  5414.5  312.46  5420.6  313.35
  5442.8  312.75  5453.8  313.55  5482.8  318.32  5546.8  319.52  5574.2  320.08
#Mann= 7 ,-1 , 0
  4378.6     .05       0  4825.6     .16       0  4923.4     .05       0
  4932.3     .16       0  4997.2     .07       0  5003.2     .16       0
  5546.8     .05       0
Bank Sta=4997.2,5003.2
XS Rating Curve= 0 ,0
Exp/Cntr=0.3,0.1

Type RM Length L Ch R = 1 ,7821    ,763,763,763
BEGIN DESCRIPTION:
UNT0497 IN WICK 10.0
END DESCRIPTION:
XS GIS Cut Line= 3
       3548431.3      10250668.6      3548904.42     10250460.25
      3549507.11     10249999.84
#Sta/Elev= 30
  4370.8  317.09  4748.3  313.05  4924.7  307.53  4954.3  307.54  4977.7  308.25
  4992.2  302.95  4995.5  302.69  4998.2  302.19  5001.5  302.69  5006.7  305.43
    5013  305.61  5021.2  308.13  5027.5  306.47  5035.8  308.65  5041.1  308.09
  5071.1  309.09  5141.8  308.84  5170.9  306.77  5199.5  306.58  5235.3  308.96
  5320.7  310.19  5384.9  311.03  5405.7  312.58  5426.6     311  5505.5  311.64
  5513.7  310.42  5569.9  312.16  5584.4   314.1  5615.4  315.39  5646.2  316.33
#Mann= 8 ,-1 , 0
  4370.8     .05       0  4924.7     .16       0  4954.3     .12       0
  4995.5     .07       0  5001.5     .12       0  5041.1     .16       0
  5320.7     .05       0  5615.4      .1       0
Bank Sta=4995.5,5001.5
XS Rating Curve= 0 ,0
Exp/Cntr=0.3,0.1

Type RM Length L Ch R = 1 ,7058    ,102,102,102
BEGIN DESCRIPTION:
Mapping XS c7c9b88b
END DESCRIPTION:
XS GIS Cut Line= 2
      3548852.32     10251085.26      3549716.03     10250447.25
#Sta/Elev= 30
  4617.8  314.41  4820.1  312.81  4925.4  309.84    4985  308.37  4996.6  300.24
  4999.4  299.74  5002.6  300.24  5014.3  304.74  5020.5  305.45  5077.5  306.21
  5127.3  305.51  5135.3  306.36  5141.6  304.97    5150  306.25  5156.2  302.78
  5164.6  305.66  5170.8  306.67    5177   305.8  5185.5   306.3  5191.7  302.15
  5200.1  306.35  5206.3  306.07    5264  310.03  5325.9  311.13  5373.5  310.49
  5542.4  311.87  5557.1  311.47  5609.4  312.84  5642.4  313.66  5691.6  314.08
#Mann= 8 ,-1 , 0
  4617.8     .05       0  4925.4     .12       0  4996.6     .07       0
  5002.6     .12       0  5325.9     .16       0  5373.5      .1       0
  5609.4     .05       0  5642.4      .1       0
Bank Sta=4996.6,5002.6
XS Rating Curve= 0 ,0
Exp/Cntr=0.3,0.1

Type RM Length L Ch R = 1 ,6956    ,404,404,404
BEGIN DESCRIPTION:
Mapping XS 643170bb
END DESCRIPTION:
XS GIS Cut Line= 2
      3548900.05      10251185.1      3549802.86     10250477.61
#Sta/Elev= 30
  4613.8  314.59  4795.1  312.28    4853  309.81  4888.2  309.67  4917.1  308.25
  4959.4  307.54  4973.2  305.71  4983.9  305.59  4987.7   304.9  4995.8  300.49
  4999.1  300.06  5001.9  299.56  5005.1  300.06  5010.3  303.66    5023  306.36
  5051.9  304.79  5066.3  305.73  5087.1  305.07  5130.5  306.59  5188.1     306
    5230  308.62  5265.2  309.46  5297.2  308.86    5352  309.92  5372.8  308.91
    5437  311.14  5495.1  311.61  5527.6  312.04  5696.7  314.77  5760.8  315.51
#Mann= 8 ,-1 , 0
  4613.8     .05       0  4983.9     .12       0  4999.1     .07       0
  5005.1     .12       0  5297.2     .16       0  5495.1      .1       0
  5527.6     .05       0  5696.7      .1       0
Bank Sta=4999.1,5005.1
XS Rating Curve= 0 ,0
Exp/Cntr=0.3,0.1

Type RM Length L Ch R = 1 ,6552    ,617,617,617
BEGIN DESCRIPTION:
UNT0497 IN WICK 9.0
END DESCRIPTION:
XS GIS Cut Line= 2
      3548996.02     10251340.15      3549972.17      10250672.9
#Sta/Elev= 30
  4334.2  314.77  4394.8  314.59  4451.7  312.73  4511.1  312.16  4604.1  308.57
  4700.7   307.7  4804.5   306.4  4840.4  305.39  4885.8  305.39  4977.9   304.5
  4995.9  299.75  4998.6  299.25  5001.9  299.75  5007.8  303.06  5019.9   305.9
  5049.7  307.22  5107.4  307.59  5151.3  307.94  5157.4  308.52  5173.8  308.06
  5286.4  310.86  5294.9  312.84  5303.3  313.24  5315.9  313.92  5344.3  313.95
  5351.7  314.12  5359.1  312.24  5366.7  311.53  5430.6  312.47  5516.6  313.05
#Mann= 10 ,-1 , 0
  4334.2     .05       0  4700.7     .16       0  4885.8     .12       0
  4995.9     .07       0  5001.9     .12       0  5107.4     .16       0
  5173.8     .05       0  5303.3      .1       0  5344.3     .05       0
  5430.6      .1       0
Bank Sta=4995.9,5001.9
XS Rating Curve= 0 ,0
Exp/Cntr=0.3,0.1

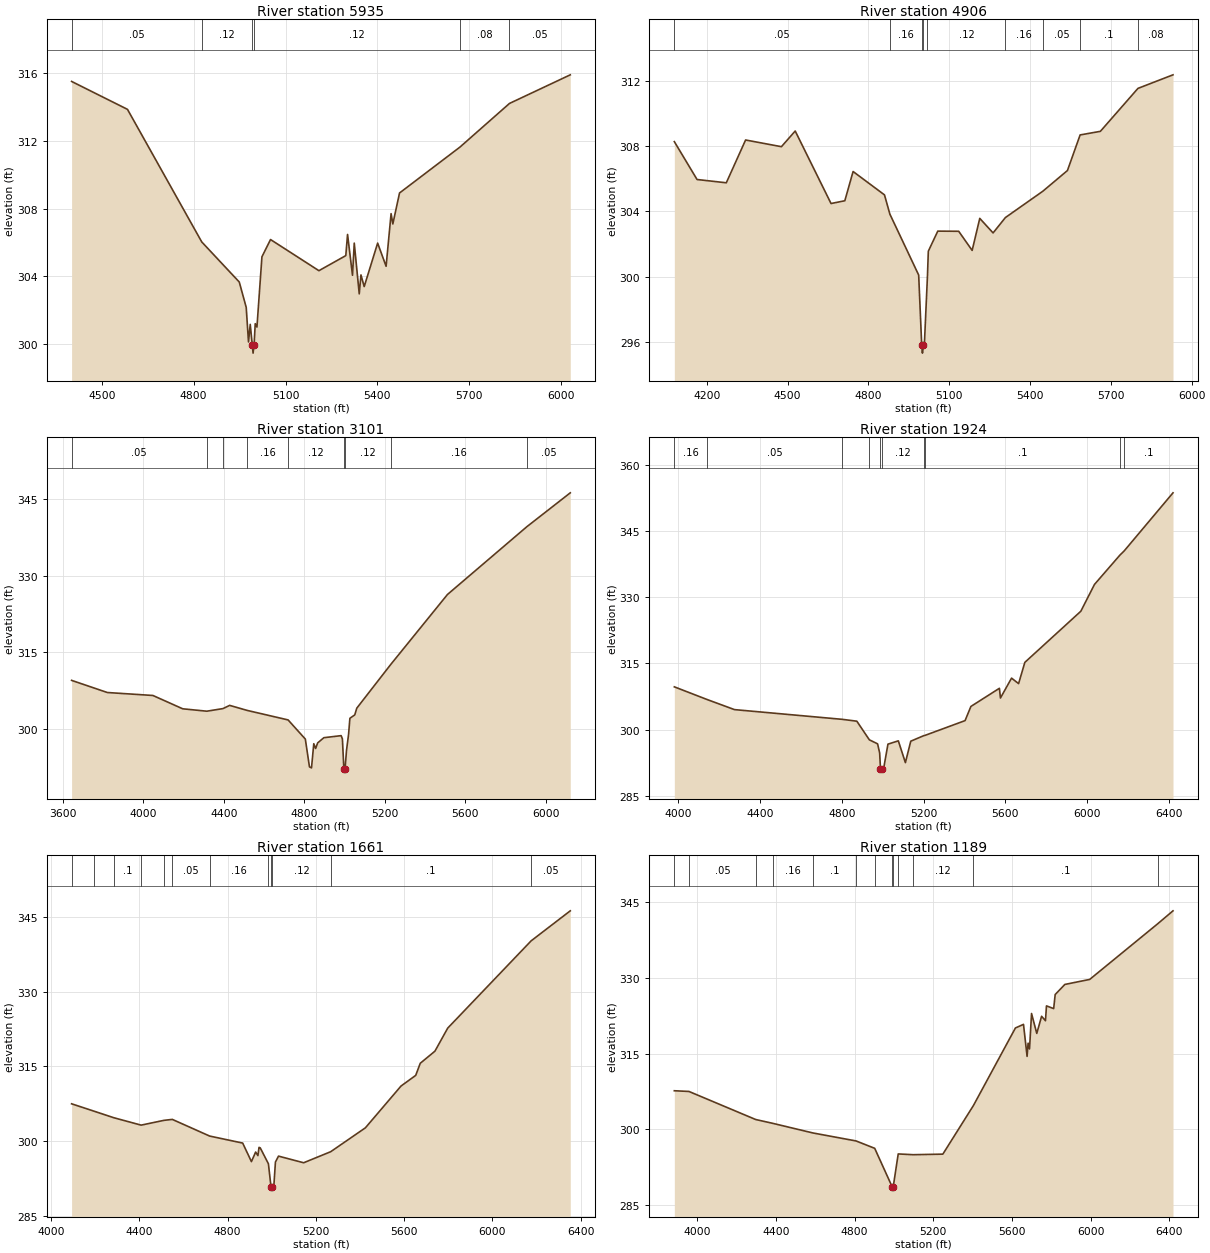
Type RM Length L Ch R = 1 ,5935    ,1029,1029,1029
BEGIN DESCRIPTION:
UNT0497 IN WICK 8.0
END DESCRIPTION:
XS GIS Cut Line= 4
      3549238.58     10251580.05      3549572.82     10251497.58
      3550505.98     10250998.45      3550583.94     10250786.25
#Sta/Elev= 30
  4401.4  315.51  4583.9  313.86  4826.4  306.03    4949  303.66  4971.7  302.16
  4979.1  300.12  4984.8  301.16  4991.4  299.96  4994.1  299.46  4997.4  299.96
  5001.1   301.2  5006.7     301    5023  305.15  5051.1  306.17  5209.1  304.33
  5296.9  305.22  5302.6  306.47  5318.8  304.06  5324.5  305.96  5340.8  302.96
  5346.4  304.08    5357  303.39  5400.9  305.96  5428.5  304.59  5444.8   307.7
  5450.5  307.09  5472.4  308.92  5669.6  311.63  5831.5  314.21    6030   315.9
#Mann= 6 ,-1 , 0
  4401.4     .05       0  4826.4     .12       0  4991.4     .07       0
  4997.4     .12       0  5669.6     .08       0  5831.5     .05       0
Bank Sta=4991.4,4997.4
XS Rating Curve= 0 ,0
Exp/Cntr=0.3,0.1

Type RM Length L Ch R = 1 ,4906    ,1805,1805,1805
BEGIN DESCRIPTION:
UNT0497 IN WICK 6.0
END DESCRIPTION:
XS GIS Cut Line= 4
      3549403.53     10252374.32      3550063.28     10252231.08
      3550696.96     10251645.15      3550718.66     10251332.68
#Sta/Elev= 30
  4079.4  308.26  4163.8  305.94  4272.4  305.74    4344  308.36    4477  307.95
  4528.2  308.91  4661.2  304.47  4712.4  304.64  4743.1  306.43  4859.6     305
  4879.7  303.82  4986.6  300.09  4997.8  295.81  5000.6  295.31  5003.8  295.81
  5008.2  296.01  5019.3  300.08  5022.4  301.55  5057.5  302.78  5135.2  302.77
  5185.1   301.6  5213.4  303.56  5262.8  302.67  5308.5  303.61  5447.3  305.22
  5538.9  306.49    5586  308.67  5661.2  308.89  5800.7  311.52  5930.8  312.35
#Mann= 9 ,-1 , 0
  4079.4     .05       0  4879.7     .16       0  4997.8     .07       0
  5003.8     .16       0  5019.3     .12       0  5308.5     .16       0
  5447.3     .05       0    5586      .1       0  5800.7     .08       0
Bank Sta=4997.8,5003.8
XS Rating Curve= 0 ,0
Exp/Cntr=0.3,0.1

Type RM Length L Ch R = 1 ,3101    ,1177,1177,1177
BEGIN DESCRIPTION:
UNT0497 IN WICK 5.0
END DESCRIPTION:
XS GIS Cut Line= 3
      3550267.25     10252725.88      3552190.01     10252300.53
      3552684.81     10252174.66
#Sta/Elev= 30
  3642.8  309.53  3820.6  307.15  4047.2  306.57  4195.3  303.96  4315.3  303.49
  4395.4     304  4428.8  304.63  4515.3  303.65  4719.4  301.78  4805.1  298.03
  4825.6  292.59  4835.8  292.38  4847.1  297.12  4856.3  296.19  4866.5  297.28
  4897.3   298.3  4983.1   298.7  4989.4  298.07  4996.7  292.25  4999.4  291.75
  5002.7  292.25  5009.9  295.81  5020.2  298.98  5026.7   302.1  5050.9  302.77
  5061.1  304.09  5229.5  312.63  5511.8  326.35  5906.6  339.63  6122.6  346.27
#Mann= 9 ,-1 , 0
  3642.8     .05       0  4315.3     .16       0  4395.4     .05       0
  4515.3     .16       0  4719.4     .12       0  4996.7     .07       0
  5002.7     .12       0  5229.5     .16       0  5906.6     .05       0
Bank Sta=4996.7,5002.7
XS Rating Curve= 0 ,0
Exp/Cntr=0.3,0.1

Type RM Length L Ch R = 1 ,1924    ,263,263,263
BEGIN DESCRIPTION:
UNT0497 IN WICK 3.0
END DESCRIPTION:
XS GIS Cut Line= 3
      3550392.06     10253091.65      3552529.64      10252717.2
      3552778.13     10252609.15
#Sta/Elev= 30
  3979.9  309.71  4137.9  306.88  4274.4  304.55  4801.8  302.35  4873.3  301.93
  4934.6  297.71  4974.9   296.8    4985  294.75  4989.1  291.12  4991.9  290.62
  4995.1  291.12  5005.3  291.42  5025.6  296.73  5076.4  297.48    5111  292.55
  5137.3   297.4  5202.5  298.68  5205.6  298.69  5403.1  302.06  5431.7  305.27
  5571.2  309.38  5576.3  307.18  5630.7  311.68  5665.2  310.44  5695.7  315.25
  5969.8  326.83  6036.6   332.9  6160.9  339.53  6181.8  340.48    6421  353.65
#Mann= 10 ,-1 , 0
  3979.9     .16       0  4137.9     .05       0  4801.8     .16       0
  4934.6     .12       0  4989.1     .07       0  4995.1     .12       0
  5202.5     .16       0  5205.6      .1       0  6160.9     .16       0
  6181.8      .1       0
Bank Sta=4989.1,4995.1
XS Rating Curve= 0 ,0
Exp/Cntr=0.3,0.1

Type RM Length L Ch R = 1 ,1661    ,472,472,472
BEGIN DESCRIPTION:
Mapping XS 1857d614
END DESCRIPTION:
XS GIS Cut Line= 2
      3550587.08     10253390.66      3552768.21     10252794.62
#Sta/Elev= 30
  4092.4  307.47  4192.1  306.02  4282.7  304.69  4407.7  303.19  4511.2  304.15
  4549.1  304.34  4718.2     301  4868.1  299.59  4907.8  295.87  4926.9  297.79
  4937.2  297.08  4942.3  298.73  4947.7  298.63  4984.8  295.44  4996.5  290.85
  4999.3  290.35  5002.5  290.85  5009.9  291.28  5016.6  295.78  5030.6  296.97
  5144.6  295.64  5267.3  297.86  5424.5  302.65  5586.2  311.04  5652.6  313.17
  5673.3   315.6  5739.8  318.03  5797.7  322.65  6175.9  340.16  6353.5  346.19
#Mann= 12 ,-1 , 0
  4092.4     .16       0  4192.1     .05       0  4282.7      .1       0
  4407.7     .05       0  4511.2      .1       0  4549.1     .05       0
  4718.2     .16       0  4984.8     .12       0  4996.5     .07       0
  5002.5     .12       0  5267.3      .1       0  6175.9     .05       0
Bank Sta=4996.5,5002.5
XS Rating Curve= 0 ,0
Exp/Cntr=0.3,0.1

Type RM Length L Ch R = 1 ,1189    ,0,0,0
BEGIN DESCRIPTION:
UNT0497 IN WICK 1.0
END DESCRIPTION:
XS GIS Cut Line= 3
      3550587.37     10253715.46        3552649.     10253270.58
      3552790.05     10252869.12
#Sta/Elev= 30
  3883.6  307.64  3957.9   307.5  4297.1  301.95  4384.3  301.19  4588.1  299.29
  4807.4  297.71  4902.1  296.25  4990.3  288.68  4993.1  288.18  4996.3  288.68
  5021.6  295.14  5097.5  294.99  5248.4   295.1  5403.7  304.71  5617.3  320.06
  5658.3  320.77  5676.6  314.44  5681.7  317.05    5689  315.91  5699.2  322.92
  5725.8  318.98  5750.3  322.37    5770  321.49  5775.1  324.43  5811.7  323.89
  5819.3  326.67  5868.6  328.67  5994.8  329.66  6340.5  340.67  6418.2  343.23
#Mann= 13 ,-1 , 0
  3883.6     .16       0  3957.9     .05       0  4297.1      .1       0
  4384.3     .16       0  4588.1      .1       0  4807.4     .16       0
  4902.1      .1       0  4990.3     .07       0  4996.3      .1       0
  5021.6      .1       0  5097.5     .12       0  5403.7      .1       0
  6340.5     .05       0
Bank Sta=4990.3,4996.3
XS Rating Curve= 0 ,0
Exp/Cntr=0.3,0.1

Chan Stop Cuts=-1
Use User Specified Reach Order=0
Composite Channel Slope=5