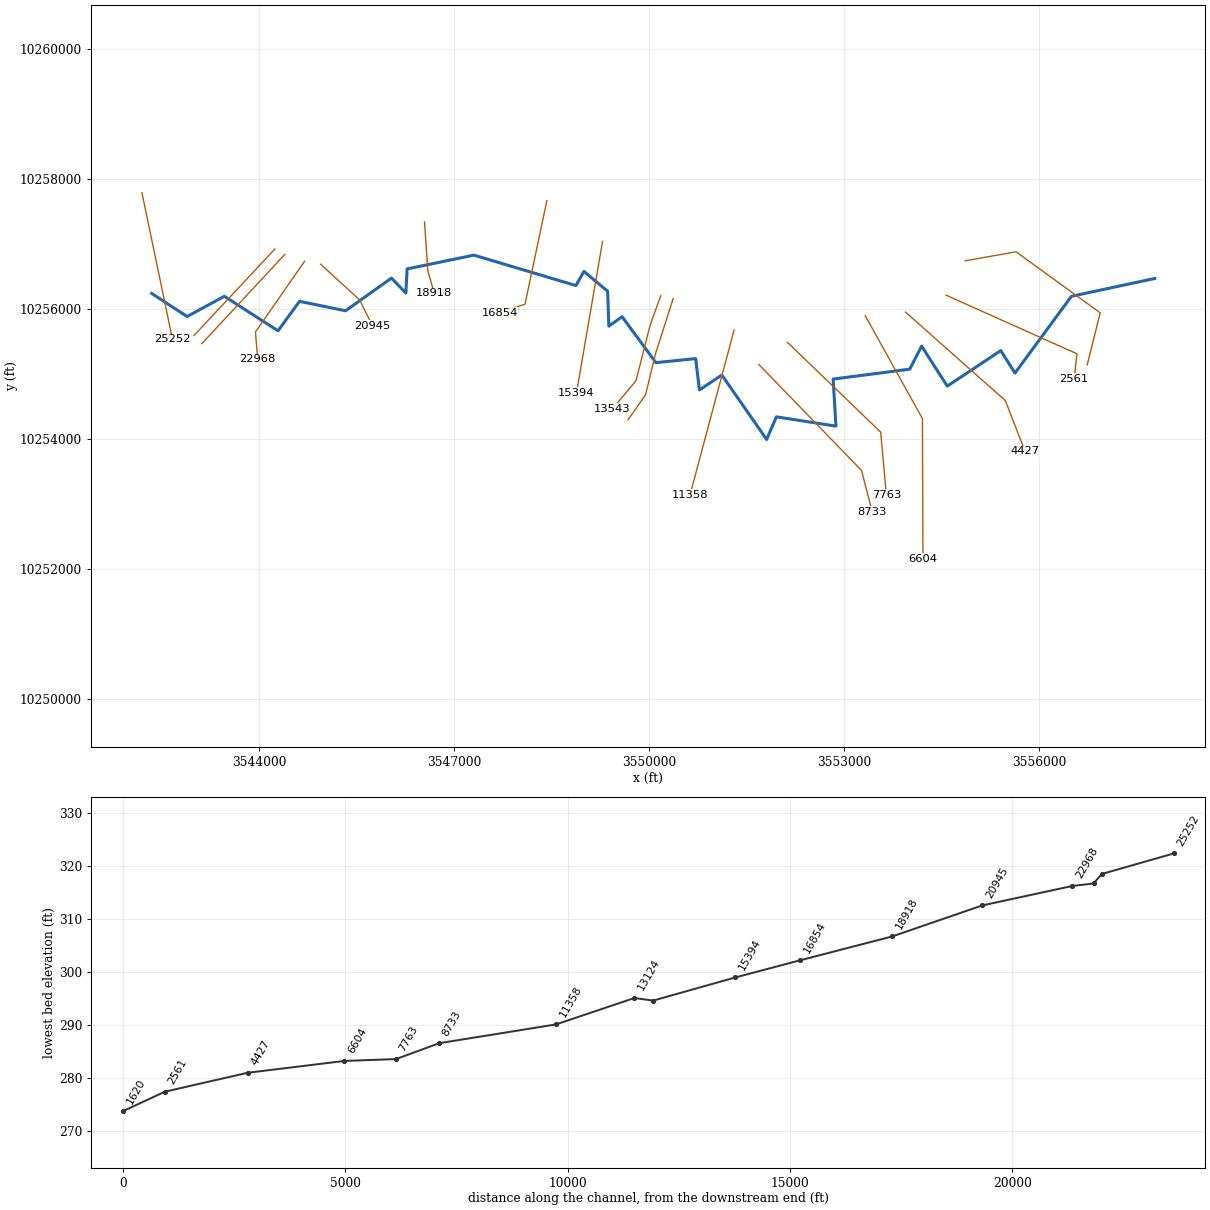
--- WICKSONCREEKTRIB.prj (project) ---

Proj Title=WICKSON CREEK TRIB 31
Current Plan=p01
Default Exp/Contr=0.3,0.1
English Units
Geom File=g01
Flow File=f01
Plan File=p01
Y Axis Title=Elevation
X Axis Title(PF)=Main Channel Distance
X Axis Title(XS)=Station
BEGIN DESCRIPTION:
LITTLE WICKSON CREEK
END DESCRIPTION:
DSS Export Rating Curves= 0
DSS Export Rating Curve Sorted= 0
DSS Export Volume Flow Curves= 0
DXF OffsetX= 0
DXF OffsetY= 0
DXF ScaleX= 1
DXF ScaleY= 10

--- WICKSONCREEKTRIB.p01 (plan) ---

Plan Title=Multiple Run
Short Identifier=Multiple
Geom File=g01
Flow File=f01
Subcritical Flow
K Sum by GR= 0
Std Step Tol= 0.01
Critical Tol= 0.01
Num of Std Step Trials= 20
Max Error Tol= 0.3
Flow Tol Ratio= 0.001
Split Flow NTrial= 30
Split Flow Tol= 0.02
Split Flow Ratio= 0.02
Log Output Level= 0
Friction Slope Method= 1
Unsteady Friction Slope Method= 2
Unsteady Bridges Friction Slope Method= 1
Parabolic Critical Depth
Global Vel Dist=  1 , 1 , 1
Global Log Level= 0
CheckData=True
Encroach Param= -1, 0, 0, 0
BEGIN DESCRIPTION:
Multiple Run
END DESCRIPTION:

--- WICKSONCREEKTRIB.f01 (steady flow) ---

Flow Title=Multiple
Program Version=4.10
Number of Profiles= 7
Profile Names=10-year,25-year,50-year,1pct_min,100-year,1pct_plu,500-year
River Rch & RM=LITTLE WICKSON C,Reach-1         ,25252
     827    1129    1378    1229    1662    2248    2427
River Rch & RM=LITTLE WICKSON C,Reach-1         ,15394
     967    1328    1625    1453    1965    2658    2885
River Rch & RM=LITTLE WICKSON C,Reach-1         ,8733
    1642    2303    2860    2592    3505    4740    5280
River Rch & RM=LITTLE WICKSON C,Reach-1         ,4427
    1733    2436    3030    2748    3716    5026    5611
River Rch & RM=WICKSONCRTRB31,Reach-1         ,25252
     827    1129    1378    1229    1662    2248    2427
River Rch & RM=WICKSONCRTRB31,Reach-1         ,15394
     967    1328    1625    1453    1965    2658    2885
River Rch & RM=WICKSONCRTRB31,Reach-1         ,8733
    1642    2303    2860    2592    3505    4740    5280
River Rch & RM=WICKSONCRTRB31,Reach-1         ,4427
    1733    2436    3030    2748    3716    5026    5611
Boundary for River Rch & Prof#=WICKSONCRTRB31,Reach-1         , 1
Up Type= 0
Dn Type= 3
Dn Slope=0.005
Boundary for River Rch & Prof#=WICKSONCRTRB31,Reach-1         , 2
Up Type= 0
Dn Type= 3
Dn Slope=0.005
Boundary for River Rch & Prof#=WICKSONCRTRB31,Reach-1         , 3
Up Type= 0
Dn Type= 3
Dn Slope=0.005
Boundary for River Rch & Prof#=WICKSONCRTRB31,Reach-1         , 4
Up Type= 0
Dn Type= 3
Dn Slope=0.005
Boundary for River Rch & Prof#=WICKSONCRTRB31,Reach-1         , 5
Up Type= 0
Dn Type= 3
Dn Slope=0.005
Boundary for River Rch & Prof#=WICKSONCRTRB31,Reach-1         , 6
Up Type= 0
Dn Type= 3
Dn Slope=0.005
Boundary for River Rch & Prof#=WICKSONCRTRB31,Reach-1         , 7
Up Type= 0
Dn Type= 3
Dn Slope=0.005
DSS Import GetInterval= 0
DSS Import GetPeak= 0
DSS Import FillOption= 0

--- WICKSONCREEKTRIB.g01 (geometry) ---

Geom Title=Existing Conditions
Program Version=4.10

River Reach=WICKSONCRTRB31  ,Reach-1
Reach XY= 30
      3542342.06      10256241.8      3542887.02     10255885.75
      3543461.02     10256197.14      3544286.79     10255665.37
      3544617.45     10256119.46      3545326.27     10255973.93
      3546033.28     10256477.24      3546255.14     10256245.65
       3546273.3     10256618.26      3547302.35     10256830.83
      3548871.67      10256362.3      3548995.99     10256580.21
      3549360.05     10256274.79       3549379.4     10255736.53
       3549582.3     10255883.02      3550103.43     10255174.98
      3550715.29     10255237.33      3550773.54     10254755.21
      3551118.45     10254984.26      3551807.46     10253992.27
      3551957.95     10254340.39       3552874.8       10254197.
      3552831.68     10254922.02      3554010.86     10255074.61
      3554193.28     10255429.18      3554587.87     10254813.43
      3555412.08      10255360.7      3555630.51     10255014.74
      3556499.43     10256196.75      3557782.11     10256471.64

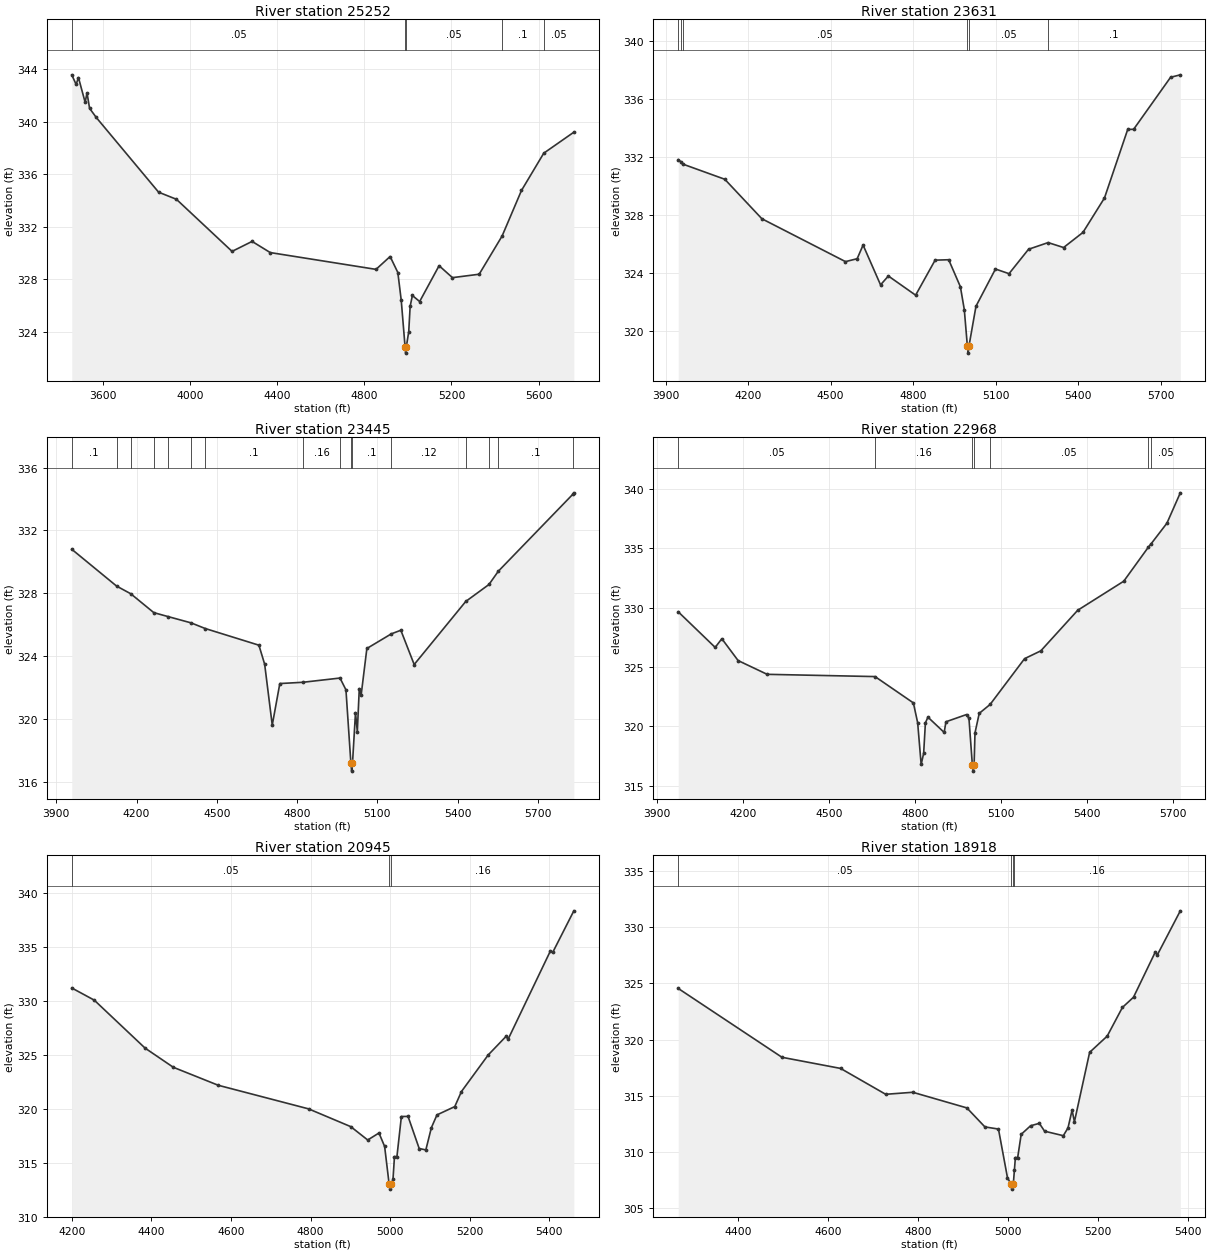
Type RM Length L Ch R = 1 ,25252   ,1621,1621,1621
BEGIN DESCRIPTION:
LITTLE WICKSON CREEK 32.0
END DESCRIPTION:
XS GIS Cut Line= 2
       3542192.1     10257791.66      3542661.87     10255536.37
#Sta/Elev= 30
  3458.2  343.56  3478.1  342.83  3488.9  343.35  3519.5  341.47  3528.2  342.18
  3539.9  341.01  3570.6  340.31  3856.6  334.62  3938.3  334.08  4193.7  330.11
  4285.6  330.87  4368.9  330.02  4854.2  328.74  4918.9  329.72  4954.3   328.5
    4970  326.37  4987.4  322.86  4990.2  322.36  4993.4  322.86  5004.3  323.99
  5010.8  325.93  5021.1  326.75  5054.4  326.29  5143.6  329.02  5204.9  328.11
  5327.5  328.37  5432.7  331.28  5521.6  334.75  5623.8  337.59  5761.9  339.19
#Mann= 5 ,-1 , 0
  3458.2     .05       0  4987.4     .03       0  4993.4     .05       0
  5432.7      .1       0  5623.8     .05       0
Bank Sta=4987.4,4993.4
XS Rating Curve= 0 ,0
Exp/Cntr=0.3,0.1

Type RM Length L Ch R = 1 ,23631   ,186,186,186
BEGIN DESCRIPTION:
LITTLE WICKSON CREEK 30.0
END DESCRIPTION:
XS GIS Cut Line= 2
      3544238.33     10256924.94      3542992.13     10255591.67
#Sta/Elev= 30
  3946.1   331.8  3956.1  331.65  3961.9   331.5  4115.3  330.45  4250.2  327.73
    4554  324.78  4596.5  324.98    4618  325.92  4681.5  323.18  4709.9  323.79
    4809  322.47  4879.8  324.88  4929.2  324.91  4971.7  323.05  4985.9  321.48
    4997  318.98  4999.8  318.48    5003  318.98  5028.4  321.71  5099.2  324.27
  5148.5  323.95  5219.4  325.63  5290.6  326.09  5346.8  325.75  5417.2  326.79
  5495.4  329.16  5579.9  333.88  5601.4  333.89  5735.7  337.47  5771.1  337.64
#Mann= 6 ,-1 , 0
  3946.1     .05       0  3956.1      .1       0  3961.9     .05       0
    4997     .04       0    5003     .05       0  5290.6      .1       0
Bank Sta=4997,5003
XS Rating Curve= 0 ,0
Exp/Cntr=0.3,0.1

Type RM Length L Ch R = 1 ,23445   ,477,477,477
BEGIN DESCRIPTION:
LITTLE WICKSON CREEK 28.0
END DESCRIPTION:
XS GIS Cut Line= 2
      3544391.09     10256841.59      3543113.35     10255466.63
#Sta/Elev= 30
  3957.7   330.8  4125.2  328.46  4178.3  327.97  4264.4  326.77  4317.5  326.52
  4403.6  326.12  4456.6  325.76  4657.3   324.7  4678.8  323.49  4707.2  319.62
  4735.5  322.26  4821.3  322.34  4960.5  322.61  4982.7  321.86  5001.2  317.19
    5004  316.69  5007.2  317.19  5018.4  320.41  5025.2  319.21  5032.6  321.94
  5039.4  321.51  5060.9  324.49  5152.3  325.42  5187.9  325.65  5237.8  323.47
  5430.5  327.48  5517.4  328.56  5552.2   329.4  5830.4  334.29  5834.7  334.39
#Mann= 16 ,-1 , 0
  3957.7      .1       0  4125.2     .05       0  4178.3      .1       0
  4264.4     .05       0  4317.5      .1       0  4403.6     .05       0
  4456.6      .1       0  4821.3     .16       0  4960.5      .1       0
  5001.2     .07       0  5007.2      .1       0  5152.3     .12       0
  5430.5      .1       0  5517.4     .05       0  5552.2      .1       0
  5830.4     .05       0
Bank Sta=5001.2,5007.2
XS Rating Curve= 0 ,0
Exp/Cntr=0.3,0.1

Type RM Length L Ch R = 1 ,22968   ,2023,2023,2023
BEGIN DESCRIPTION:
LITTLE WICKSON CREEK 26.0
END DESCRIPTION:
XS GIS Cut Line= 3
      3544696.68     10256737.46      3543939.72     10255647.16
      3543974.31     10255225.08
#Sta/Elev= 30
  3974.8  329.65  4103.6  326.65  4126.9  327.38  4183.6  325.54  4284.9  324.38
  4661.1  324.19  4794.8  321.97  4809.7   320.3  4821.9  316.78  4830.6  317.72
  4836.7  320.29  4845.5  320.77  4902.2  319.48  4908.3  320.38  4980.1  320.99
  4988.6  320.66  5000.5  316.72  5003.2  316.22  5006.5  316.72  5009.6  319.44
  5024.4  321.09  5062.3  321.84  5182.5   325.7  5239.2  326.36  5367.8  329.78
  5528.4  332.23  5614.5  335.11    5624  335.39  5678.9  337.12  5725.6  339.68
#Mann= 7 ,-1 , 0
  3974.8     .05       0  4661.1     .16       0  5000.5     .07       0
  5006.5     .16       0  5062.3     .05       0  5614.5      .1       0
    5624     .05       0
Bank Sta=5000.5,5006.5
XS Rating Curve= 0 ,0
Exp/Cntr=0.3,0.1

Type RM Length L Ch R = 1 ,20945   ,2027,2027,2027
BEGIN DESCRIPTION:
LITTLE WICKSON CREEK 24.0
END DESCRIPTION:
XS GIS Cut Line= 3
      3544942.08     10256691.67      3545542.11     10256141.64
      3545742.11     10255741.63
#Sta/Elev= 30
  4200.3  331.23  4256.8   330.1  4384.4  325.65  4455.3  323.87  4568.2   322.2
  4795.1  320.01  4901.1  318.36  4943.7  317.12    4972  317.77  4986.2  316.52
  4997.4  313.06  5000.2  312.56  5003.4  313.06  5007.2  313.46  5010.9  315.58
  5017.1  315.58  5028.3   319.3    5045  319.31    5073  316.33  5089.7   316.2
  5103.7  318.27  5117.7  319.45  5162.4  320.22  5179.2  321.62  5246.3  325.01
    5291  326.73  5296.6  326.49  5402.8  334.68  5408.4  334.53  5461.5  338.39
#Mann= 3 ,-1 , 0
  4200.3     .05       0  4997.4     .07       0  5003.4     .16       0
Bank Sta=4997.4,5003.4
XS Rating Curve= 0 ,0
Exp/Cntr=0.3,0.1

Type RM Length L Ch R = 1 ,18918   ,2064,2064,2064
BEGIN DESCRIPTION:
LITTLE WICKSON CREEK 21.0
END DESCRIPTION:
XS GIS Cut Line= 3
       3546542.1     10257341.66      3546592.11     10256591.64
      3546692.11     10256241.63
#Sta/Elev= 30
  4267.3  324.55  4497.8  318.43  4628.1  317.44  4728.3  315.14  4788.5  315.32
  4908.7  313.93  4948.8  312.24  4978.9  312.05  4998.9  307.73    5006  307.21
  5008.7  306.71    5012  307.21  5014.3  308.39  5016.5  309.52  5021.6  309.52
  5029.4  311.58  5050.2  312.34  5069.7  312.56  5081.4  311.86    5123  311.46
  5133.4  312.15  5142.5  313.73  5147.7   312.7  5181.5  318.87  5220.5  320.31
  5254.3  322.86    5279  323.77  5327.1  327.76  5332.3  327.56    5383  331.45
#Mann= 4 ,-1 , 0
  4267.3     .05       0    5006    .035       0    5012     .05       0
  5014.3     .16       0
Bank Sta=5006,5012
XS Rating Curve= 0 ,0
Exp/Cntr=0.3,0.1

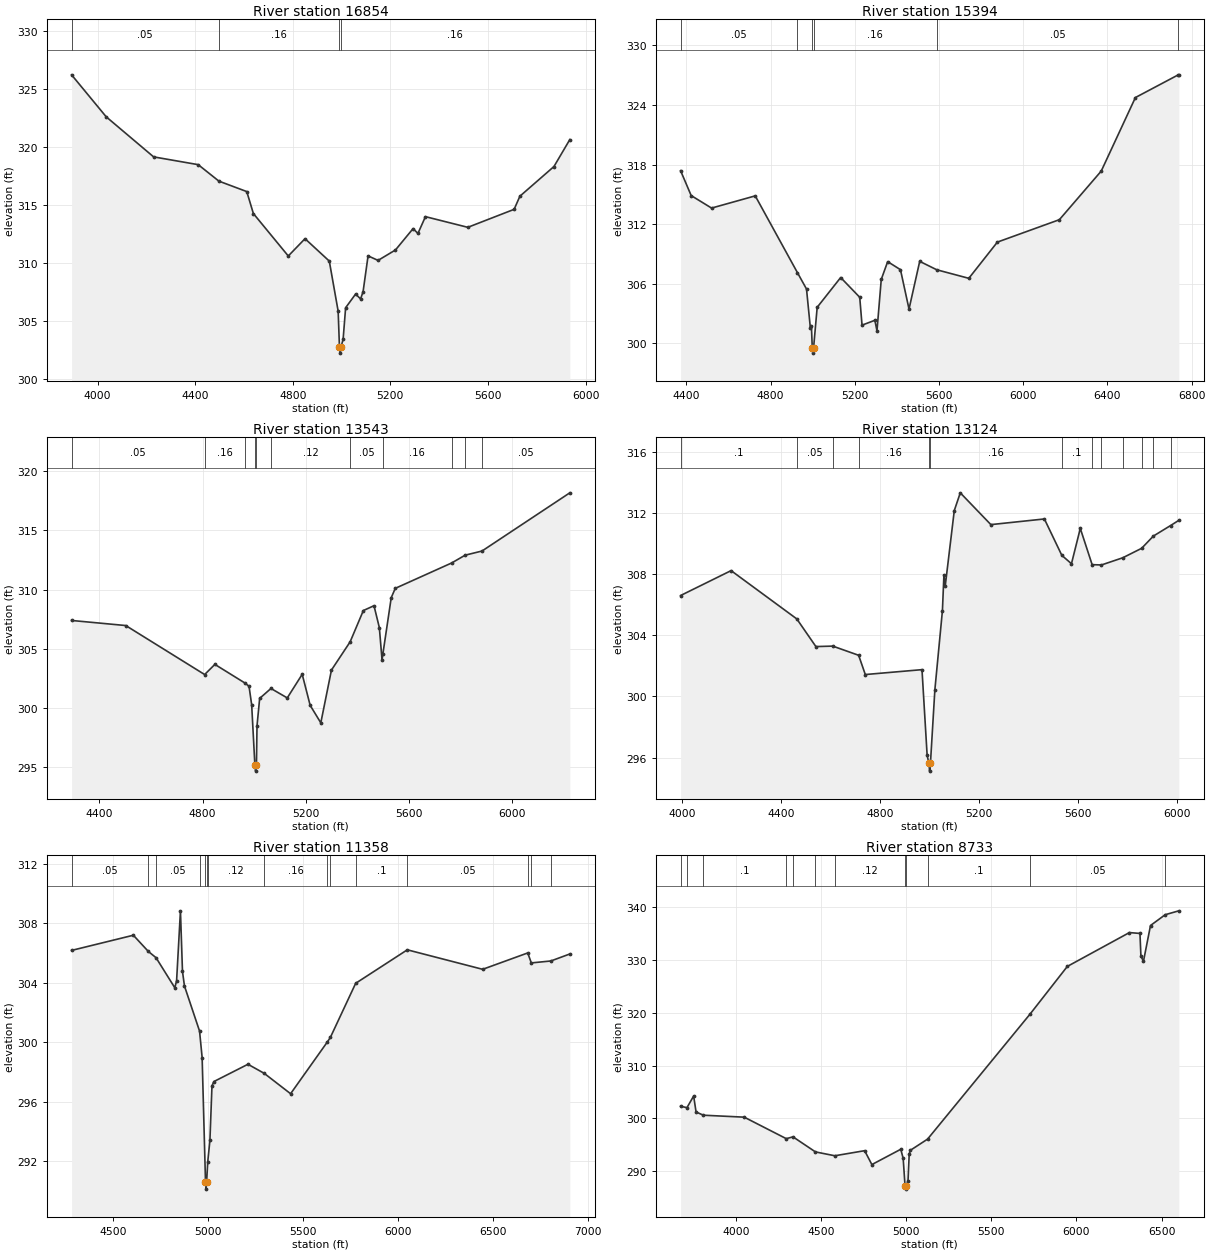
Type RM Length L Ch R = 1 ,16854   ,1460,1460,1460
BEGIN DESCRIPTION:
LITTLE WICKSON CREEK 17.0
END DESCRIPTION:
XS GIS Cut Line= 3
      3548424.96      10257670.6      3548088.59     10256075.55
      3547697.96     10255945.34
#Sta/Elev= 30
  3893.6  326.21  4035.6  322.59  4229.8  319.14  4412.5  318.47  4497.4  317.05
  4611.6  316.15  4638.6  314.26  4781.7   310.6  4850.3  312.09  4949.8  310.16
  4986.1  305.85  4991.5  302.73  4994.3  302.23  4997.5  302.73  5006.5  303.43
  5016.7  306.14  5057.6  307.32  5078.1   306.9  5088.3  307.53  5108.7  310.61
  5149.6  310.22  5221.1  311.12  5293.2  312.96  5313.1  312.54  5343.8  313.99
  5517.5  313.07  5707.3  314.62  5730.9  315.75  5870.6  318.31  5935.5  320.63
#Mann= 4 ,-1 , 0
  3893.6     .05       0  4497.4     .16       0  4991.5     .07       0
  4997.5     .16       0
Bank Sta=4991.5,4997.5
XS Rating Curve= 0 ,0
Exp/Cntr=0.3,0.1

Type RM Length L Ch R = 1 ,15394   ,1851,1851,1851
BEGIN DESCRIPTION:
LITTLE WICKSON CREEK 16.0
END DESCRIPTION:
XS GIS Cut Line= 2
      3549282.16     10257041.24      3548880.69     10254708.34
#Sta/Elev= 30
    4372  317.38  4422.3  314.87  4519.2  313.61  4726.7  314.84  4927.2   307.1
  4970.3  305.45  4988.5  301.55  4993.5  301.76  4997.7  299.49  5000.5  298.99
  5003.7  299.49    5021  303.61  5132.6  306.61  5223.1  304.62  5234.1  301.81
    5295   302.3  5305.1  301.24  5325.4  306.42  5355.9  308.21  5416.7   307.4
  5457.3  303.43  5508.1  308.24  5589.2  307.39  5741.4  306.53  5877.1  310.18
  6171.7  312.44  6370.6  317.34  6532.9  324.75  6736.7  327.04  6739.2  327.04
#Mann= 6 ,-1 , 0
    4372     .05       0  4927.2     .16       0  4997.7     .07       0
  5003.7     .16       0  5589.2     .05       0  6736.7      .1       0
Bank Sta=4997.7,5003.7
XS Rating Curve= 0 ,0
Exp/Cntr=0.3,0.1

Type RM Length L Ch R = 1 ,13543   ,419,419,419
BEGIN DESCRIPTION:
LITTLE WICKSON CREEK 14.0
END DESCRIPTION:
XS GIS Cut Line= 4
      3550177.83     10256205.35      3550012.91     10255745.31
      3549795.89     10254894.61       3549431.3     10254460.57
#Sta/Elev= 30
  4291.9  307.38  4502.2  306.95  4808.3   302.8    4848  303.66  4963.3   302.1
  4980.5  301.81  4990.8  300.24  5003.3  295.12  5006.1  294.62  5009.3  295.12
  5011.5  298.45  5021.8  300.78  5065.7  301.62  5128.9  300.82  5186.9  302.82
  5217.8  300.19  5259.1  298.71  5300.4  303.18  5372.9  305.57  5424.2  308.22
  5465.5  308.63  5486.2  306.78  5496.7  304.05  5500.1  304.56  5532.4  309.31
  5548.1   310.1  5766.9  312.25  5819.3  312.91  5884.6  313.26  6225.4  318.19
#Mann= 11 ,-1 , 0
  4291.9     .05       0  4808.3     .16       0  4963.3     .05       0
  5003.3     .04       0  5009.3     .05       0  5065.7     .12       0
  5372.9     .05       0  5500.1     .16       0  5766.9     .05       0
  5819.3     .16       0  5884.6     .05       0
Bank Sta=5003.3,5009.3
XS Rating Curve= 0 ,0
Exp/Cntr=0.3,0.1

Type RM Length L Ch R = 1 ,13124   ,1766,1766,1766
BEGIN DESCRIPTION:
LITTLE WICKSON CREEK 13.0
END DESCRIPTION:
XS GIS Cut Line= 4
      3550368.82     10256162.01      3550099.71     10255319.96
      3549943.46      10254677.6      3549674.72     10254296.16
#Sta/Elev= 30
    3994   306.6  4197.9  308.23  4463.2  305.07  4540.3  303.26  4608.4  303.29
  4712.9  302.69  4739.8  301.43  4968.7  301.75  4989.5  296.14  4996.8  295.61
  4999.5  295.11  5002.8  295.61  5020.7  300.43  5051.2  305.61  5057.3  307.96
  5062.5  307.22  5099.1  312.16  5123.3  313.32  5246.8  311.24  5462.9  311.61
  5533.3  309.23  5572.2  308.68  5607.9  310.99  5655.7  308.62  5693.3   308.6
  5779.3  309.07  5855.6  309.69  5902.9  310.49  5972.5  311.18  6005.7  311.52
#Mann= 13 ,-1 , 0
    3994      .1       0  4463.2     .05       0  4608.4      .1       0
  4712.9     .16       0  4996.8     .07       0  5002.8     .16       0
  5533.3      .1       0  5655.7     .05       0  5693.3      .1       0
  5779.3     .05       0  5855.6      .1       0  5902.9     .05       0
  5972.5      .1       0
Bank Sta=4996.8,5002.8
XS Rating Curve= 0 ,0
Exp/Cntr=0.3,0.1

Type RM Length L Ch R = 1 ,11358   ,2625,2625,2625
BEGIN DESCRIPTION:
LITTLE WICKSON CREEK 12.0
END DESCRIPTION:
XS GIS Cut Line= 2
      3551306.31     10255675.88      3550629.23     10253141.16
#Sta/Elev= 30
  4282.1  306.17  4607.4  307.19  4686.4   306.1  4726.9  305.68  4825.7  303.66
  4835.1  304.13  4855.4  308.83  4866.1  304.76  4876.5  303.78    4956  300.75
  4969.6  298.97  4987.3  290.63  4990.1  290.13  4993.3  290.63  4999.1  291.96
  5010.6  293.41  5021.4  297.07  5031.7  297.36  5210.9  298.52  5296.5  297.91
  5435.4  296.54    5629  300.02  5644.7  300.32  5778.1  303.96    6050  306.21
  6446.8   304.9  6684.1     306    6703  305.33  6805.8  305.46  6905.7  305.93
#Mann= 15 ,-1 , 0
  4282.1     .05       0  4686.4      .1       0  4726.9     .05       0
    4956      .1       0  4987.3     .07       0  4993.3      .1       0
  4999.1     .12       0  5296.5     .16       0    5629     .05       0
  5644.7     .16       0  5778.1      .1       0    6050     .05       0
  6684.1     .16       0    6703     .05       0  6805.8      .1       0
Bank Sta=4987.3,4993.3
XS Rating Curve= 0 ,0
Exp/Cntr=0.3,0.1

Type RM Length L Ch R = 1 ,8733    ,970,970,970
BEGIN DESCRIPTION:
LITTLE WICKSON CREEK 11.0
END DESCRIPTION:
XS GIS Cut Line= 3
      3551688.22     10255146.38      3553268.11      10253514.4
      3553433.04     10252880.74
#Sta/Elev= 30
    3675  302.29  3712.3  302.02  3751.7  304.22  3765.9   301.2  3809.1  300.59
  4048.8  300.22  4295.6  296.15  4335.3  296.49    4467  293.64  4580.8  292.91
    4756  293.87  4798.4  291.24  4968.2  294.14  4982.3  292.41  4993.5  287.09
  4996.2  286.59  4999.5  287.09  5010.6   288.1  5017.7  293.24  5024.8  293.95
  5125.5  296.06  5727.7  319.75  5946.4  328.77  6310.9  335.18  6372.9  335.02
  6378.6  330.71  6393.6  329.75  6434.9  336.52  6521.5  338.57  6601.2   339.3
#Mann= 12 ,-1 , 0
    3675      .1       0  3712.3     .05       0  3809.1      .1       0
  4295.6     .05       0  4335.3      .1       0    4467     .16       0
  4580.8     .12       0  4993.5     .07       0  4999.5     .12       0
  5125.5      .1       0  5727.7     .05       0  6521.5     .16       0
Bank Sta=4993.5,4999.5
XS Rating Curve= 0 ,0
Exp/Cntr=0.3,0.1

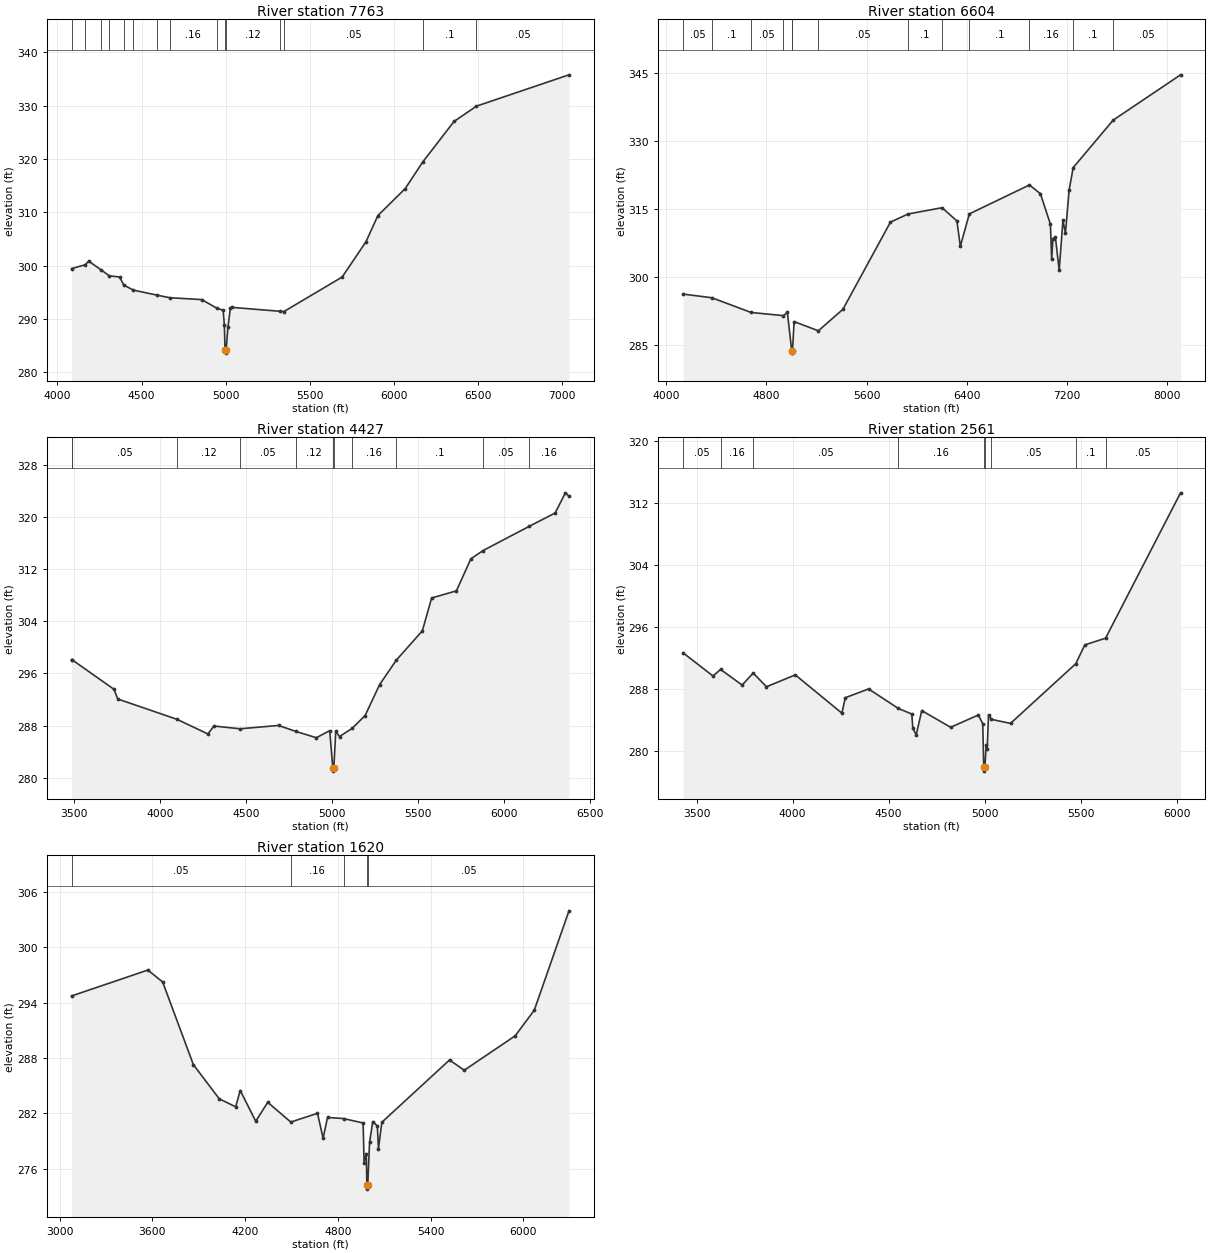
Type RM Length L Ch R = 1 ,7763    ,1159,1159,1159
BEGIN DESCRIPTION:
LITTLE WICKSON CREEK 10.0
END DESCRIPTION:
XS GIS Cut Line= 3
      3552130.93     10255484.92      3553563.25     10254104.68
      3553650.06     10253141.11
#Sta/Elev= 30
  4083.5  299.45  4165.4  300.19  4185.6  300.85  4257.8  299.25  4307.9   298.1
  4369.5  297.88  4393.9  296.37  4450.5  295.43    4593  294.47  4665.9     294
  4857.6  293.64  4945.3  292.06  4984.9  291.64  4991.8  288.86  4996.1   284.1
  4998.8   283.6  5002.1   284.1  5013.2  288.51  5027.4     292  5034.3  292.19
    5323  291.45  5345.9   291.4  5692.1  297.88  5833.6   304.5  5904.4  309.41
  6066.9  314.47  6171.4  319.48  6356.8  327.06    6490  329.93  7040.1  335.81
#Mann= 15 ,-1 , 0
  4083.5     .16       0  4165.4      .1       0  4257.8     .16       0
  4307.9     .05       0  4393.9     .16       0  4450.5     .05       0
    4593      .1       0  4665.9     .16       0  4945.3     .12       0
  4996.1     .07       0  5002.1     .12       0    5323      .1       0
  5345.9     .05       0  6171.4      .1       0    6490     .05       0
Bank Sta=4996.1,5002.1
XS Rating Curve= 0 ,0
Exp/Cntr=0.3,0.1

Type RM Length L Ch R = 1 ,6604    ,2177,2177,2177
BEGIN DESCRIPTION:
LITTLE WICKSON CREEK 7.0
END DESCRIPTION:
XS GIS Cut Line= 3
      3553324.64     10255899.33      3554205.61     10254313.01
      3554214.29     10252151.56
#Sta/Elev= 30
  4133.7  296.26  4363.9  295.45  4676.8  292.21    4936  291.51  4967.2  292.22
    5002  283.75  5004.7  283.25    5008  283.75    5021   290.2  5214.7  288.17
  5411.1  292.91    5791  312.12  5933.3  313.92  6203.8  315.29  6322.2  312.37
  6349.6   306.8  6421.5  313.93  6901.9   320.3  6989.6  318.37  7069.6  311.66
  7079.6  303.89  7089.6  308.47  7109.6  308.77  7139.6  301.51  7169.6  312.49
  7189.6  309.71  7219.6  319.25  7251.8  324.13  7570.9  334.58  8109.7  344.57
#Mann= 13 ,-1 , 0
  4133.7     .05       0  4363.9      .1       0  4676.8     .05       0
    4936     .12       0    5002     .07       0    5008     .12       0
  5214.7     .05       0  5933.3      .1       0  6203.8     .16       0
  6421.5      .1       0  6901.9     .16       0  7251.8      .1       0
  7570.9     .05       0
Bank Sta=5002,5008
XS Rating Curve= 0 ,0
Exp/Cntr=0.3,0.1

Type RM Length L Ch R = 1 ,4427    ,1866,1866,1866
BEGIN DESCRIPTION:
LITTLE WICKSON CREEK 6.0
END DESCRIPTION:
XS GIS Cut Line= 3
      3553945.22     10255953.62      3555481.66     10254590.79
      3555785.47     10253809.55
#Sta/Elev= 30
    3484   298.1  3489.1  298.05  3731.4  293.55  3752.3  292.08  4096.9  288.96
  4276.7  286.72  4311.8  287.93    4464  287.51  4687.3  288.02  4786.4  287.12
  4907.3  286.14    4985  287.22  5002.9  281.52  5005.7  281.02  5008.9  281.52
  5020.1  287.13  5041.9  286.32  5116.1  287.59  5190.8  289.54  5275.2  294.28
  5372.5  298.04  5523.6  302.52  5577.4  307.55  5721.5  308.65  5805.8  313.56
    5877  314.83  6143.1  318.51  6295.5  320.58  6355.3  323.67    6376  323.16
#Mann= 11 ,-1 , 0
    3484      .1       0  3489.1     .05       0  4096.9     .12       0
    4464     .05       0  4786.4     .12       0  5002.9     .07       0
  5008.9     .12       0  5116.1     .16       0  5372.5      .1       0
    5877     .05       0  6143.1     .16       0
Bank Sta=5002.9,5008.9
XS Rating Curve= 0 ,0
Exp/Cntr=0.3,0.1

Type RM Length L Ch R = 1 ,2561    ,941,941,941
BEGIN DESCRIPTION:
LITTLE WICKSON CREEK 4.0
END DESCRIPTION:
XS GIS Cut Line= 3
      3554570.18     10256214.06      3556584.09     10255311.28
      3556540.68     10254929.33
#Sta/Elev= 30
  3429.4  292.68  3584.9   289.7  3624.8  290.54  3736.9  288.53  3794.6  290.08
  3863.8  288.31  4013.8  289.84  4256.6  284.91  4274.3   286.9  4395.7  288.03
  4551.2  285.51  4620.8   284.8  4626.2  282.94  4643.9  282.13  4672.6  285.24
  4823.3  283.09  4967.2  284.67  4990.4  283.55  4995.6  277.94  4998.4  277.44
  5001.6  277.94  5008.1  280.82  5013.6   280.3  5020.5   284.7  5035.5  284.11
    5135  283.59  5474.9  291.28  5522.3  293.71  5630.2  294.57  6020.8   313.3
#Mann= 9 ,-1 , 0
  3429.4     .05       0  3624.8     .16       0  3794.6     .05       0
  4551.2     .16       0  4995.6     .07       0  5001.6     .16       0
  5035.5     .05       0  5474.9      .1       0  5630.2     .05       0
Bank Sta=4995.6,5001.6
XS Rating Curve= 0 ,0
Exp/Cntr=0.3,0.1

Type RM Length L Ch R = 1 ,1620    ,0,0,0
BEGIN DESCRIPTION:
LITTLE WICKSON CREEK 1.0
END DESCRIPTION:
XS GIS Cut Line= 4
      3554865.32     10256743.57      3555646.59     10256882.46
      3556942.25     10255942.22      3556742.11     10255141.65
#Sta/Elev= 30
  3076.6  294.71    3571  297.52  3666.5  296.22  3865.3  287.26  4032.3  283.57
    4139  282.69  4168.4  284.46  4268.9  281.13  4346.4  283.18  4495.8  281.04
  4668.5  281.99  4704.8  279.29  4733.5  281.54  4837.1  281.42  4963.9  280.94
  4970.1  276.65  4984.7   277.6  4987.9  274.27  4990.7  273.77  4993.9  274.27
  5005.6  278.85  5026.5  281.09  5055.9  280.62  5063.1  278.16  5085.2  281.02
  5523.1  287.77  5618.5  286.66  5948.3  290.39    6072  293.18  6296.2  303.94
#Mann= 5 ,-1 , 0
  3076.6     .05       0  4495.8     .16       0  4837.1     .05       0
  4987.9     .03       0  4993.9     .05       0
Bank Sta=4987.9,4993.9
XS Rating Curve= 0 ,0
Exp/Cntr=0.3,0.1

Chan Stop Cuts=-1
Use User Specified Reach Order=0
Composite Channel Slope=5