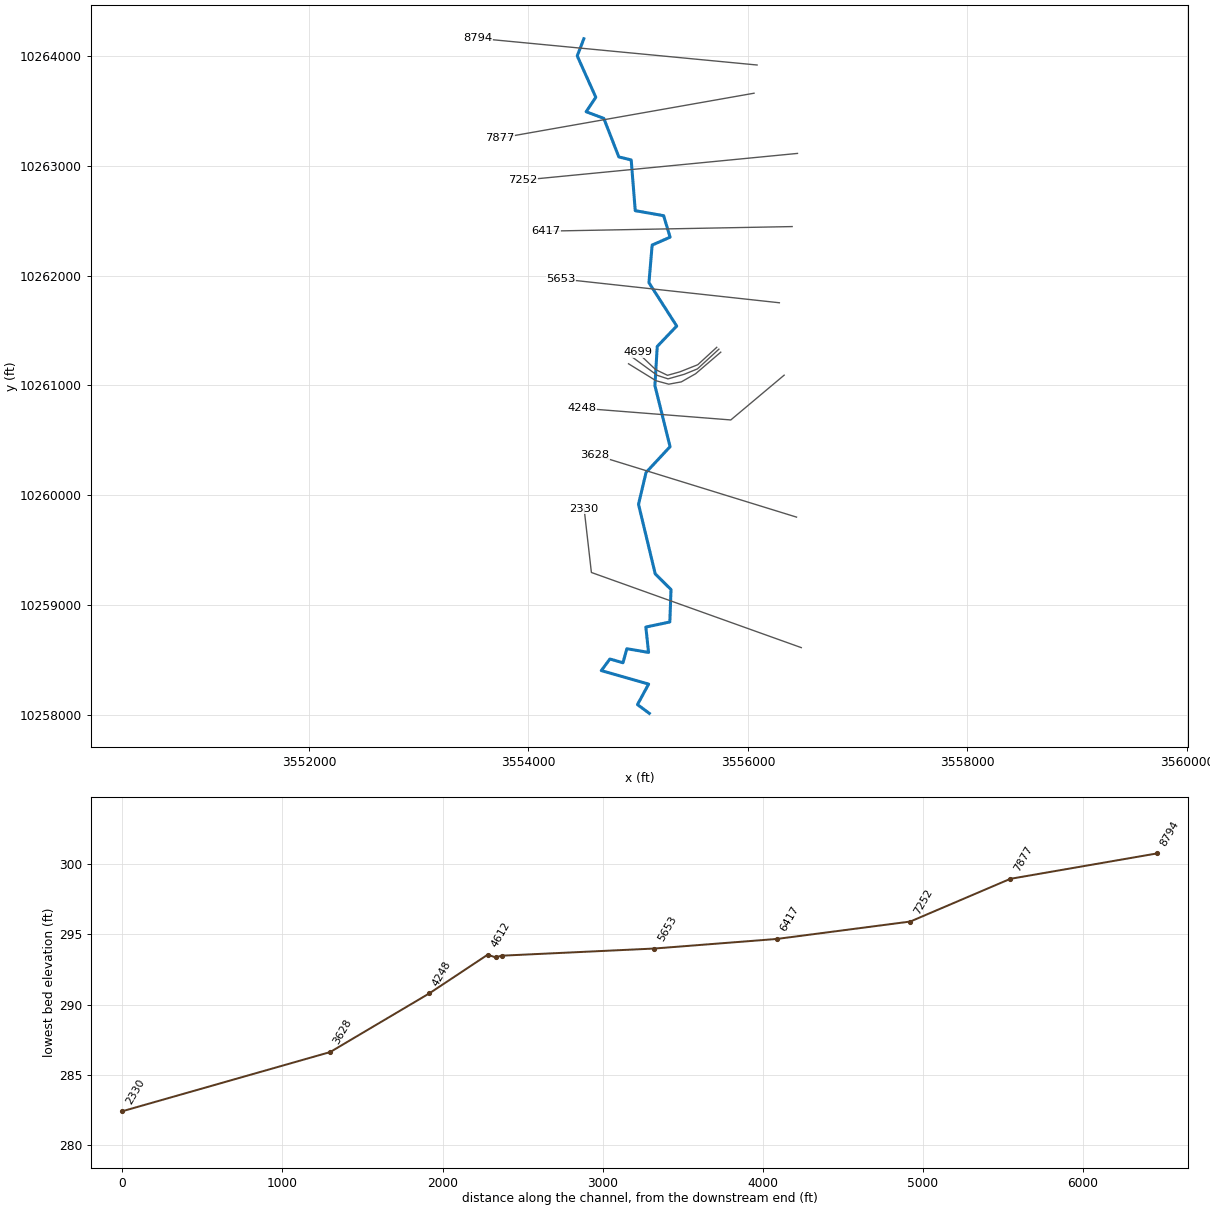
--- WICKSONCRKTRIB33.prj (project) ---

Proj Title=WICKSON CREEK TRIB 33
Current Plan=p01
Default Exp/Contr=0.3,0.1
English Units
Geom File=g01
Flow File=f01
Plan File=p01
Y Axis Title=Elevation
X Axis Title(PF)=Main Channel Distance
X Axis Title(XS)=Station
BEGIN DESCRIPTION:
UNT0496 IN WICK
END DESCRIPTION:
DSS Export Rating Curves= 0
DSS Export Rating Curve Sorted= 0
DSS Export Volume Flow Curves= 0
DXF OffsetX= 0
DXF OffsetY= 0
DXF ScaleX= 1
DXF ScaleY= 10

--- WICKSONCRKTRIB33.p01 (plan) ---

Plan Title=Multiple Run
Short Identifier=Multiple
Geom File=g01
Flow File=f01
Subcritical Flow
K Sum by GR= 0
Std Step Tol= 0.01
Critical Tol= 0.01
Num of Std Step Trials= 20
Max Error Tol= 0.3
Flow Tol Ratio= 0.001
Split Flow NTrial= 30
Split Flow Tol= 0.02
Split Flow Ratio= 0.02
Log Output Level= 0
Friction Slope Method= 1
Unsteady Friction Slope Method= 2
Unsteady Bridges Friction Slope Method= 1
Parabolic Critical Depth
Global Vel Dist=  1 , 1 , 1
Global Log Level= 0
CheckData=True
Encroach Param= -1, 0, 0, 0
BEGIN DESCRIPTION:
Multiple Run
END DESCRIPTION:

--- WICKSONCRKTRIB33.f01 (steady flow) ---

Flow Title=Multiple
Program Version=4.10
Number of Profiles= 7
Profile Names=10-year,25-year,50-year,1pct_min,100-year,1pct_plu,500-year
River Rch & RM=UNT0496 IN WICK,Reach-1         ,8794
     580     784     951     846    1144    1548    1659
River Rch & RM=UNT0496 IN WICK,Reach-1         ,6417
     633     857    1040     924    1250    1690    1809
River Rch & RM=WICKSONCRTR312,Reach-1         ,8794
     580     784     951     846    1144    1548    1659
River Rch & RM=WICKSONCRTR312,Reach-1         ,6417
     633     857    1040     924    1250    1690    1809
River Rch & RM=WICKSONCRTR33,Reach-1         ,8794
     580     784     951     846    1144    1548    1659
River Rch & RM=WICKSONCRTR33,Reach-1         ,6417
     633     857    1040     924    1250    1690    1809
Boundary for River Rch & Prof#=WICKSONCRTR33,Reach-1         , 1
Up Type= 0
Dn Type= 3
Dn Slope=0.005
Boundary for River Rch & Prof#=WICKSONCRTR33,Reach-1         , 2
Up Type= 0
Dn Type= 3
Dn Slope=0.005
Boundary for River Rch & Prof#=WICKSONCRTR33,Reach-1         , 3
Up Type= 0
Dn Type= 3
Dn Slope=0.005
Boundary for River Rch & Prof#=WICKSONCRTR33,Reach-1         , 4
Up Type= 0
Dn Type= 3
Dn Slope=0.005
Boundary for River Rch & Prof#=WICKSONCRTR33,Reach-1         , 5
Up Type= 0
Dn Type= 3
Dn Slope=0.005
Boundary for River Rch & Prof#=WICKSONCRTR33,Reach-1         , 6
Up Type= 0
Dn Type= 3
Dn Slope=0.005
Boundary for River Rch & Prof#=WICKSONCRTR33,Reach-1         , 7
Up Type= 0
Dn Type= 3
Dn Slope=0.005
DSS Import GetInterval= 0
DSS Import GetPeak= 0
DSS Import FillOption= 0

--- WICKSONCRKTRIB33.g01 (geometry) ---

Geom Title=Existing Conditions
Program Version=4.10

River Reach=WICKSONCRTR33   ,Reach-1
Reach XY= 30
      3554505.16     10264158.37      3554445.06     10264002.42
      3554614.33     10263625.68       3554526.2     10263493.84
       3554687.1     10263433.29       3554824.2     10263081.95
      3554936.74     10263054.57      3554973.84     10262592.27
      3555232.25     10262546.68      3555291.29     10262350.66
      3555127.84     10262278.86      3555098.54     10261936.05
      3555351.49     10261541.05      3555174.07     10261355.25
      3555152.94     10260998.45      3555290.98     10260442.06
       3555072.1     10260206.66      3555003.54      10259916.7
      3555155.75     10259283.15      3555299.57     10259139.89
      3555288.85     10258844.55      3555070.04     10258798.04
      3555095.18     10258567.08      3554897.19     10258600.82
      3554861.93      10258472.8      3554742.95     10258507.11
      3554664.19     10258401.36      3555095.72      10258278.6
      3554993.99     10258091.58      3555102.11     10258011.64

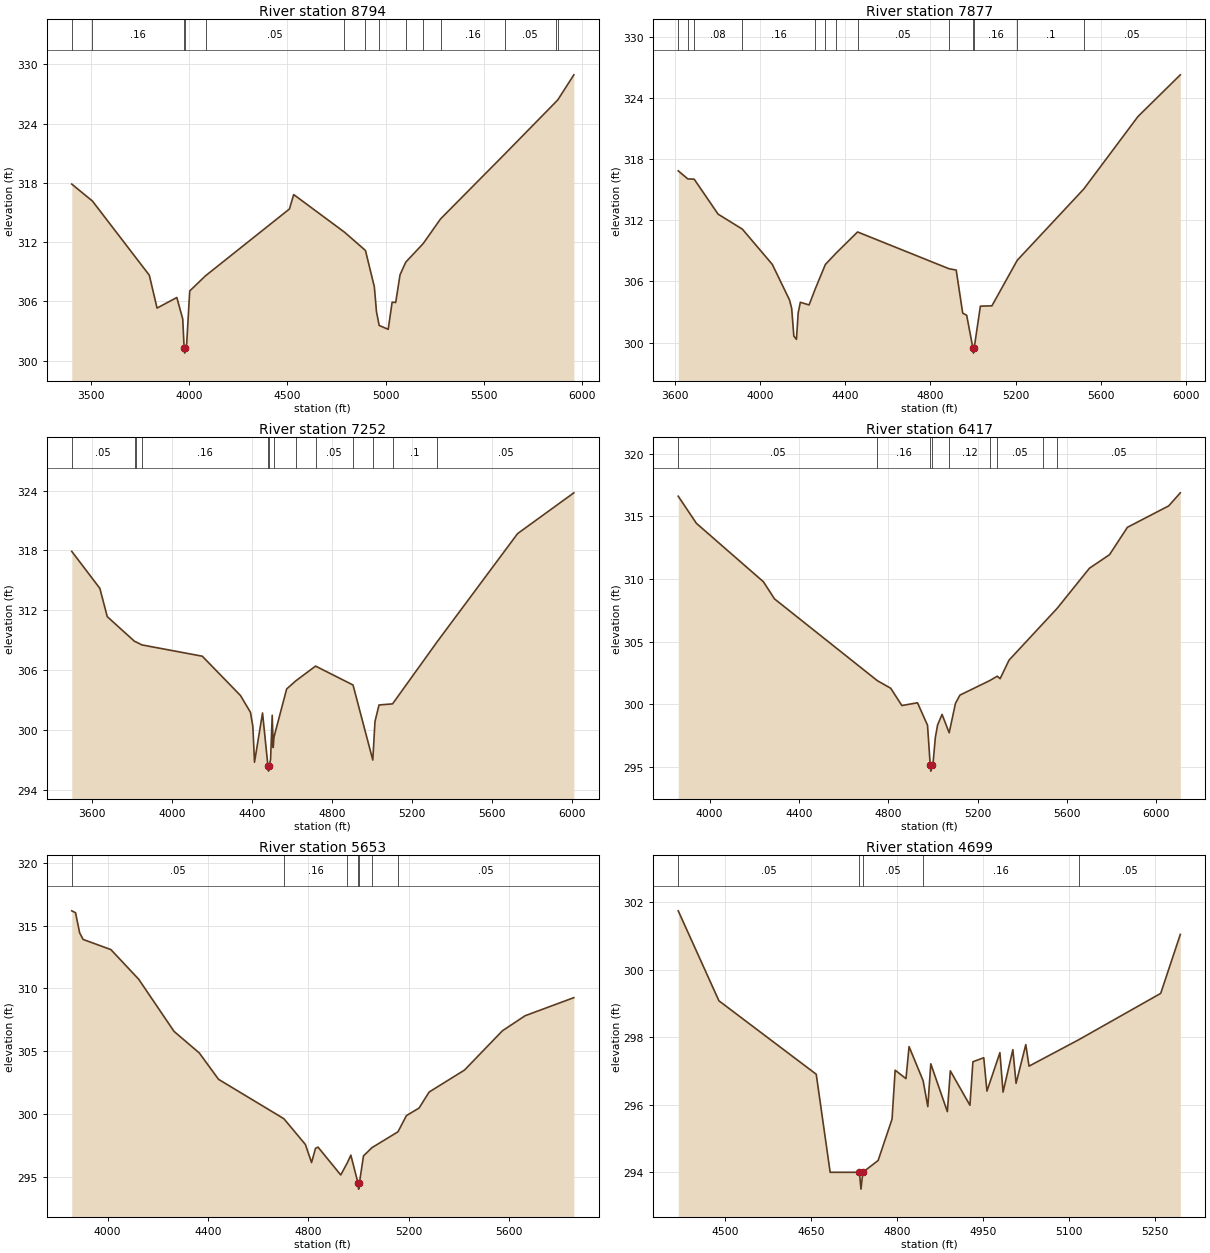
Type RM Length L Ch R = 1 ,8794    ,917,917,917
BEGIN DESCRIPTION:
UNT0496 IN WICK 9.0
END DESCRIPTION:
XS GIS Cut Line= 2
      3556083.95     10263919.53      3553542.25     10264162.59
#Sta/Elev= 30
  3404.1  317.88  3509.4  316.16  3798.4  308.66  3837.9  305.33  3938.4   306.4
  3968.5  304.22  3975.6  301.27  3978.3  300.77  3981.6  301.27  3988.6  301.74
  4003.9  307.06  4084.4   308.6    4511  315.36  4532.7  316.82  4790.6  313.02
  4897.7  311.16  4942.9  307.48  4953.7  304.96  4967.4  303.57  5013.3  303.18
  5033.3  305.92  5051.5   305.9  5073.5   308.7  5102.7  309.98  5191.3  311.86
  5279.3  314.35  5606.1  320.92    5865  326.18  5876.7  326.43  5957.4  328.94
#Mann= 14 ,-1 , 0
  3404.1     .08       0  3509.4     .16       0  3975.6     .07       0
  3981.6     .16       0  4084.4     .05       0  4790.6     .16       0
  4897.7     .05       0  4967.4     .16       0  5102.7      .1       0
  5191.3     .12       0  5279.3     .16       0  5606.1     .05       0
    5865     .16       0  5876.7     .05       0
Bank Sta=3975.6,3981.6
XS Rating Curve= 0 ,0
Exp/Cntr=0.3,0.1

Type RM Length L Ch R = 1 ,7877    ,625,625,625
BEGIN DESCRIPTION:
Mapping XS 7251f6e7
END DESCRIPTION:
XS GIS Cut Line= 2
      3556056.15     10263662.59      3553736.95     10263252.91
#Sta/Elev= 30
  3617.2  316.85  3661.8  316.06  3692.1  316.03  3804.1   312.6  3917.9  311.13
  4058.4  307.67  4139.2  304.18  4149.4  303.34  4159.5  300.63  4171.7  300.31
  4179.8   302.9    4190  303.95    4231  303.69  4259.3  305.23  4307.3  307.66
  4358.9   308.8  4458.4  310.85  4887.5  307.24  4921.1  307.11  4951.6  302.88
  4970.2  302.68  4999.4  299.46  5002.1  298.96  5005.4  299.46  5034.5  303.57
  5088.6   303.6  5207.3  308.07  5519.7  315.07  5773.7  322.18  5972.3  326.27
#Mann= 13 ,-1 , 0
  3617.2     .05       0  3661.8      .1       0  3692.1     .08       0
  3917.9     .16       0  4259.3      .1       0  4307.3     .16       0
  4358.9      .1       0  4458.4     .05       0  4887.5     .16       0
  4999.4     .07       0  5005.4     .16       0  5207.3      .1       0
  5519.7     .05       0
Bank Sta=4999.4,5005.4
XS Rating Curve= 0 ,0
Exp/Cntr=0.3,0.1

Type RM Length L Ch R = 1 ,7252    ,835,835,835
BEGIN DESCRIPTION:
Mapping XS b69a3a96
END DESCRIPTION:
XS GIS Cut Line= 2
      3556452.03     10263113.98      3553952.02     10262870.92
#Sta/Elev= 30
  3498.1  317.91  3638.7  314.21  3675.6  311.38  3812.7   308.9  3818.1  308.86
  3849.2  308.55  4151.1  307.42    4342  303.49  4392.2   301.8    4404   300.4
  4412.3  296.81  4452.5  301.74  4479.6  296.42  4482.4  295.92  4485.6  296.42
  4492.7  297.09  4500.9  301.51  4505.9  298.28  4509.9  299.34  4573.1  304.14
  4618.6  304.95  4717.7  306.43  4905.2  304.54  5004.1  297.03  5015.1  300.89
  5035.2  302.54  5102.9  302.65    5327  308.89  5728.5  319.69  6009.9  323.77
#Mann= 13 ,-1 , 0
  3498.1     .05       0  3812.7     .16       0  3818.1     .05       0
  3849.2     .16       0  4479.6     .07       0  4485.6     .16       0
  4509.9     .12       0  4618.6     .16       0  4717.7     .05       0
  4905.2     .12       0  5004.1     .16       0  5102.9      .1       0
    5327     .05       0
Bank Sta=4479.6,4485.6
XS Rating Curve= 0 ,0
Exp/Cntr=0.3,0.1

Type RM Length L Ch R = 1 ,6417    ,764,764,764
BEGIN DESCRIPTION:
Mapping XS 0d717d26
END DESCRIPTION:
XS GIS Cut Line= 2
      3556403.39     10262447.31      3554155.28     10262405.68
#Sta/Elev= 30
  3859.3   316.6  3940.6  314.44  4240.7  309.78  4290.7  308.41  4751.2  301.89
  4810.8  301.29  4860.8  299.91  4930.8  300.13  4975.7  298.34  4987.8  295.18
  4990.5  294.68  4993.8  295.18  5000.8  295.39  5010.8  297.37  5020.8  298.36
  5040.8   299.2  5072.7  297.74  5100.8  300.08  5120.8  300.74  5254.4   301.9
  5288.2  302.25  5300.8  302.05  5340.8  303.53  5491.5  306.42  5555.8  307.65
  5700.9  310.86  5790.9  311.94  5870.9  314.12  6055.9  315.83  6107.8  316.87
#Mann= 9 ,-1 , 0
  3859.3     .05       0  4751.2     .16       0  4987.8     .07       0
  4993.8     .16       0  5072.7     .12       0  5254.4     .16       0
  5288.2     .05       0  5491.5     .16       0  5555.8     .05       0
Bank Sta=4987.8,4993.8
XS Rating Curve= 0 ,0
Exp/Cntr=0.3,0.1

Type RM Length L Ch R = 1 ,5653    ,954,954,954
BEGIN DESCRIPTION:
UNT0496 IN WICK 7.0
END DESCRIPTION:
XS GIS Cut Line= 2
      3556287.06     10261753.07      3554299.27     10261970.07
#Sta/Elev= 30
  3857.4  316.18  3872.4  316.03  3888.9  314.42  3902.6   313.9  4013.3  313.09
  4123.9  310.73  4264.8  306.57  4365.4  304.85    4442  302.75  4702.3  299.61
  4787.8  297.56  4812.4  296.12  4828.1  297.25  4838.1  297.35  4928.7  295.13
  4955.4  296.12  4968.9  296.71  4997.1   294.5  4999.9     294  5003.1   294.5
  5019.2  296.65  5053.3  297.31  5156.6  298.57  5190.2  299.86  5240.5  300.46
  5280.8  301.74  5421.6  303.49  5572.5  306.62    5663  307.82    5857  309.26
#Mann= 7 ,-1 , 0
  3857.4     .05       0  4702.3     .16       0  4955.4     .12       0
  4997.1     .07       0  5003.1     .12       0  5053.3     .16       0
  5156.6     .05       0
Bank Sta=4997.1,5003.1
XS Rating Curve= 0 ,0
Exp/Cntr=0.3,0.1

Type RM Length L Ch R = 1 ,4699    ,37,37,37
BEGIN DESCRIPTION:
UNT0496 IN WICK 6.0
END DESCRIPTION:
XS GIS Cut Line= 6
      3555716.52      10261347.3      3555543.33     10261188.44
      3555379.27     10261123.33      3555267.29     10261092.08
      3555159.22     10261144.17      3554993.89     10261301.69
#Sta/Elev= 30
  4417.9  301.75  4488.9  299.08  4658.7   296.9    4683  293.99    4734  293.99
  4736.8  293.49    4740  293.99  4766.7  294.34    4791  295.57  4796.4  297.02
  4815.3  296.77  4820.7  297.72  4845.2  296.71  4853.4  295.94  4858.6  297.21
  4887.5  295.79  4892.7     297  4926.9  295.98  4932.1  297.27    4951  297.39
  4956.6   296.4  4979.2  297.54  4984.7  296.37  5001.8  297.63  5007.4  296.63
  5024.4  297.78    5030  297.14  5117.4  297.93  5259.8   299.3    5294  301.05
#Mann= 5 ,-1 , 0
  4417.9     .05       0    4734     .07       0    4740     .05       0
  4845.2     .16       0  5117.4     .05       0
Bank Sta=4734,4740
XS Rating Curve= 0 ,0
Exp/Cntr=0.3,0.1

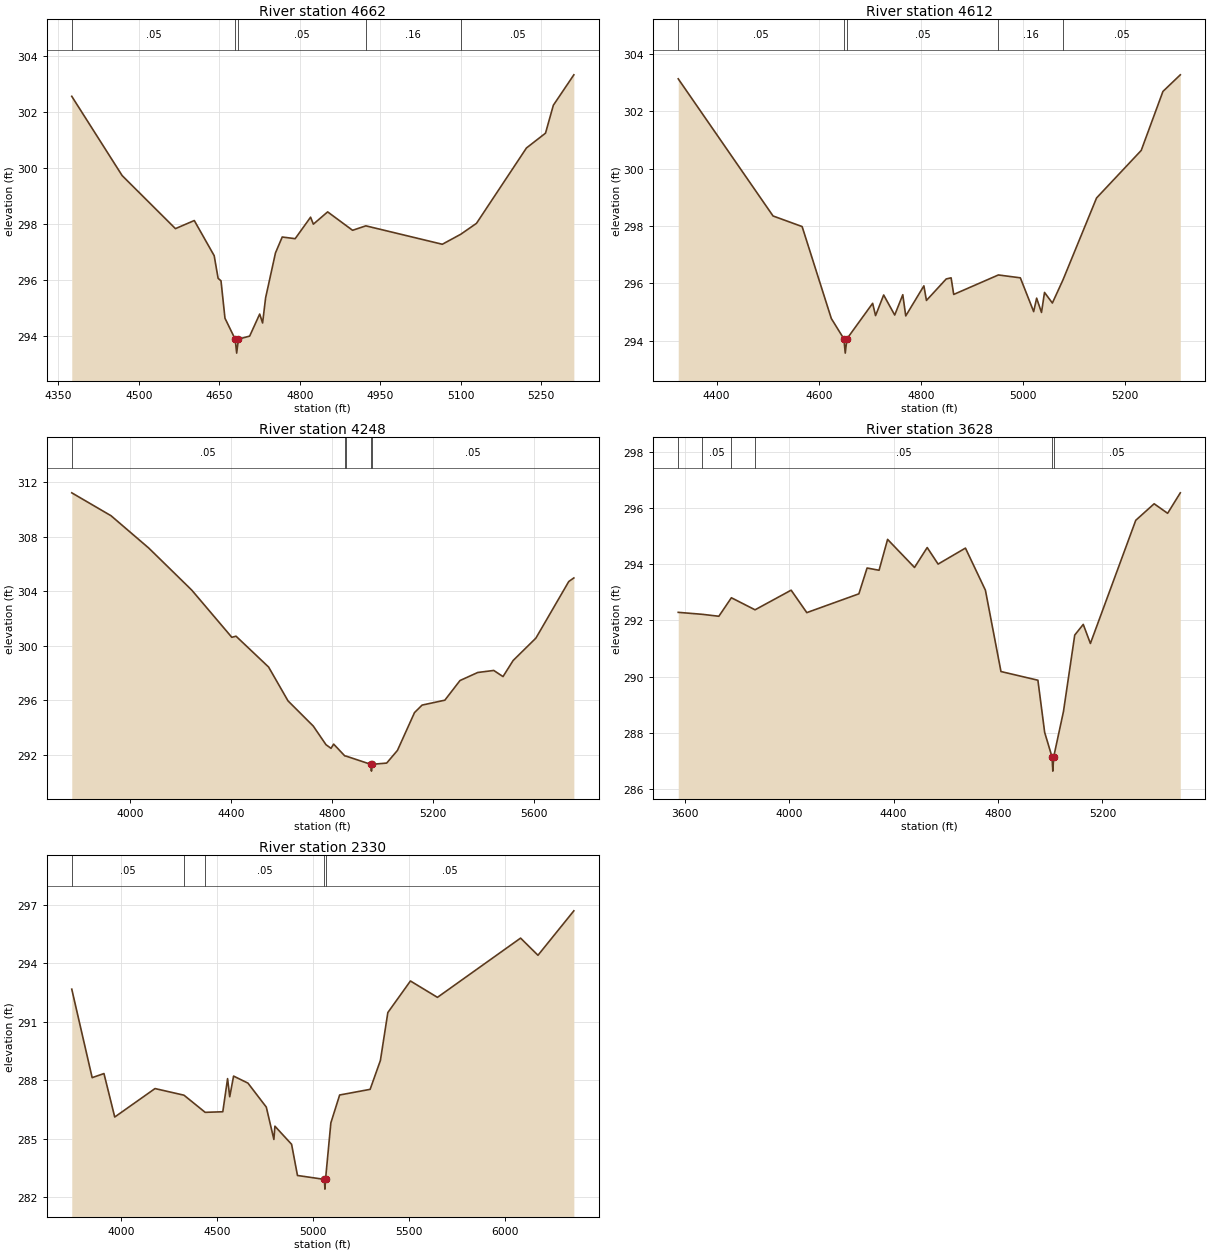
Type RM Length L Ch R = 1 ,4662    ,50,50,50
BEGIN DESCRIPTION:
Mapping XS 3616ba38
END DESCRIPTION:
XS GIS Cut Line= 6
      3555736.06     10261330.38      3555540.73     10261150.68
      3555419.64      10261101.2       3555272.5     10261059.53
      3555173.54     10261092.08      3554945.71     10261258.73
#Sta/Elev= 30
  4375.2  302.57  4469.1  299.73  4568.4  297.83  4603.5  298.12  4640.6  296.86
  4647.9  296.05  4653.3  295.96  4660.7  294.62  4679.7  293.87  4682.5  293.37
  4685.7  293.87  4706.7  293.98  4725.4  294.77  4730.8  294.45  4736.4  295.35
  4754.8  296.96  4767.4  297.53  4791.5  297.47  4820.2  298.24  4825.4  297.99
    4852  298.43  4898.5  297.77  4923.2  297.93  5065.7  297.27  5100.2  297.63
  5129.4  298.02  5222.5  300.72    5258  301.25  5272.6  302.25  5310.8  303.34
#Mann= 5 ,-1 , 0
  4375.2     .05       0  4679.7     .07       0  4685.7     .05       0
  4923.2     .16       0  5100.2     .05       0
Bank Sta=4679.7,4685.7
XS Rating Curve= 0 ,0
Exp/Cntr=0.3,0.1

Type RM Length L Ch R = 1 ,4612    ,364,364,364
BEGIN DESCRIPTION:
Mapping XS fa36df87
END DESCRIPTION:
XS GIS Cut Line= 6
      3555752.95     10261303.01       3555523.8     10261106.41
      3555393.59     10261032.19      3555279.01     10261011.35
      3555163.13      10261042.6      3554912.53     10261197.12
#Sta/Elev= 30
  4324.9  303.14  4510.5  298.35  4567.4  297.98  4624.5  294.77  4649.1  294.06
  4651.8  293.56  4655.1  294.06  4705.4   295.3  4711.1  294.87    4727  295.59
  4748.6  294.89  4764.4   295.6  4770.2  294.86  4805.7  295.91  4810.7   295.4
  4849.4  296.15    4859  296.19  4864.1  295.61  4951.5  296.29  4994.5  296.19
  5020.6  295.01  5026.4  295.48  5035.9  294.98  5041.8  295.68  5057.2  295.31
    5078  296.12  5143.7  298.98  5231.1  300.64  5273.6   302.7  5307.6  303.28
#Mann= 5 ,-1 , 0
  4324.9     .05       0  4649.1     .07       0  4655.1     .05       0
  4951.5     .16       0    5078     .05       0
Bank Sta=4649.1,4655.1
XS Rating Curve= 0 ,0
Exp/Cntr=0.3,0.1

Type RM Length L Ch R = 1 ,4248    ,620,620,620
BEGIN DESCRIPTION:
UNT0496 IN WICK 4.0
END DESCRIPTION:
XS GIS Cut Line= 3
      3556330.51     10261093.36      3555844.38     10260685.36
      3554492.11     10260791.64
#Sta/Elev= 30
  3767.7  311.21  3923.5  309.53  4073.1  307.16  4243.5  304.08  4402.4  300.62
  4419.2   300.7  4548.3  298.44  4625.3  295.96  4725.6  294.11  4775.8  292.75
  4795.8  292.48  4806.3  292.79  4850.2  291.93  4857.2   291.9  4953.3  291.31
  4956.1  290.81  4959.3  291.31  5016.5   291.4  5059.3  292.33  5126.9   295.1
    5157  295.65  5247.2  296.01  5307.3  297.45  5377.6  298.04  5441.3  298.19
  5477.9  297.74  5518.1  298.92  5608.3  300.56  5738.7  304.71  5758.8  304.97
#Mann= 5 ,-1 , 0
  3767.7     .05       0  4850.2     .16       0  4857.2     .05       0
  4953.3     .03       0  4959.3     .05       0
Bank Sta=4953.3,4959.3
XS Rating Curve= 0 ,0
Exp/Cntr=0.3,0.1

Type RM Length L Ch R = 1 ,3628    ,1298,1298,1298
BEGIN DESCRIPTION:
UNT0496 IN WICK 2.0
END DESCRIPTION:
XS GIS Cut Line= 2
      3556443.31     10259799.94      3554605.67     10260367.54
#Sta/Elev= 30
  3574.9  292.29  3666.6  292.22  3730.5  292.15  3778.5  292.81  3869.2  292.38
  4007.4  293.08  4067.4  292.28  4266.9  292.95  4298.3  293.87  4344.2  293.79
  4376.9  294.89    4480  293.89  4528.6   294.6  4570.4  294.01  4675.1  294.58
  4751.6  293.08  4811.2  290.18  4952.7  289.87  4978.6  288.01    5007  287.13
  5009.8  286.63    5013  287.13  5050.7  288.76  5093.8  291.48  5126.4  291.86
  5153.8  291.18  5327.5  295.57    5398  296.16  5449.6  295.82  5498.2  296.55
#Mann= 6 ,-1 , 0
  3574.9     .16       0  3666.6     .05       0  3778.5      .1       0
  3869.2     .05       0    5007     .03       0    5013     .05       0
Bank Sta=5007,5013
XS Rating Curve= 0 ,0
Exp/Cntr=0.3,0.1

Type RM Length L Ch R = 1 ,2330    ,0,0,0
BEGIN DESCRIPTION:
UNT0496 IN WICK 1.0
END DESCRIPTION:
XS GIS Cut Line= 3
      3556486.77     10258610.69      3554574.15     10259295.51
      3554507.65      10259877.4
#Sta/Elev= 30
  3743.1  292.68  3849.4  288.14  3910.9  288.35  3967.1  286.12  4177.1  287.58
    4328  287.24  4438.6  286.36  4530.4  286.39  4555.3  288.09  4566.5  287.16
  4586.6  288.22  4661.5  287.86  4757.1  286.63  4796.7  284.97    4802  285.65
    4889  284.72  4919.7  283.12  5059.9  282.92  5062.7  282.42  5065.9  282.92
  5093.7  285.82  5139.5  287.25  5298.4  287.54  5351.9  289.02  5390.7  291.48
  5508.5   293.1  5649.3  292.26  6082.7   295.3  6173.3  294.42  6360.3   296.7
#Mann= 5 ,-1 , 0
  3743.1     .05       0    4328      .1       0  4438.6     .05       0
  5059.9     .03       0  5065.9     .05       0
Bank Sta=5059.9,5065.9
XS Rating Curve= 0 ,0
Exp/Cntr=0.3,0.1

Chan Stop Cuts=-1
Use User Specified Reach Order=0
Composite Channel Slope=5