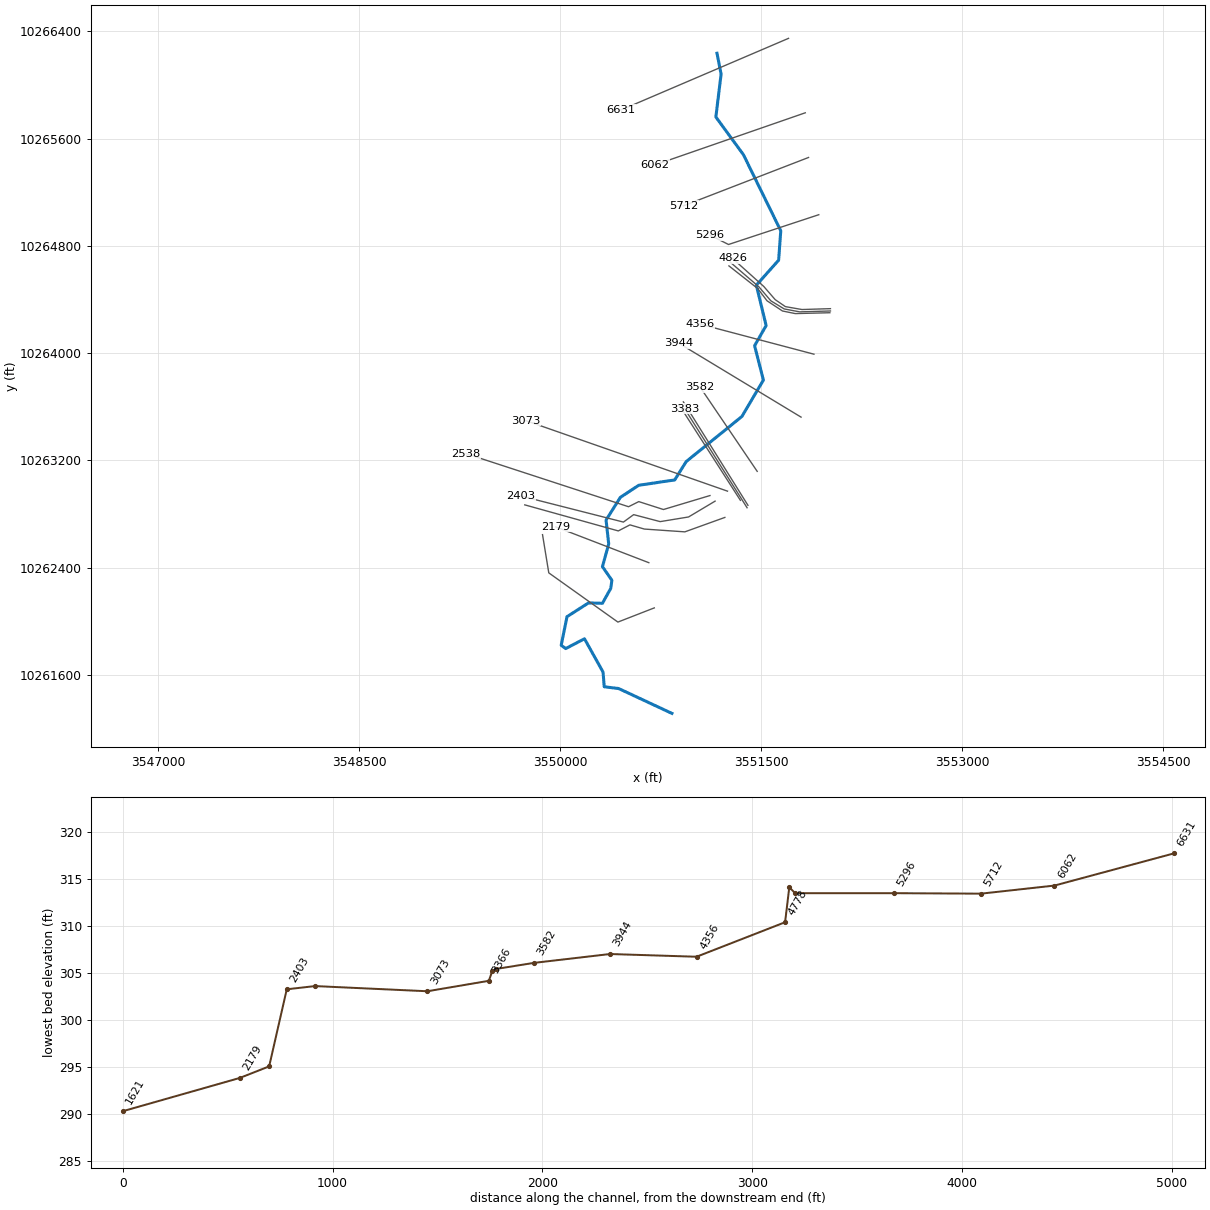
--- WICKSONCREEKTRIB.prj (project) ---

Proj Title=WICKSON CREEK TRIB 36
Current Plan=p01
Default Exp/Contr=0.3,0.1
English Units
Geom File=g01
Flow File=f01
Plan File=p01
Y Axis Title=Elevation
X Axis Title(PF)=Main Channel Distance
X Axis Title(XS)=Station
BEGIN DESCRIPTION:
UNT05134 IN WICK
END DESCRIPTION:
DSS Export Rating Curves= 0
DSS Export Rating Curve Sorted= 0
DSS Export Volume Flow Curves= 0
DXF Filename=UNT05134 IN WICK.
DXF OffsetX= 0
DXF OffsetY= 0
DXF ScaleX= 1
DXF ScaleY= 10

--- WICKSONCREEKTRIB.p01 (plan) ---

Plan Title=Multiple Run
Short Identifier=Multiple
Geom File=g01
Flow File=f01
Subcritical Flow
K Sum by GR= 0
Std Step Tol= 0.01
Critical Tol= 0.01
Num of Std Step Trials= 20
Max Error Tol= 0.3
Flow Tol Ratio= 0.001
Split Flow NTrial= 30
Split Flow Tol= 0.02
Split Flow Ratio= 0.02
Log Output Level= 0
Friction Slope Method= 1
Unsteady Friction Slope Method= 2
Unsteady Bridges Friction Slope Method= 1
Parabolic Critical Depth
Global Vel Dist=  1 , 1 , 1
Global Log Level= 0
CheckData=True
Encroach Param= -1, 0, 0, 0
BEGIN DESCRIPTION:
Multiple Run
END DESCRIPTION:

--- WICKSONCREEKTRIB.f01 (steady flow) ---

Flow Title=Multiple
Program Version=4.10
Number of Profiles= 7
Profile Names=10-year,25-year,50-year,1pct_min,100-year,1pct_plu,500-year
River Rch & RM=UNT05134 IN WICK,Reach-1         ,6631
     254     323     377     323     437     590     586
River Rch & RM=UNT05134 IN WICK,Reach-1         ,3073
     354     462     547     475     643     869     888
River Rch & RM=WICKSONCRTRB36,Reach-1         ,6631
     254     323     377     323     437     590     586
River Rch & RM=WICKSONCRTRB36,Reach-1         ,3073
     354     462     547     475     643     869     888
Boundary for River Rch & Prof#=WICKSONCRTRB36,Reach-1         , 1
Up Type= 0
Dn Type= 3
Dn Slope=0.005
Boundary for River Rch & Prof#=WICKSONCRTRB36,Reach-1         , 2
Up Type= 0
Dn Type= 3
Dn Slope=0.005
Boundary for River Rch & Prof#=WICKSONCRTRB36,Reach-1         , 3
Up Type= 0
Dn Type= 3
Dn Slope=0.005
Boundary for River Rch & Prof#=WICKSONCRTRB36,Reach-1         , 4
Up Type= 0
Dn Type= 3
Dn Slope=0.005
Boundary for River Rch & Prof#=WICKSONCRTRB36,Reach-1         , 5
Up Type= 0
Dn Type= 3
Dn Slope=0.005
Boundary for River Rch & Prof#=WICKSONCRTRB36,Reach-1         , 6
Up Type= 0
Dn Type= 3
Dn Slope=0.005
Boundary for River Rch & Prof#=WICKSONCRTRB36,Reach-1         , 7
Up Type= 0
Dn Type= 3
Dn Slope=0.005
DSS Import GetInterval= 0
DSS Import GetPeak= 0
DSS Import FillOption= 0

--- WICKSONCREEKTRIB.g01 (geometry) ---

Geom Title=Existing Conditions
Program Version=4.10

River Reach=WICKSONCRTRB36  ,Reach-1
Reach XY= 30
      3551168.55     10266237.17      3551199.29     10266081.66
      3551160.23     10265761.35      3551365.96      10265480.1
      3551644.47     10264912.49      3551628.57     10264693.11
      3551462.19     10264506.36      3551535.39      10264205.3
      3551449.29     10264054.97      3551514.89     10263798.53
       3551354.6     10263527.02      3550938.87     10263190.39
       3550853.2     10263053.48       3550584.1     10263013.33
      3550447.38     10262923.27      3550341.04       10262754.
      3550360.75     10262575.81      3550313.87     10262406.53
      3550384.19     10262304.97      3550376.38     10262245.08
      3550313.87      10262133.1      3550209.71      10262135.7
      3550049.52     10262033.09      3550006.18     10261820.03
      3550039.95     10261795.17      3550179.84     10261868.35
      3550318.39     10261620.13      3550327.21     10261510.27
      3550434.82     10261497.02      3550832.11     10261311.64

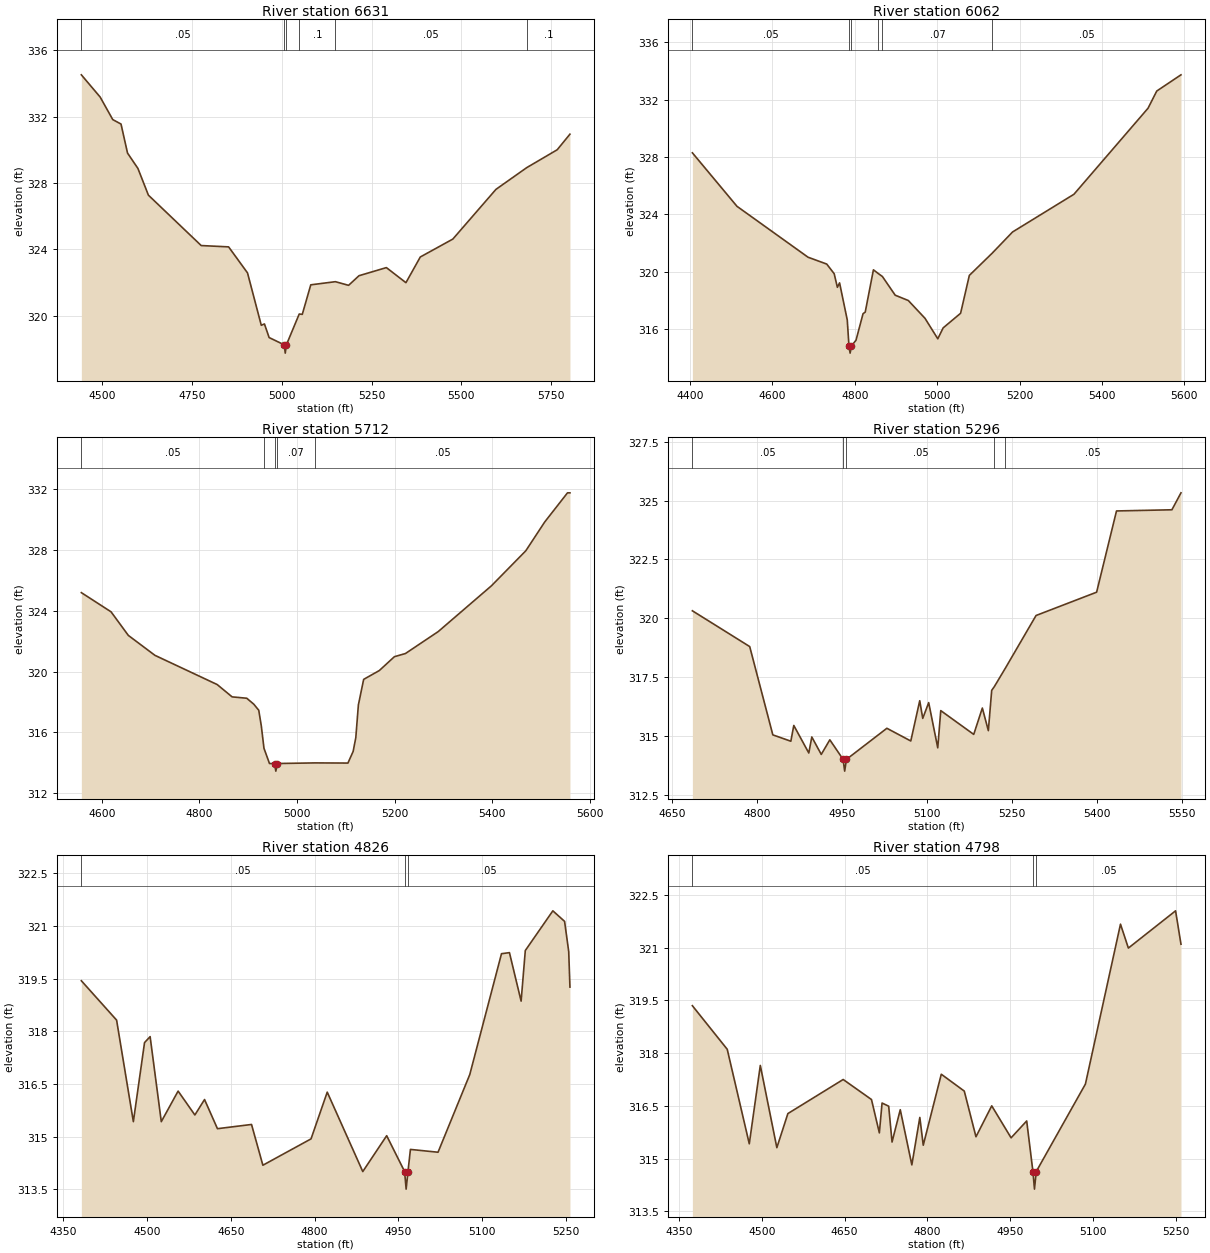
Type RM Length L Ch R = 1 ,6631    ,569,569,569
BEGIN DESCRIPTION:
UNT05134 IN WICK 12.0
END DESCRIPTION:
XS GIS Cut Line= 2
      3551702.48     10266348.38      3550452.46     10265813.64
#Sta/Elev= 30
  4442.5  334.53  4494.8  333.19  4529.9  331.83  4552.9  331.56    4571  329.81
    4600  328.88  4629.1  327.27    4776  324.23  4852.3  324.15  4904.9  322.58
  4943.2  319.42    4952   319.5    4965  318.68  5007.1  318.24  5009.9  317.74
  5013.1  318.24  5048.8   320.1  5057.3  320.08  5080.9  321.86  5149.4  322.05
  5186.1  321.83  5215.1  322.41  5291.3   322.9  5345.7  321.99  5385.7  323.54
  5476.2  324.62  5596.2  327.62  5681.8  328.93  5766.7  330.01  5802.1  330.95
#Mann= 6 ,-1 , 0
  4442.5     .05       0  5007.1     .03       0  5013.1     .05       0
  5048.8      .1       0  5149.4     .05       0  5681.8      .1       0
Bank Sta=5007.1,5013.1
XS Rating Curve= 0 ,0
Exp/Cntr=0.3,0.1

Type RM Length L Ch R = 1 ,6062    ,350,350,350
BEGIN DESCRIPTION:
UNT05134 IN WICK 11.0
END DESCRIPTION:
XS GIS Cut Line= 2
      3551827.45     10265792.81      3550706.52     10265404.13
#Sta/Elev= 30
  4405.7  328.29    4514  324.56  4686.5  321.01    4732  320.53    4750  319.86
  4757.8  318.91  4763.1  319.22  4781.8  316.63  4785.9  314.82  4788.7  314.32
  4791.9  314.82    4803  315.22  4820.1  317.07  4825.4  317.18  4845.3  320.13
  4856.7  319.88  4867.2  319.66  4898.2  318.36    4930  317.99  4970.5  316.75
  5001.6  315.32  5014.6  316.08    5057   317.1  5078.2  319.74    5134   321.3
  5183.2  322.77  5332.2   325.4  5512.1   331.4  5533.3   332.6  5592.1  333.73
#Mann= 6 ,-1 , 0
  4405.7     .05       0  4785.9     .07       0  4791.9     .05       0
  4856.7      .1       0  4867.2     .07       0    5134     .05       0
Bank Sta=4785.9,4791.9
XS Rating Curve= 0 ,0
Exp/Cntr=0.3,0.1

Type RM Length L Ch R = 1 ,5712    ,416,416,416
BEGIN DESCRIPTION:
UNT05134 IN WICK 10.0
END DESCRIPTION:
XS GIS Cut Line= 2
      3551851.75     10265459.47      3550917.72     10265098.36
#Sta/Elev= 30
    4558  325.19  4618.9  323.93  4654.3  322.38  4708.8  321.07  4836.4  319.15
    4867  318.34    4897  318.25  4911.4  317.86  4921.6  317.46  4926.9  316.42
  4932.3  314.96  4943.6  313.96  4953.9  313.96  4956.6  313.46  4959.9  313.96
  5036.6     314  5104.4  313.99  5115.1  314.76  5120.5  315.66  5125.8  317.81
  5136.6  319.49  5168.7  320.07  5199.6  320.98  5222.3  321.19  5289.4  322.63
  5398.5  325.64  5468.9  327.94  5507.6  329.83  5554.4  331.75  5559.4  331.75
#Mann= 5 ,-1 , 0
    4558     .05       0  4932.3     .07       0  4953.9     .07       0
  4959.9     .07       0  5036.6     .05       0
Bank Sta=4953.9,4959.9
XS Rating Curve= 0 ,0
Exp/Cntr=0.3,0.1

Type RM Length L Ch R = 1 ,5296    ,470,470,470
BEGIN DESCRIPTION:
UNT05134 IN WICK 9.0
END DESCRIPTION:
XS GIS Cut Line= 3
      3551928.16      10265032.4      3551254.54     10264810.17
      3551117.84     10264879.03
#Sta/Elev= 30
  4686.3  320.32  4787.5   318.8  4828.3  315.05  4860.1  314.78  4865.3  315.45
  4891.8  314.28  4897.1  314.96  4913.8  314.22  4928.9  314.84  4952.3  314.01
  4955.1  313.51  4958.3  314.01  5029.6  315.33  5071.8  314.79  5087.6   316.5
  5092.9  315.75  5103.4  316.42  5119.4   314.5  5124.7  316.08  5182.9  315.07
  5198.1  316.19  5208.7  315.23  5214.6  316.94  5219.3   317.1  5238.9  317.89
  5292.9  320.12  5399.8  321.11  5434.9  324.56  5532.7  324.61  5548.7  325.33
#Mann= 5 ,-1 , 0
  4686.3     .05       0  4952.3    .033       0  4958.3     .05       0
  5219.3     .07       0  5238.9     .05       0
Bank Sta=4952.3,4958.3
XS Rating Curve= 0 ,0
Exp/Cntr=0.3,0.1

Type RM Length L Ch R = 1 ,4826    ,28,28,28
BEGIN DESCRIPTION:
UNT05134 IN WICK 8.0
END DESCRIPTION:
XS GIS Cut Line= 6
      3552015.19     10264331.44      3551802.55     10264324.93
      3551678.85     10264346.63       3551602.9     10264398.71
      3551518.26     10264496.37      3551284.02     10264706.75
#Sta/Elev= 30
  4382.7  319.44  4445.8  318.32  4475.8  315.43  4495.8  317.68  4505.8  317.85
  4525.8  315.43  4555.9   316.3  4585.9  315.62  4603.2  316.06  4626.3  315.23
  4687.3  315.35  4707.6  314.19  4793.8  314.94  4822.8  316.27  4886.4  314.01
  4929.2  315.03  4961.3  314.01    4964  313.51  4967.3  314.01  4971.7  314.64
  5021.1  314.56  5077.9  316.77  5134.7  320.21  5148.9  320.24  5169.8  318.86
  5177.3   320.3  5226.6  321.43  5247.6  321.13    5255  320.27  5257.2  319.26
#Mann= 3 ,-1 , 0
  4382.7     .05       0  4961.3    .033       0  4967.3     .05       0
Bank Sta=4961.3,4967.3
XS Rating Curve= 0 ,0
Exp/Cntr=0.3,0.1

Type RM Length L Ch R = 1 ,4798    ,20,20,20
BEGIN DESCRIPTION:
Mapping XS 5b60eca3
END DESCRIPTION:
XS GIS Cut Line= 6
      3552015.25     10264314.08      3551785.19     10264307.57
      3551670.17     10264329.27      3551570.34     10264390.03
      3551481.37      10264494.2       3551265.7     10264679.67
#Sta/Elev= 30
  4373.8  319.35    4437  318.11    4477  315.42    4497  317.65    4527  315.31
    4547  316.28  4647.3  317.25  4698.6  316.68  4712.9  315.73  4717.8  316.58
  4729.8  316.49  4735.9  315.47  4750.8  316.39  4771.8  314.82  4786.3  316.17
  4792.5  315.38  4825.2   317.4  4866.9  316.92  4888.1  315.62  4916.7   316.5
  4951.8  315.59  4980.1  316.07  4991.4  314.63  4994.2  314.13  4997.4  314.63
  5086.6  317.12  5150.2  321.67  5164.5  320.99  5250.1  322.05  5259.9   321.1
#Mann= 3 ,-1 , 0
  4373.8     .05       0  4991.4    .033       0  4997.4     .05       0
Bank Sta=4991.4,4997.4
XS Rating Curve= 0 ,0
Exp/Cntr=0.3,0.1

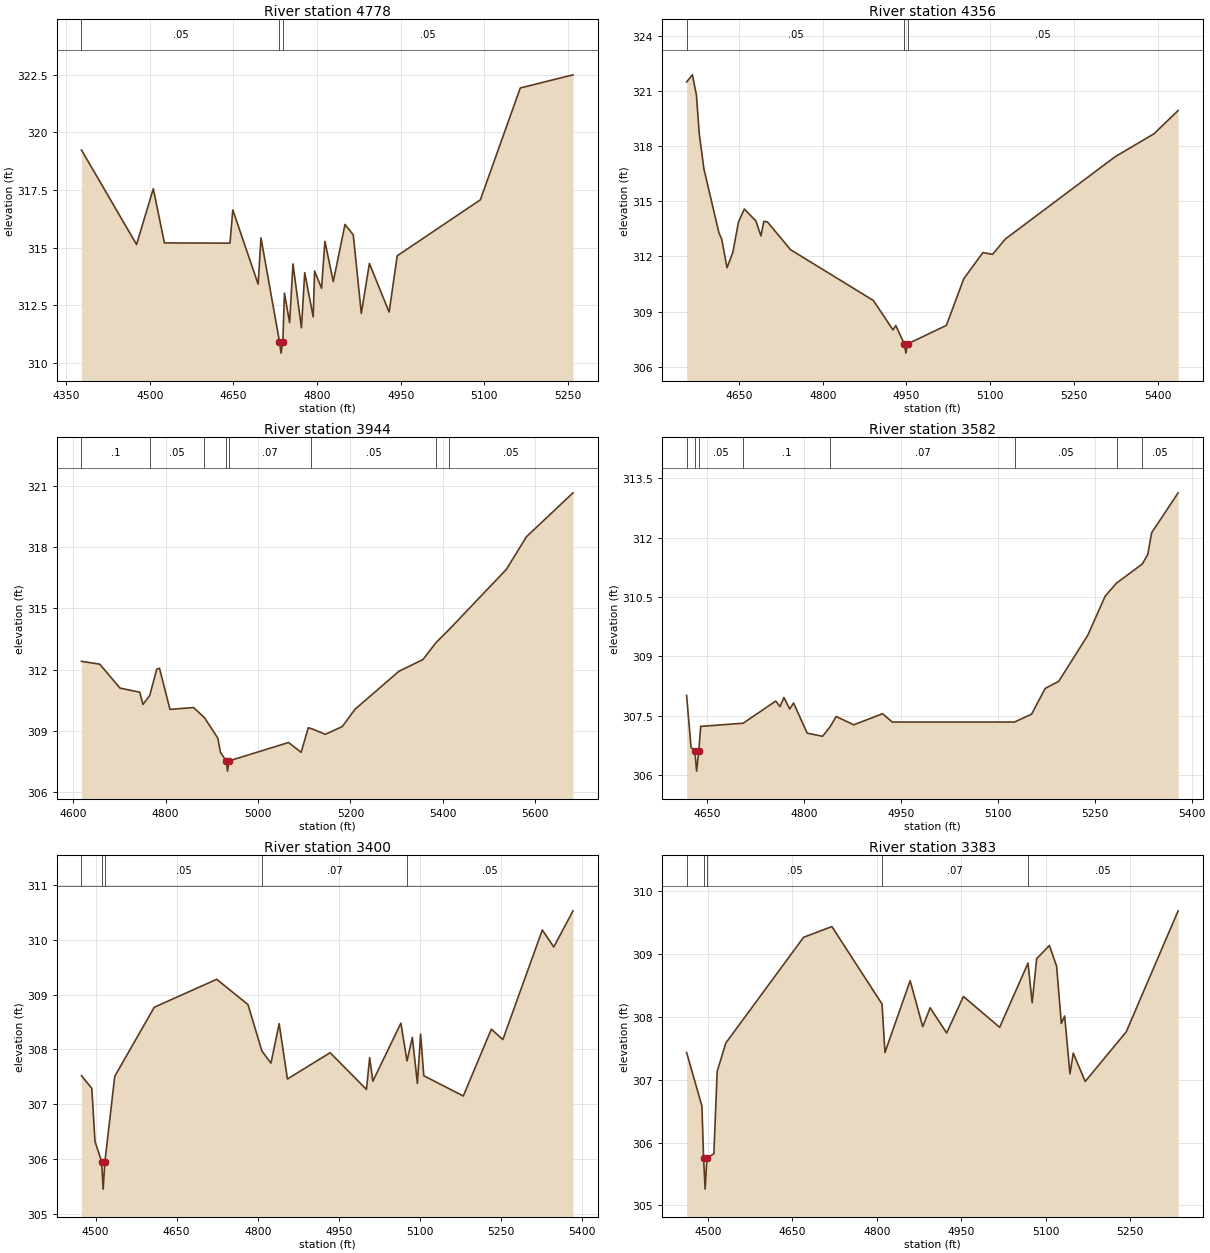
Type RM Length L Ch R = 1 ,4778    ,422,422,422
BEGIN DESCRIPTION:
Mapping XS 03babfc0
END DESCRIPTION:
XS GIS Cut Line= 6
       3552010.9     10264301.06      3551752.64     10264294.55
      3551657.15     10264314.08      3551542.13     10264390.03
      3551472.69     10264481.18      3551257.81     10264650.48
#Sta/Elev= 30
  4377.3  319.23  4476.1  315.13  4506.1  317.55  4526.1   315.2  4643.7  315.19
  4648.8  316.63  4694.2  313.41  4699.3  315.42  4732.5  310.92  4735.3  310.42
  4738.5  310.92  4741.4  313.02  4750.7  311.74  4756.7  314.29  4771.9  311.52
  4777.8  313.91    4793  311.99  4795.5  313.98    4808  313.23    4814  315.27
    4829  313.52    4850     316  4864.9  315.55  4879.3  312.14  4893.8  314.31
  4929.2   312.2  4943.7  314.64  5092.9  317.07  5164.5  321.92  5259.1  322.49
#Mann= 3 ,-1 , 0
  4377.3     .05       0  4732.5    .033       0  4738.5     .05       0
Bank Sta=4732.5,4738.5
XS Rating Curve= 0 ,0
Exp/Cntr=0.3,0.1

Type RM Length L Ch R = 1 ,4356    ,412,412,412
BEGIN DESCRIPTION:
UNT05134 IN WICK 7.0
END DESCRIPTION:
XS GIS Cut Line= 2
      3551892.12     10263991.64      3551040.79     10264216.43
#Sta/Elev= 30
  4556.1  321.48  4566.5  321.87  4573.7  320.77  4578.8  318.66  4587.1  316.76
  4613.9   313.3  4619.1  312.93  4628.5  311.39  4638.9  312.22    4649  313.87
  4659.5  314.58  4680.2  313.93  4689.3  313.12  4694.5  313.91  4700.9  313.88
  4742.3  312.37  4890.7  309.61  4925.8  308.01  4930.9  308.25  4946.1  307.25
  4948.9  306.75  4952.1  307.25  5021.5  308.26  5052.6  310.79  5086.8  312.21
  5104.3  312.12  5127.1  312.95  5323.3  317.41  5393.5  318.67  5436.6  319.93
#Mann= 3 ,-1 , 0
  4556.1     .05       0  4946.1     .03       0  4952.1     .05       0
Bank Sta=4946.1,4952.1
XS Rating Curve= 0 ,0
Exp/Cntr=0.3,0.1

Type RM Length L Ch R = 1 ,3944    ,362,362,362
BEGIN DESCRIPTION:
UNT05134 IN WICK 6.0
END DESCRIPTION:
XS GIS Cut Line= 2
        3551796.       10263522.       3550885.8     10264072.45
#Sta/Elev= 30
    4618  312.41  4657.6  312.27  4701.4   311.1  4744.1   310.9  4751.1   310.3
  4765.7  310.74  4780.9  312.03  4786.8  312.07  4809.5  310.06  4860.5  310.15
    4884  309.66  4912.9  308.66  4918.7  307.96  4931.2  307.54    4934  307.04
  4937.2  307.54  5066.1  308.44  5093.3  307.96  5108.8  309.16  5115.5  309.12
  5145.7  308.84  5182.5  309.22  5209.7  310.06  5304.8  311.92  5357.1   312.5
    5385  313.32  5413.4  313.96  5537.6  316.91  5580.8   318.5  5681.7  320.65
#Mann= 8 ,-1 , 0
    4618      .1       0  4765.7     .05       0    4884     .07       0
  4931.2     .07       0  4937.2     .07       0  5115.5     .05       0
    5385     .16       0  5413.4     .05       0
Bank Sta=4931.2,4937.2
XS Rating Curve= 0 ,0
Exp/Cntr=0.3,0.1

Type RM Length L Ch R = 1 ,3582    ,182,182,182
BEGIN DESCRIPTION:
Mapping XS 513c5706
END DESCRIPTION:
XS GIS Cut Line= 2
      3551468.59     10263117.46      3551041.84     10263747.18
#Sta/Elev= 30
  4618.4  308.01  4625.3   306.7  4631.2   306.6  4633.9   306.1  4637.2   306.6
  4640.2  307.23  4705.9  307.31  4756.3  307.87    4763  307.73    4769  307.96
    4778  307.67    4784  307.82    4805  307.06  4828.8  306.98  4840.5  307.22
  4849.9  307.48  4877.1  307.27  4921.7  307.55  4936.7  307.34  5125.9  307.34
  5152.4  307.54  5173.4  308.19  5194.4  308.37  5239.2  309.53  5266.2  310.52
  5283.8  310.85  5323.5  311.33  5332.1  311.57  5338.1  312.12  5379.1  313.13
#Mann= 8 ,-1 , 0
  4618.4     .05       0  4631.2     .07       0  4637.2     .05       0
  4705.9      .1       0  4840.5     .07       0  5125.9     .05       0
  5283.8     .16       0  5323.5     .05       0
Bank Sta=4631.2,4637.2
XS Rating Curve= 0 ,0
Exp/Cntr=0.3,0.1

Type RM Length L Ch R = 1 ,3400    ,17,17,17
BEGIN DESCRIPTION:
Mapping XS 91089035
END DESCRIPTION:
XS GIS Cut Line= 2
      3551399.58      10262864.2      3550917.68     10263635.89
#Sta/Elev= 30
  4473.8  307.52  4492.9  307.29  4498.8  306.32  4511.1  305.95  4513.9  305.45
  4517.1  305.95  4535.4  307.51  4608.5  308.77  4724.1  309.28  4781.9  308.82
  4807.8  307.97  4824.5  307.75  4839.7  308.47    4855  307.46    4934  307.94
  5001.3  307.27  5007.2  307.85  5013.1  307.42    5065  308.48  5076.3  307.79
  5086.2  308.22  5095.6  307.38  5101.5  308.28  5107.4  307.52  5180.5  307.15
  5232.4  308.37  5253.7  308.18  5326.8  310.18    5348  309.87  5383.6  310.53
#Mann= 5 ,-1 , 0
  4473.8     .05       0  4511.1     .07       0  4517.1     .05       0
  4807.8     .07       0  5076.3     .05       0
Bank Sta=4511.1,4517.1
XS Rating Curve= 0 ,0
Exp/Cntr=0.3,0.1

Type RM Length L Ch R = 1 ,3383    ,17,17,17
BEGIN DESCRIPTION:
Mapping XS 04428c21
END DESCRIPTION:
XS GIS Cut Line= 2
      3551393.07     10262845.96      3550927.85     10263584.08
#Sta/Elev= 30
  4462.5  307.43  4489.7  306.58  4492.6  305.76  4495.4  305.26  4498.6  305.76
  4510.9  305.82  4516.8  307.13  4532.1  307.58  4670.2  309.26  4720.4  309.43
  4809.4   308.2  4814.6  307.43  4859.3  308.57  4881.7  307.84  4894.8  308.14
  4924.1  307.74  4953.9  308.32  5018.2  307.83  5068.6  308.85  5075.9  308.22
  5083.9  308.92  5106.5  309.13  5119.3   308.8  5127.7  307.89  5133.6  308.01
    5143  307.09  5148.9  307.42  5170.1  306.97    5243  307.76    5335  309.68
#Mann= 5 ,-1 , 0
  4462.5     .05       0  4492.6     .07       0  4498.6     .05       0
  4809.4     .07       0  5068.6     .05       0
Bank Sta=4492.6,4498.6
XS Rating Curve= 0 ,0
Exp/Cntr=0.3,0.1

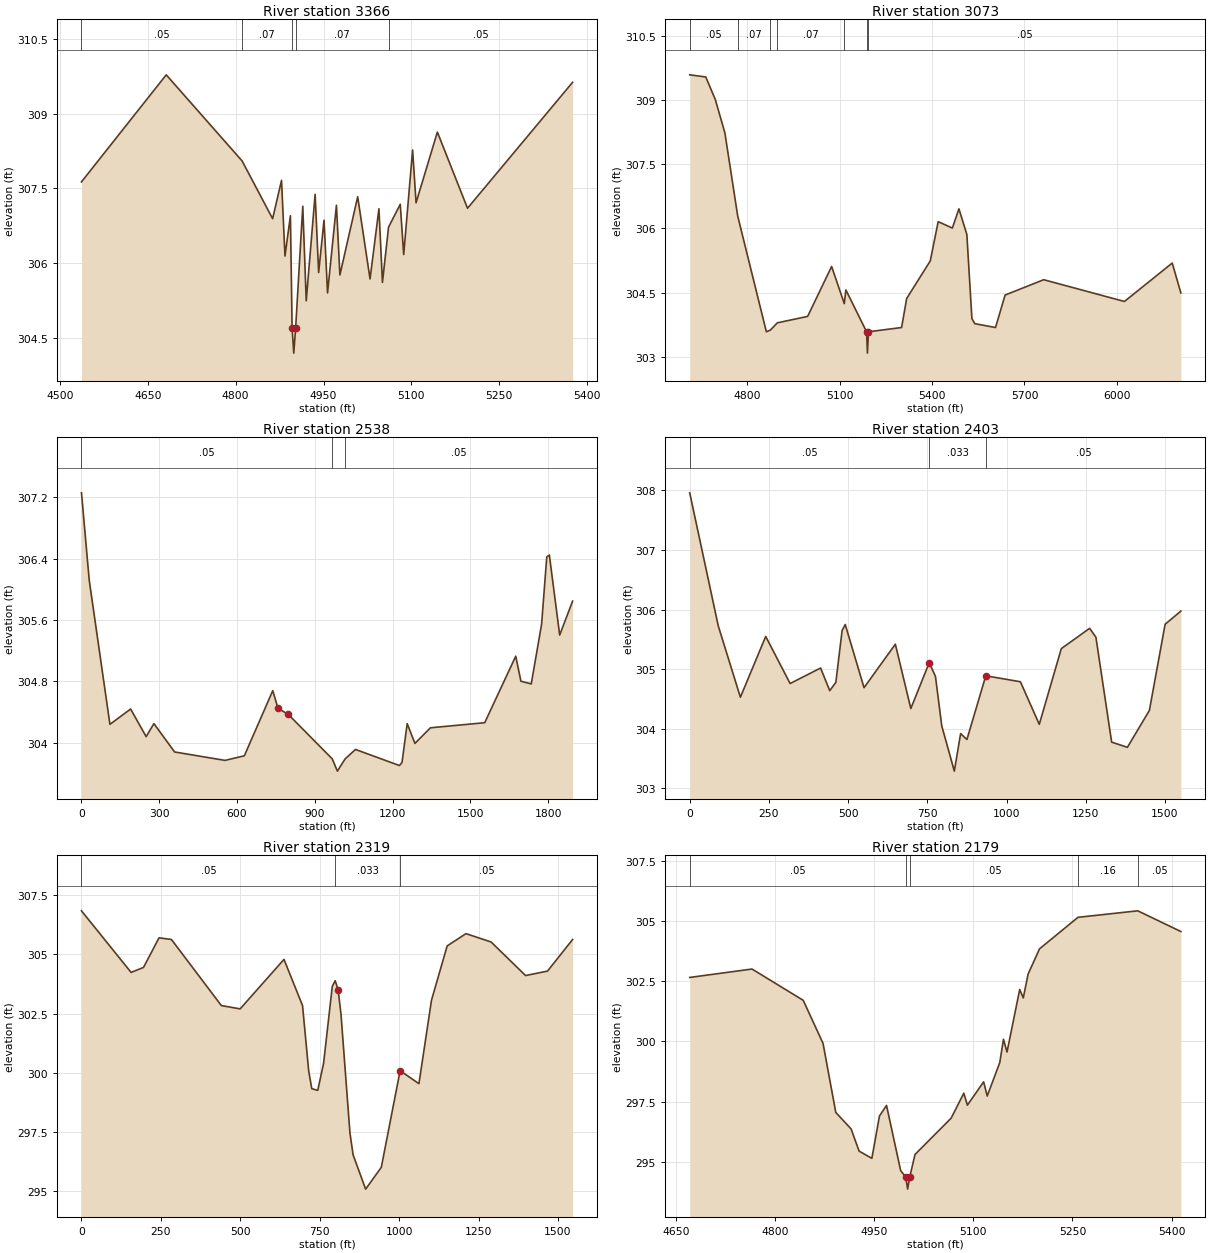
Type RM Length L Ch R = 1 ,3366    ,293,293,293
BEGIN DESCRIPTION:
Mapping XS aefe6fa0
END DESCRIPTION:
XS GIS Cut Line= 2
      3551343.19     10262901.39      3550889.78      10263607.2
#Sta/Elev= 30
  4536.6  307.63  4681.4  309.78    4811  308.05  4863.1  306.89  4878.3  307.66
  4884.2  306.14  4893.5  306.95  4896.4  304.69  4899.2  304.19  4902.4  304.69
  4914.6  307.14  4920.5  305.24  4935.7  307.38  4941.7  305.81  4950.9  306.86
  4956.9   305.4  4972.1  307.16    4978  305.76  5008.4  307.33  5029.5  305.68
  5044.7  307.09  5050.7  305.61  5061.1  306.72  5081.1  307.18    5087  306.17
  5102.2  308.27  5108.1  307.21  5144.5  308.63    5196   307.1  5375.5  309.63
#Mann= 5 ,-1 , 0
  4536.6     .05       0    4811     .07       0  4896.4     .07       0
  4902.4     .07       0  5061.1     .05       0
Bank Sta=4896.4,4902.4
XS Rating Curve= 0 ,0
Exp/Cntr=0.3,0.1

Type RM Length L Ch R = 1 ,3073    ,535,535,535
BEGIN DESCRIPTION:
UNT05134 IN WICK 4.0
END DESCRIPTION:
XS GIS Cut Line= 2
      3551247.07     10262969.69       3549741.7     10263496.25
#Sta/Elev= 30
    4613   309.6  4665.1  309.55  4696.2  309.02  4727.2  308.24  4768.9  306.29
  4861.9  303.58    4875  303.62  4897.6  303.79  4995.9  303.94  5073.8  305.11
  5114.9  304.24  5120.1  304.56  5187.3  303.58  5190.1  303.08  5193.3  303.58
    5301  303.68  5317.5  304.36  5394.1  305.24  5419.8  306.16  5465.8  306.01
  5487.2  306.46  5512.9  305.86  5529.3  303.89  5538.7  303.77    5606  303.68
  5637.1  304.44  5762.4   304.8  6024.6  304.29  6179.8  305.19  6207.8  304.49
#Mann= 7 ,-1 , 0
    4613     .05       0  4768.9     .07       0    4875     .05       0
  4897.6     .07       0  5114.9     .05       0  5187.3     .07       0
  5193.3     .05       0
Bank Sta=5187.3,5193.3
XS Rating Curve= 0 ,0
Exp/Cntr=0.3,0.1

Type RM Length L Ch R = 1 ,2538    ,135,135,135
XS GIS Cut Line= 5
      3551116.28    10262936.889     3550769.057    10262832.722
      3550585.03     10262891.75     3550508.641    10262853.556
     3549296.835    10263249.389
#Sta/Elev= 30
       0  307.26   29.93  306.12  109.75  304.24  189.57  304.44  249.43  304.08
  279.37  304.25  359.19  303.88  553.54  303.77  628.11  303.83  737.76  304.68
   757.7  304.45  797.57  304.37  967.03  303.79  986.97  303.63 1016.87  303.79
 1056.75303.9127  1226.2 303.703 1236.17 303.743 1256.11304.2498 1286.01303.9915
 1345.82304.1952 1555.15304.2616 1674.77 305.129 1694.71304.8028 1734.58304.7675
 1774.46305.5461 1794.39 306.424 1804.36306.4487 1844.23305.4048 1894.07305.8473
#Mann= 3 ,-1 , 0
       0     .05       0  967.03     .03       0 1016.87     .05       0
Bank Sta=757.7,797.57
XS Rating Curve= 0 ,0
Exp/Cntr=0.3,0.1

Type RM Length L Ch R = 1 ,2403    ,84,84,84
XS GIS Cut Line= 6
     3551154.474     10262895.22     3550956.557    10262777.167
     3550744.752    10262742.445     3550546.835    10262794.528
     3550470.446    10262738.972     3549706.557    10262933.417
#Sta/Elev= 30
       0  307.96   89.96  305.73  159.92  304.53  239.88  305.55  316.87  304.76
  413.11  305.02  441.99  304.64  461.23  304.78     481  305.65  490.88  305.75
  550.18  304.69  649.02  305.42  697.85  304.34  755.98  305.11   775.6  304.88
  795.46  304.05  835.17  303.29  855.03  303.92  874.89  303.82  934.47  304.89
1043.701304.78961103.279304.07511172.788305.34521262.156305.68611282.016305.5378
1331.665 303.7771381.314303.68941450.823 304.3081500.472305.75461550.121305.9748
#Mann= 3 ,-1 , 0
       0     .05       0  755.98    .033       0  934.47     .05       0
Bank Sta=755.98,934.47
XS Rating Curve= 0 ,0
Exp/Cntr=0.3,0.1

Type RM Length L Ch R = 1 ,2319    ,140,140,140
XS GIS Cut Line= 6
     3551227.391    10262773.695      3550928.78    10262666.056
     3550626.696    10262686.889     3550519.057    10262718.139
     3550432.252       10262673.     3549734.335    10262867.445
#Sta/Elev= 30
       0  306.84  156.24  304.24   195.3  304.45  244.13   305.7  283.19  305.63
  440.36  302.84   499.5   302.7  637.51  304.79  695.87  302.84  715.27  300.08
  724.98  299.33  743.82  299.26  762.11   300.4  789.54  303.65  798.69  303.89
  807.83  303.51  816.98  302.47  845.14  297.46  855.01  296.54   894.5  295.09
  943.86  296.01 1003.09  300.091062.324299.54241101.812 303.0641151.173305.3586
1210.405305.87621289.382 305.5251397.975304.10741467.079304.29571546.056305.6297
#Mann= 3 ,-1 , 0
       0     .05       0  798.69    .033       0 1003.09     .05       0
Bank Sta=807.83,1003.09
XS Rating Curve= 0 ,0
Exp/Cntr=0.3,0.1

Type RM Length L Ch R = 1 ,2179    ,558,558,558
BEGIN DESCRIPTION:
UNT05134 IN WICK 2.0
END DESCRIPTION:
XS GIS Cut Line= 2
      3550660.09     10262435.93      3549966.33     10262703.03
#Sta/Elev= 30
  4670.7  302.66    4765  303.01  4842.5  301.71  4872.5  299.92  4891.8  297.05
    4915  296.36  4927.1  295.44  4946.4  295.14  4957.9   296.9  4968.6  297.34
    4990  294.63  4997.7  294.36  5000.5  293.86  5003.7  294.36  5011.7   295.3
  5066.4  296.81  5085.6  297.85    5091  297.35  5115.6  298.32    5121  297.73
    5140  299.12  5145.6  300.09    5151  299.56  5170.2  302.16  5175.6  301.81
  5182.9   302.8  5200.2  303.85  5258.4  305.16  5348.9  305.43  5414.1  304.57
#Mann= 5 ,-1 , 0
  4670.7     .05       0  4997.7     .03       0  5003.7     .05       0
  5258.4     .16       0  5348.9     .05       0
Bank Sta=4997.7,5003.7
XS Rating Curve= 0 ,0
Exp/Cntr=0.3,0.1

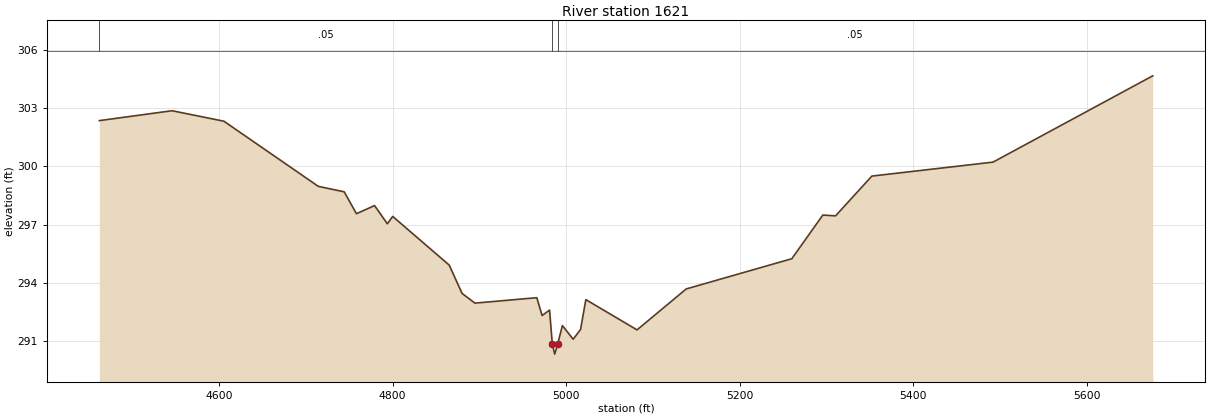
Type RM Length L Ch R = 1 ,1621    ,0,0,0
BEGIN DESCRIPTION:
UNT05134 IN WICK 1.0
END DESCRIPTION:
XS GIS Cut Line= 4
      3550700.91     10262098.75       3550429.2     10261992.84
      3549913.57     10262360.03      3549866.91     10262645.21
#Sta/Elev= 30
  4462.1  302.36  4545.9  302.87  4605.6  302.33  4714.4  298.97  4744.2  298.69
  4758.3  297.56  4779.2  297.98  4793.9  297.04  4800.1  297.42  4865.2  294.91
    4880  293.45  4894.8  292.95  4966.1  293.23  4972.2  292.31  4980.8  292.59
    4984  290.82  4986.7  290.32    4990  290.82  4995.6  291.79    5008  291.09
  5016.5  291.59  5022.6  293.13  5081.6  291.57  5138.2  293.68  5259.9  295.24
  5295.6  297.49  5310.3  297.45  5352.1   299.5  5491.7  300.22  5675.7  304.67
#Mann= 3 ,-1 , 0
  4462.1     .05       0    4984    .035       0    4990     .05       0
Bank Sta=4984,4990
XS Rating Curve= 0 ,0
Exp/Cntr=0.3,0.1

Chan Stop Cuts=-1
Use User Specified Reach Order=0
Composite Channel Slope=5