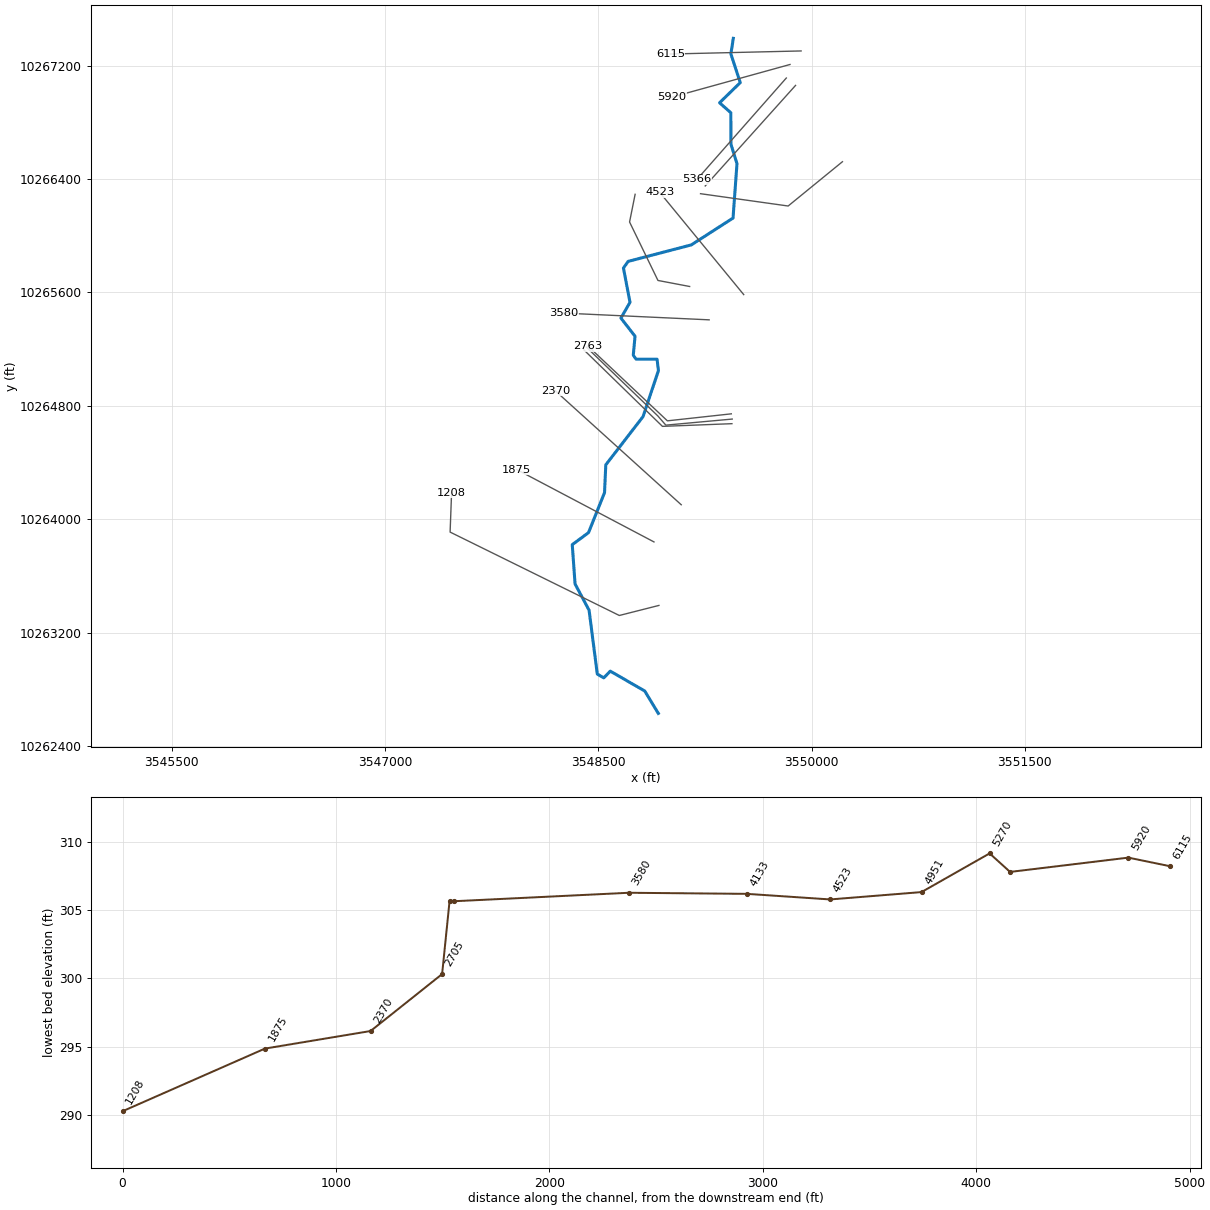
--- WICKSONCREEKTRIB.prj (project) ---

Proj Title=WICKSON CREEK TRIB 37
Current Plan=p01
Default Exp/Contr=0.3,0.1
English Units
Geom File=g01
Flow File=f01
Plan File=p01
Y Axis Title=Elevation
X Axis Title(PF)=Main Channel Distance
X Axis Title(XS)=Station
BEGIN DESCRIPTION:
UNT05130 IN WICK
END DESCRIPTION:
DSS Export Rating Curves= 0
DSS Export Rating Curve Sorted= 0
DSS Export Volume Flow Curves= 0
DXF OffsetX= 0
DXF OffsetY= 0
DXF ScaleX= 1
DXF ScaleY= 10

--- WICKSONCREEKTRIB.p01 (plan) ---

Plan Title=Multiple Run
Short Identifier=Multiple
Geom File=g01
Flow File=f01
Subcritical Flow
K Sum by GR= 0
Std Step Tol= 0.01
Critical Tol= 0.01
Num of Std Step Trials= 20
Max Error Tol= 0.3
Flow Tol Ratio= 0.001
Split Flow NTrial= 30
Split Flow Tol= 0.02
Split Flow Ratio= 0.02
Log Output Level= 0
Friction Slope Method= 1
Unsteady Friction Slope Method= 2
Unsteady Bridges Friction Slope Method= 1
Parabolic Critical Depth
Global Vel Dist=  1 , 1 , 1
Global Log Level= 0
CheckData=True
Encroach Param= -1, 0, 0, 0
BEGIN DESCRIPTION:
Multiple Run
END DESCRIPTION:

--- WICKSONCREEKTRIB.f01 (steady flow) ---

Flow Title=Multiple
Program Version=4.10
Number of Profiles= 7
Profile Names=10-year,25-year,50-year,1pct_min,100-year,1pct_plu,500-year
River Rch & RM=UNT05130 IN WICK,Reach-1         ,6115
     431     570     681     597     807    1092    1137
River Rch & RM=UNT05130 IN WICK,Reach-1         ,3580
     540     723     872     770    1041    1408    1489
River Rch & RM=WICKSONCRTRB37,Reach-1         ,6115
     431     570     681     597     807    1092    1137
River Rch & RM=WICKSONCRTRB37,Reach-1         ,3580
     540     723     872     770    1041    1408    1489
Boundary for River Rch & Prof#=WICKSONCRTRB37,Reach-1         , 1
Up Type= 0
Dn Type= 3
Dn Slope=0.005
Boundary for River Rch & Prof#=WICKSONCRTRB37,Reach-1         , 2
Up Type= 0
Dn Type= 3
Dn Slope=0.005
Boundary for River Rch & Prof#=WICKSONCRTRB37,Reach-1         , 3
Up Type= 0
Dn Type= 3
Dn Slope=0.005
Boundary for River Rch & Prof#=WICKSONCRTRB37,Reach-1         , 4
Up Type= 0
Dn Type= 3
Dn Slope=0.005
Boundary for River Rch & Prof#=WICKSONCRTRB37,Reach-1         , 5
Up Type= 0
Dn Type= 3
Dn Slope=0.005
Boundary for River Rch & Prof#=WICKSONCRTRB37,Reach-1         , 6
Up Type= 0
Dn Type= 3
Dn Slope=0.005
Boundary for River Rch & Prof#=WICKSONCRTRB37,Reach-1         , 7
Up Type= 0
Dn Type= 3
Dn Slope=0.005
DSS Import GetInterval= 0
DSS Import GetPeak= 0
DSS Import FillOption= 0

--- WICKSONCREEKTRIB.g01 (geometry) ---

Geom Title=Existing Conditions
Program Version=4.10

River Reach=WICKSONCRTRB37  ,Reach-1
Reach XY= 30
      3549449.48     10267392.01       3549432.1     10267282.56
      3549498.12     10267079.66      3549352.72     10266937.51
      3549432.12     10266866.98      3549432.31     10266646.42
      3549475.11     10266507.82      3549447.34     10266124.14
      3549153.93     10265934.91      3548709.49     10265818.59
       3548676.5     10265771.71      3548722.67      10265529.9
      3548658.82     10265418.51      3548758.13     10265290.74
      3548745.63     10265156.71      3548765.77     10265128.93
      3548912.99     10265128.93      3548922.71     10265048.38
      3548814.64     10264724.24       3548552.4     10264383.62
      3548543.54     10264187.79      3548430.78     10263905.23
      3548316.46      10263820.6      3548336.25     10263543.08
      3548434.86     10263358.01       3548492.5     10262907.85
      3548538.34     10262880.93      3548583.82     10262928.34
      3548826.18     10262788.41      3548921.77     10262630.45

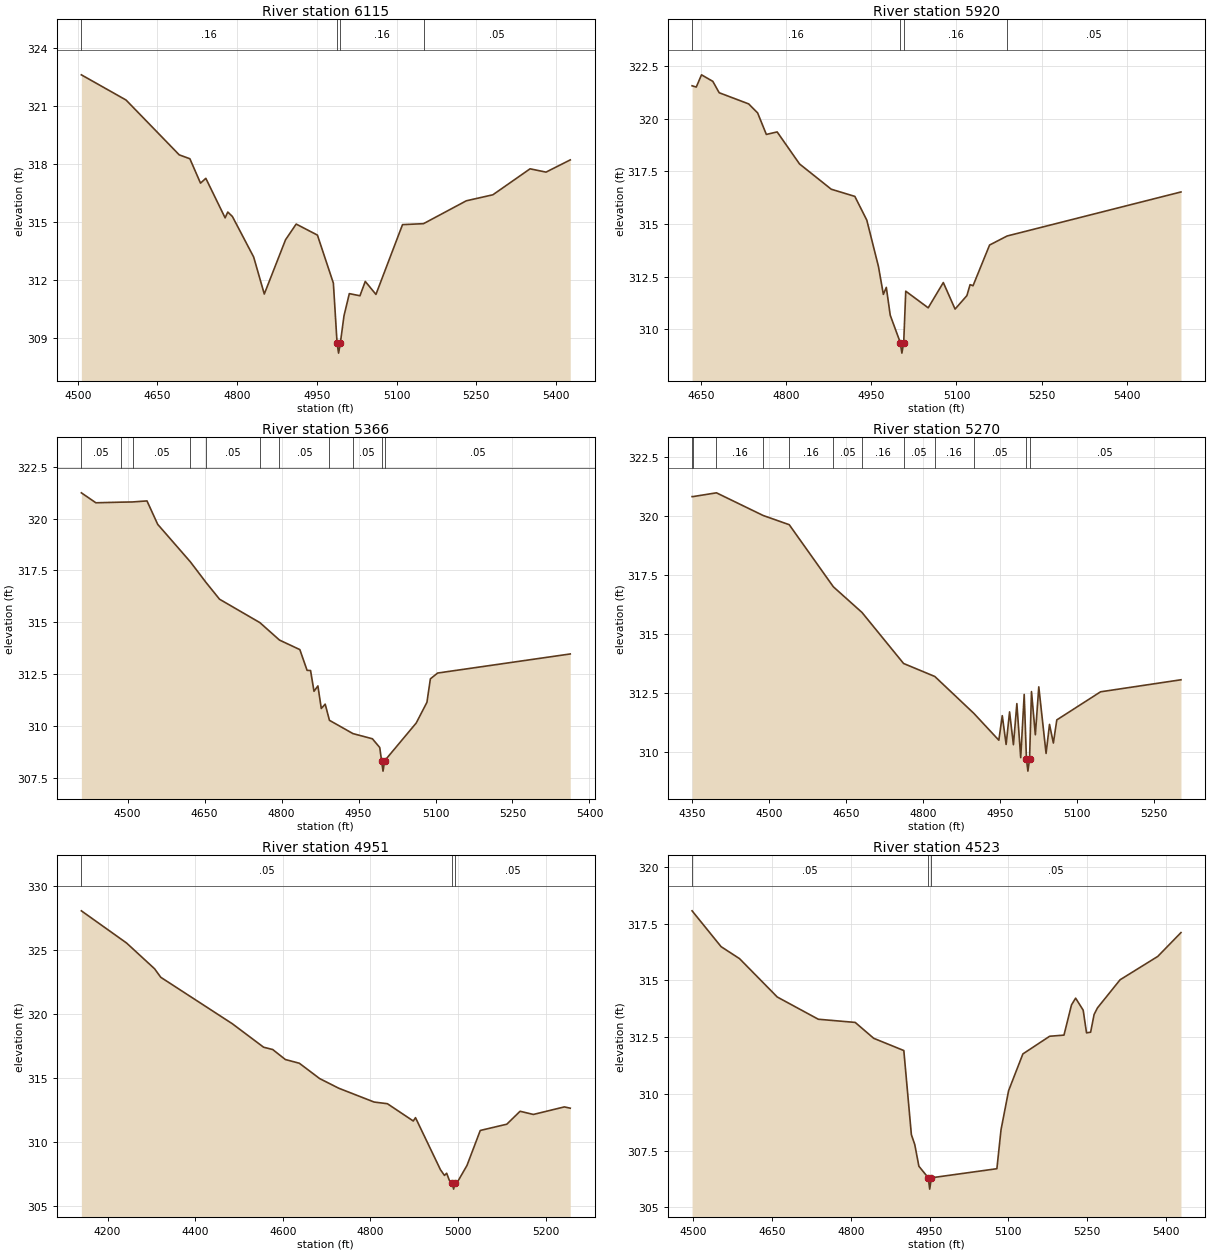
Type RM Length L Ch R = 1 ,6115    ,195,195,195
BEGIN DESCRIPTION:
UNT05130 IN WICK 12.0
END DESCRIPTION:
XS GIS Cut Line= 2
      3549926.21     10267303.05      3549006.56     10267281.36
#Sta/Elev= 30
  4506.8   322.6  4590.9   321.3    4691  318.47    4711  318.27    4731  317.01
    4741  317.26  4777.3  315.22  4782.3  315.52    4791  315.29    4831   313.2
    4851  311.29    4891  314.09    4911   314.9    4951  314.33    4981  311.85
    4988  308.74  4990.8  308.24    4994  308.74    5001  310.17    5011  311.31
    5031   311.2    5041  311.94  5061.1  311.27  5111.1  314.87  5150.6  314.92
  5231.1   316.1  5281.1  316.41  5351.1  317.75  5381.1  317.58  5426.7  318.21
#Mann= 4 ,-1 , 0
  4506.8     .16       0    4988     .07       0    4994     .16       0
  5150.6     .05       0
Bank Sta=4988,4994
XS Rating Curve= 0 ,0
Exp/Cntr=0.3,0.1

Type RM Length L Ch R = 1 ,5920    ,554,554,554
BEGIN DESCRIPTION:
UNT05130 IN WICK 11.0
END DESCRIPTION:
XS GIS Cut Line= 2
      3549848.07     10267207.56      3549019.09     10266977.53
#Sta/Elev= 30
  4634.8  321.56  4642.2   321.5  4651.4  322.08  4671.3  321.77  4682.5  321.23
  4734.4   320.7  4750.2  320.27  4765.5  319.25  4784.5  319.37  4823.9  317.85
  4879.7  316.65  4921.2  316.31  4942.3  315.18  4962.7  312.99  4971.4  311.66
  4976.6  311.99  4983.5  310.67  5001.2  309.37    5004  308.87  5007.2  309.37
  5010.8  311.81  5050.3  311.02  5076.9  312.22  5097.6  310.96  5118.4   311.6
    5124  312.12  5129.2  312.07  5158.3     314  5189.2  314.43  5495.1  316.52
#Mann= 4 ,-1 , 0
  4634.8     .16       0  5001.2     .07       0  5007.2     .16       0
  5189.2     .05       0
Bank Sta=5001.2,5007.2
XS Rating Curve= 0 ,0
Exp/Cntr=0.3,0.1

Type RM Length L Ch R = 1 ,5366    ,96,96,96
BEGIN DESCRIPTION:
Mapping XS 1c07caff
END DESCRIPTION:
XS GIS Cut Line= 2
      3549822.08     10267112.11      3549193.19     10266396.34
#Sta/Elev= 30
  4409.8  321.24  4438.1  320.76  4486.9  320.79  4509.5   320.8  4537.7  320.85
  4558.6  319.72  4622.3  317.91  4652.7  316.92  4679.1  316.11  4757.8  314.98
  4795.9  314.14  4835.6  313.68  4849.7  312.68  4856.5  312.67  4863.2  311.67
  4870.8  311.93  4877.4  310.84    4885  311.05  4893.3  310.27  4939.1  309.63
    4977  309.38  4991.3  308.96  4994.9  308.32  4997.7  307.82  5000.9  308.32
  5062.4  310.14  5083.3  311.14    5090  312.27  5104.2  312.55  5362.6  313.47
#Mann= 11 ,-1 , 0
  4409.8     .05       0  4486.9     .16       0  4509.5     .05       0
  4622.3     .16       0  4652.7     .05       0  4757.8     .16       0
  4795.9     .05       0  4893.3     .16       0  4939.1     .05       0
  4994.9     .04       0  5000.9     .05       0
Bank Sta=4994.9,5000.9
XS Rating Curve= 0 ,0
Exp/Cntr=0.3,0.1

Type RM Length L Ch R = 1 ,5270    ,319,319,319
BEGIN DESCRIPTION:
Mapping XS 6cd7a867
END DESCRIPTION:
XS GIS Cut Line= 2
      3549887.17     10267060.02       3549251.9     10266350.84
#Sta/Elev= 30
  4350.7  320.81  4352.4  320.81  4398.2  320.97  4489.1  320.01  4539.9  319.62
  4625.8  316.99  4681.7   315.9  4762.6  313.74  4823.4  313.19  4899.3  311.63
  4948.1  310.49  4954.8  311.53  4962.3  310.31    4969  311.69  4976.5   310.3
  4983.2  312.04  4990.7  309.75  4997.5  312.43  5001.9  309.68  5004.7  309.18
  5007.9  309.68  5011.7  312.55  5019.2  310.72  5025.9  312.75  5040.1  309.93
  5046.8  311.16  5054.3  310.37    5061  311.35  5146.2  312.54  5302.8  313.05
#Mann= 12 ,-1 , 0
  4350.7     .16       0  4352.4     .05       0  4398.2     .16       0
  4489.1     .05       0  4539.9     .16       0  4625.8     .05       0
  4681.7     .16       0  4762.6     .05       0  4823.4     .16       0
  4899.3     .05       0  5001.9     .03       0  5007.9     .05       0
Bank Sta=5001.9,5007.9
XS Rating Curve= 0 ,0
Exp/Cntr=0.3,0.1

Type RM Length L Ch R = 1 ,4951    ,428,428,428
BEGIN DESCRIPTION:
UNT05130 IN WICK 10.0
END DESCRIPTION:
XS GIS Cut Line= 3
      3550217.01      10266521.8      3549835.07      10266209.3
      3549218.74     10266296.11
#Sta/Elev= 30
  4140.1  328.07  4243.2  325.56  4307.1  323.55  4321.4  322.88  4484.4  319.26
  4556.1  317.42  4576.9  317.24  4605.7  316.46  4637.6  316.17  4684.1  314.97
  4727.5  314.22  4808.3  313.14  4838.6  313.01  4897.7  311.66  4902.8  311.92
  4959.7  307.86  4968.9  307.41  4973.9  307.58  4979.9  307.04    4987  306.84
  4989.8  306.34    4993  306.84  5000.1  306.99  5020.3  308.19  5050.6  310.92
  5111.2  311.41  5141.5  312.42  5171.8  312.17  5242.5  312.76    5256  312.66
#Mann= 3 ,-1 , 0
  4140.1     .05       0    4987    .035       0    4993     .05       0
Bank Sta=4987,4993
XS Rating Curve= 0 ,0
Exp/Cntr=0.3,0.1

Type RM Length L Ch R = 1 ,4523    ,390,390,390
BEGIN DESCRIPTION:
UNT05130 IN WICK 9.0
END DESCRIPTION:
XS GIS Cut Line= 2
      3549522.57     10265584.31       3548932.3     10266304.79
#Sta/Elev= 30
  4497.6  318.07  4552.9  316.49  4588.1  315.96  4659.9  314.27  4738.1  313.29
  4808.4  313.15  4843.6  312.45    4901  311.91  4915.4   308.2  4921.8  307.77
  4929.7  306.81  4947.6   306.3  4950.3   305.8  4953.6   306.3  5078.3   306.7
  5086.2  308.42  5100.6  310.14  5127.8  311.76  5178.8  312.54  5206.1  312.59
  5220.4  313.92  5228.3  314.22  5242.7  313.69  5249.1  312.69  5256.9  312.72
  5263.5   313.5  5269.9  313.79    5313  315.03  5384.8  316.06    5429  317.11
#Mann= 3 ,-1 , 0
  4497.6     .05       0  4947.6     .03       0  4953.6     .05       0
Bank Sta=4947.6,4953.6
XS Rating Curve= 0 ,0
Exp/Cntr=0.3,0.1

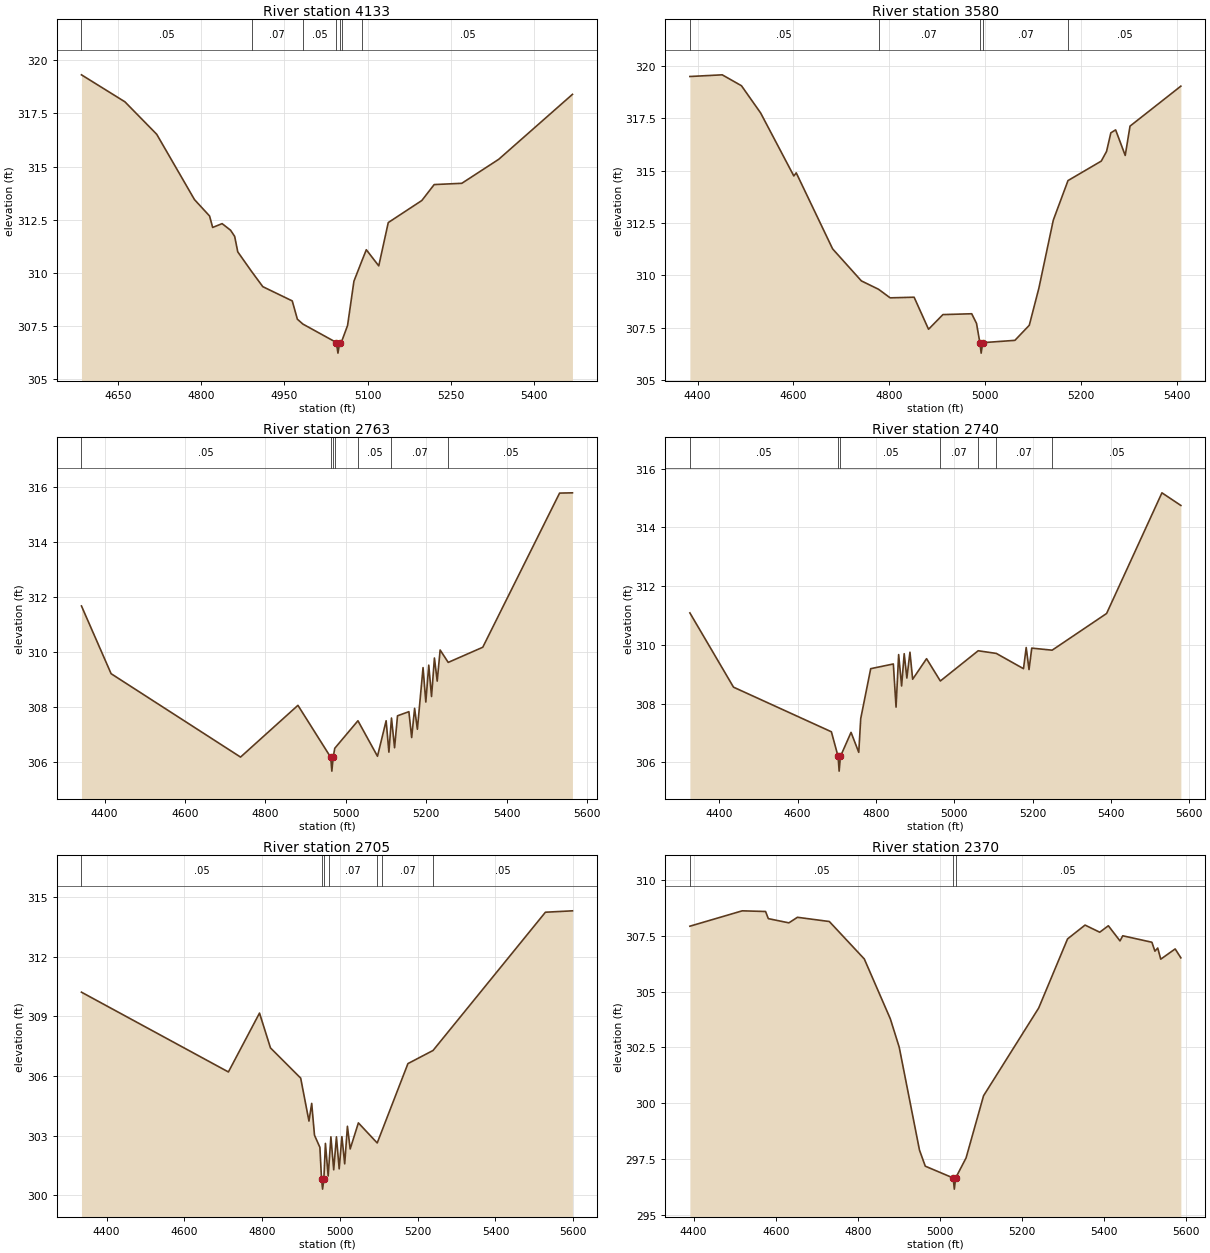
Type RM Length L Ch R = 1 ,4133    ,553,553,553
BEGIN DESCRIPTION:
UNT05130 IN WICK 8.0
END DESCRIPTION:
XS GIS Cut Line= 4
      3549142.11     10265641.64      3548919.27     10265684.13
      3548719.62     10266096.46      3548758.69     10266291.82
#Sta/Elev= 30
  4584.4  319.32  4662.6  318.05  4719.9  316.52    4788  313.44  4815.1  312.67
  4820.7  312.13  4837.7  312.31  4852.9     312  4860.3  311.71  4865.9  310.98
  4890.7  310.06    4911  309.34    4964  308.67  4973.2  307.81  4983.1  307.58
  5043.5  306.71  5046.3  306.21  5049.5  306.71  5053.7  306.81  5063.6  307.51
  5075.1   309.6  5090.2  310.61  5097.4  311.08  5119.8  310.32  5136.9  312.36
  5197.4   313.4  5219.6  314.15  5269.4  314.21  5335.8  315.34  5468.6   318.4
#Mann= 7 ,-1 , 0
  4584.4     .05       0  4890.7     .07       0  4983.1     .05       0
  5043.5     .03       0  5049.5     .05       0  5053.7      .1       0
  5090.2     .05       0
Bank Sta=5043.5,5049.5
XS Rating Curve= 0 ,0
Exp/Cntr=0.3,0.1

Type RM Length L Ch R = 1 ,3580    ,817,817,817
BEGIN DESCRIPTION:
UNT05130 IN WICK 6.0
END DESCRIPTION:
XS GIS Cut Line= 2
      3549279.54     10265406.35      3548256.15     10265454.05
#Sta/Elev= 30
  4383.9   319.5  4451.4  319.58  4491.5  319.06  4531.5  317.76  4600.8  314.75
  4605.8   314.9  4681.7  311.27  4741.7  309.74  4777.5  309.34  4801.8  308.93
  4851.8  308.96  4881.9  307.43  4911.9  308.13    4972  308.17    4982  307.71
    4989  306.79  4991.7  306.29    4995  306.79  5062.1   306.9  5092.1  307.62
  5112.1  309.39  5142.2  312.64  5172.9  314.53  5242.3  315.46  5253.3  315.92
  5262.3  316.81  5272.3  316.95  5292.3  315.73  5302.3  317.13  5408.4  319.04
#Mann= 5 ,-1 , 0
  4383.9     .05       0  4777.5     .07       0    4989     .07       0
    4995     .07       0  5172.9     .05       0
Bank Sta=4989,4995
XS Rating Curve= 0 ,0
Exp/Cntr=0.3,0.1

Type RM Length L Ch R = 1 ,2763    ,23,23,23
BEGIN DESCRIPTION:
UNT05130 IN WICK 5.0
END DESCRIPTION:
XS GIS Cut Line= 3
      3549435.33     10264743.35      3548985.53     10264693.97
      3548426.73     10265221.41
#Sta/Elev= 30
  4342.6  311.67  4416.3  309.21  4738.2  306.18  4880.9  308.06  4962.5  306.17
  4965.2  305.67  4968.5  306.17  4972.5   306.5  5030.1   307.5  5078.7  306.21
  5100.2   307.5  5107.1  306.36  5113.5   307.6  5121.2  306.52  5128.5  307.68
  5156.8  307.83  5163.7  306.89    5171  307.95  5177.9  307.19    5192  309.43
  5198.9  308.18  5206.2  309.52  5213.1  308.38  5220.3  309.78  5227.2  308.94
  5234.5  310.07  5254.6  309.62  5340.5  310.17  5531.5  315.77  5563.5  315.78
#Mann= 7 ,-1 , 0
  4342.6     .05       0  4962.5     .07       0  4968.5     .05       0
  4972.5     .07       0  5030.1     .05       0  5113.5     .07       0
  5254.6     .05       0
Bank Sta=4962.5,4968.5
XS Rating Curve= 0 ,0
Exp/Cntr=0.3,0.1

Type RM Length L Ch R = 1 ,2740    ,35,35,35
BEGIN DESCRIPTION:
Mapping XS fd605a4a
END DESCRIPTION:
XS GIS Cut Line= 4
       3549441.9     10264706.47      3548974.68     10264663.59
      3548918.26     10264728.69      3548415.93      10265213.7
#Sta/Elev= 30
  4324.8  311.09  4436.2  308.56  4686.1  307.04  4703.2   306.2  4705.9   305.7
  4709.2   306.2  4736.3  307.02    4756  306.34    4761  307.49  4786.5  309.19
  4844.3  309.35  4851.2  307.88  4857.8  309.67  4865.4   308.6    4872   309.7
  4878.8  308.87  4886.7  309.75  4893.6  308.83  4929.1  309.53  4964.3  308.77
  5060.9   309.8  5107.1  309.71  5176.6  309.19  5183.5  309.91  5190.7  309.16
  5197.7  309.89  5249.8  309.82  5388.8  311.07  5530.1  315.18  5578.4  314.75
#Mann= 7 ,-1 , 0
  4324.8     .05       0  4703.2     .07       0  4709.2     .05       0
  4964.3     .07       0  5060.9     .05       0  5107.1     .07       0
  5249.8     .05       0
Bank Sta=4703.2,4709.2
XS Rating Curve= 0 ,0
Exp/Cntr=0.3,0.1

Type RM Length L Ch R = 1 ,2705    ,335,335,335
BEGIN DESCRIPTION:
UNT05130 IN WICK 4.0
END DESCRIPTION:
XS GIS Cut Line= 3
      3549439.69     10264673.91      3548950.81     10264654.91
      3548397.43     10265195.27
#Sta/Elev= 30
  4335.2  310.22  4713.1  306.21  4793.1  309.17  4821.3  307.42    4899   305.9
  4920.3  303.74  4927.3  304.63  4934.5  303.03  4948.4  302.42  4952.6  300.82
  4955.3  300.32  4958.6  300.82  4962.6  302.62  4969.7  300.98  4972.4  301.74
  4976.7  302.95  4983.9  301.29  4990.9  302.95    4998  301.34    5005  302.96
  5012.2  301.59  5019.2  303.48  5026.3  302.34  5047.4  303.65  5095.8  302.64
  5107.5  303.23  5174.8  306.63  5239.4  307.29  5528.4  314.24  5597.9  314.31
#Mann= 7 ,-1 , 0
  4335.2     .05       0  4952.6     .07       0  4958.6     .05       0
  4972.4     .07       0  5095.8     .05       0  5107.5     .07       0
  5239.4     .05       0
Bank Sta=4952.6,4958.6
XS Rating Curve= 0 ,0
Exp/Cntr=0.3,0.1

Type RM Length L Ch R = 1 ,2370    ,495,495,495
BEGIN DESCRIPTION:
UNT05130 IN WICK 3.0
END DESCRIPTION:
XS GIS Cut Line= 2
      3549082.93     10264102.07      3548196.98      10264906.1
#Sta/Elev= 30
  4390.9  307.94  4518.5  308.63  4575.3   308.6    4582  308.28  4632.1  308.09
    4653  308.34  4730.7  308.15  4815.9  306.47  4879.4  303.78    4901  302.51
  4950.4  297.89  4964.5  297.17  5032.5  296.64  5035.3  296.14  5038.5  296.64
  5063.9  297.54  5106.5  300.33  5240.9  304.27  5311.2  307.37  5353.8  307.99
  5389.6  307.67  5410.6  307.96    5439  307.28  5445.7  307.51  5516.7  307.22
  5524.1  306.82  5530.9  306.96  5538.3  306.46  5573.4  306.92  5587.3  306.52
#Mann= 3 ,-1 , 0
  4390.9     .05       0  5032.5    .035       0  5038.5     .05       0
Bank Sta=5032.5,5038.5
XS Rating Curve= 0 ,0
Exp/Cntr=0.3,0.1

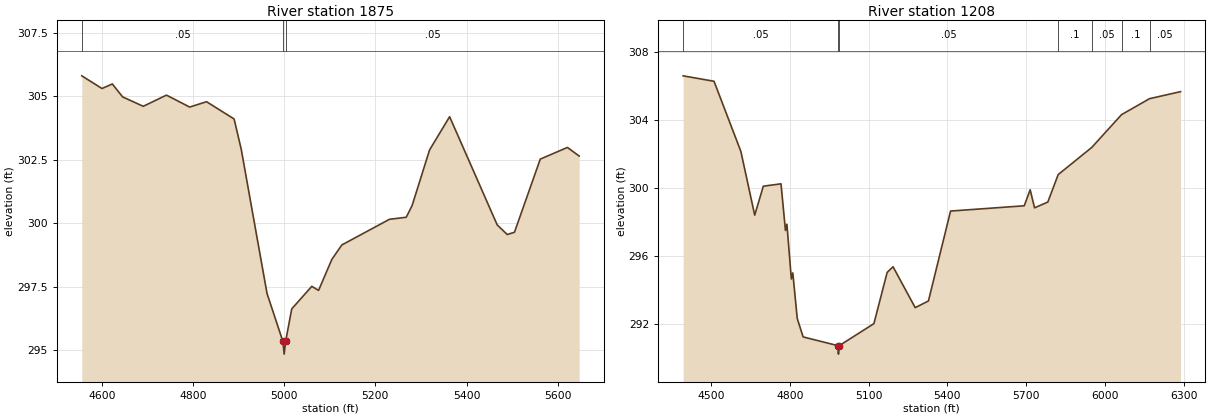
Type RM Length L Ch R = 1 ,1875    ,667,667,667
BEGIN DESCRIPTION:
UNT05130 IN WICK 2.0
END DESCRIPTION:
XS GIS Cut Line= 2
      3548891.34     10263839.81      3547926.61     10264349.93
#Sta/Elev= 30
  4555.9  305.81  4600.3  305.31  4622.9  305.49  4645.5  304.98  4690.8  304.61
  4741.7  305.05  4792.6  304.58  4829.7  304.79  4890.1  304.11  4905.7  302.92
  4962.3  297.24  4997.1  295.35  4999.9  294.85  5003.1  295.35  5016.5  296.63
  5060.5  297.52  5075.4  297.36  5104.5  298.58  5126.5  299.15  5230.9  300.16
  5267.7  300.24  5280.6   300.7  5318.9  302.89  5362.9   304.2  5467.3  299.94
  5489.3  299.56  5505.2  299.65  5561.8  302.53  5621.4  302.99  5647.2  302.65
#Mann= 3 ,-1 , 0
  4555.9     .05       0  4997.1    .035       0  5003.1     .05       0
Bank Sta=4997.1,5003.1
XS Rating Curve= 0 ,0
Exp/Cntr=0.3,0.1

Type RM Length L Ch R = 1 ,1208    ,0,0,0
BEGIN DESCRIPTION:
UNT05130 IN WICK 1.0
END DESCRIPTION:
XS GIS Cut Line= 4
       3548926.1     10263391.89      3548647.51     10263320.99
      3547457.32     10263909.25      3547467.73     10264186.86
#Sta/Elev= 30
  4394.3  306.59  4511.9  306.27  4614.1  302.15  4666.7  298.41  4699.5  300.11
  4766.8  300.25  4783.7  297.51  4789.3  297.88  4806.1  294.66  4811.7  295.02
  4828.6  292.34    4851  291.26  4982.7  290.75  4985.4  290.25  4988.7  290.75
  5120.3  292.04  5170.8  295.05  5193.2  295.38  5277.4  292.98  5327.8  293.37
    5412  298.65  5692.4  298.96  5714.9   299.9  5731.7  298.84  5782.2  299.18
  5821.5  300.79  5949.6  302.39  6062.6  304.31  6169.4  305.25  6287.2  305.66
#Mann= 7 ,-1 , 0
  4394.3     .05       0  4982.7    .035       0  4988.7     .05       0
  5821.5      .1       0  5949.6     .05       0  6062.6      .1       0
  6169.4     .05       0
Bank Sta=4982.7,4988.7
XS Rating Curve= 0 ,0
Exp/Cntr=0.3,0.1

Chan Stop Cuts=-1
Use User Specified Reach Order=0
Composite Channel Slope=5