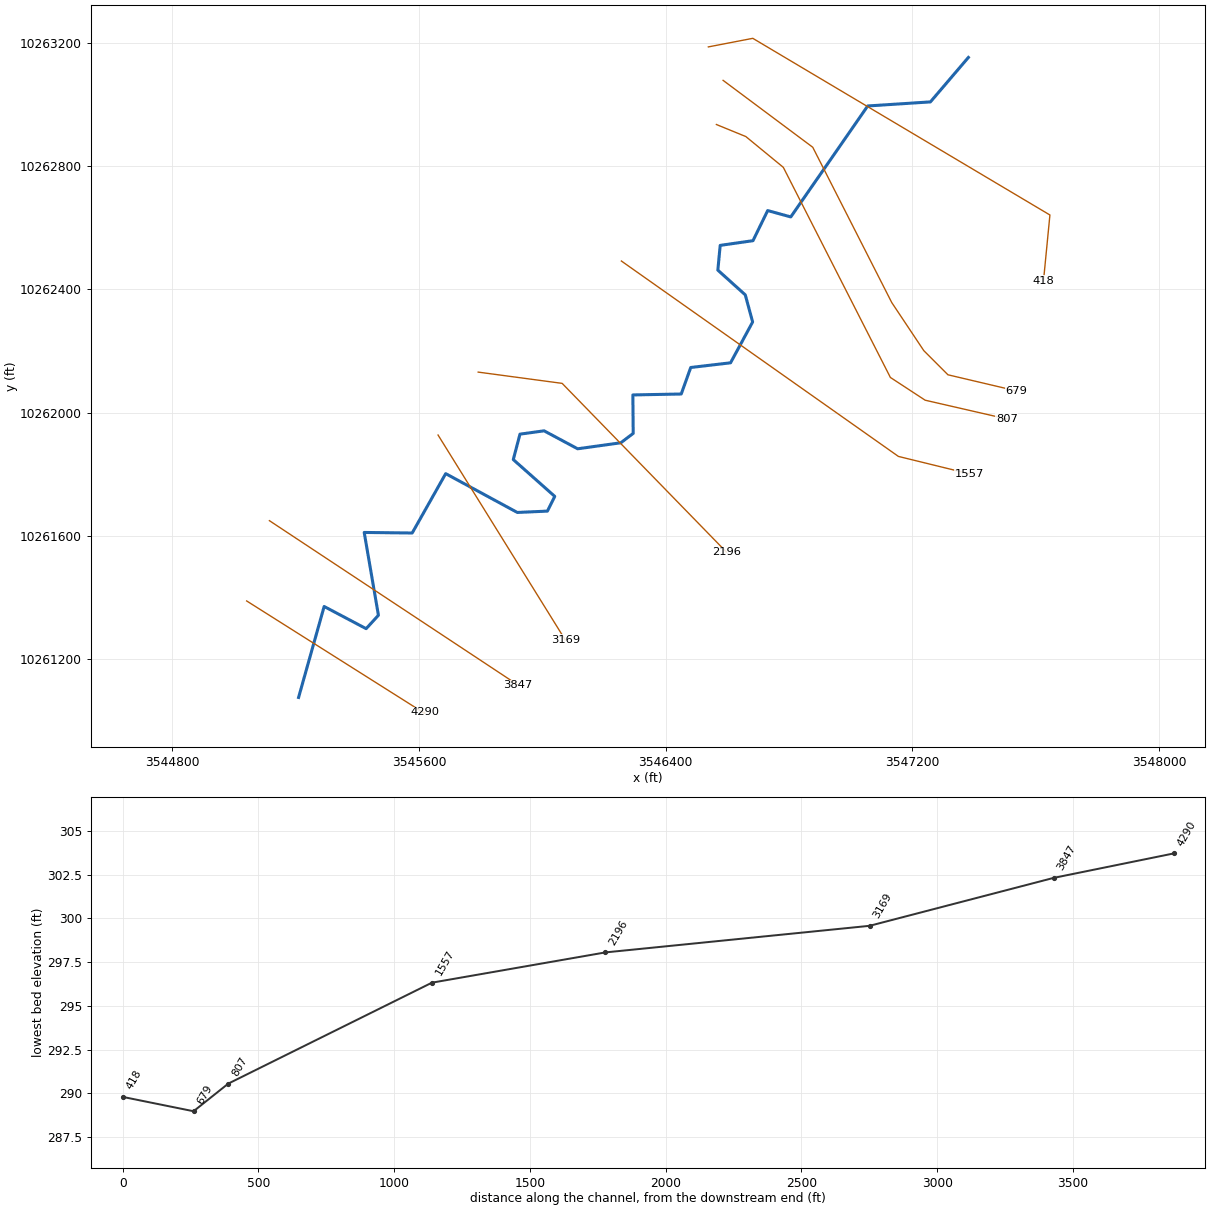
--- WICKSONCREEKTRIB.prj (project) ---

Proj Title=WICKSON CREEK TRIB 38
Current Plan=p01
Default Exp/Contr=0.3,0.1
English Units
Geom File=g01
Flow File=f01
Plan File=p01
Y Axis Title=Elevation
X Axis Title(PF)=Main Channel Distance
X Axis Title(XS)=Station
BEGIN DESCRIPTION:
UNT05127 IN WICK
END DESCRIPTION:
DSS Export Rating Curves= 0
DSS Export Rating Curve Sorted= 0
DSS Export Volume Flow Curves= 0
DXF OffsetX= 0
DXF OffsetY= 0
DXF ScaleX= 1
DXF ScaleY= 10

--- WICKSONCREEKTRIB.p01 (plan) ---

Plan Title=Multiple Run
Short Identifier=Multiple
Geom File=g01
Flow File=f01
Subcritical Flow
K Sum by GR= 0
Std Step Tol= 0.01
Critical Tol= 0.01
Num of Std Step Trials= 20
Max Error Tol= 0.3
Flow Tol Ratio= 0.001
Split Flow NTrial= 30
Split Flow Tol= 0.02
Split Flow Ratio= 0.02
Log Output Level= 0
Friction Slope Method= 1
Unsteady Friction Slope Method= 2
Unsteady Bridges Friction Slope Method= 1
Parabolic Critical Depth
Global Vel Dist=  1 , 1 , 1
Global Log Level= 0
CheckData=True
Encroach Param= -1, 0, 0, 0
BEGIN DESCRIPTION:
Multiple Run
END DESCRIPTION:

--- WICKSONCREEKTRIB.f01 (steady flow) ---

Flow Title=Multiple
Program Version=4.10
Number of Profiles= 7
Profile Names=10-year,25-year,50-year,1pct_min,100-year,1pct_plu,500-year
River Rch & RM=UNT05127 IN WICK,Reach-1         ,4290
     416     546     649     565     765    1034    1064
River Rch & RM=WICKSONCRTRB38,Reach-1         ,4290
     416     546     649     565     765    1034    1064
Boundary for River Rch & Prof#=WICKSONCRTRB38,Reach-1         , 1
Up Type= 0
Dn Type= 3
Dn Slope=0.005
Boundary for River Rch & Prof#=WICKSONCRTRB38,Reach-1         , 2
Up Type= 0
Dn Type= 3
Dn Slope=0.005
Boundary for River Rch & Prof#=WICKSONCRTRB38,Reach-1         , 3
Up Type= 0
Dn Type= 3
Dn Slope=0.005
Boundary for River Rch & Prof#=WICKSONCRTRB38,Reach-1         , 4
Up Type= 0
Dn Type= 3
Dn Slope=0.005
Boundary for River Rch & Prof#=WICKSONCRTRB38,Reach-1         , 5
Up Type= 0
Dn Type= 3
Dn Slope=0.005
Boundary for River Rch & Prof#=WICKSONCRTRB38,Reach-1         , 6
Up Type= 0
Dn Type= 3
Dn Slope=0.005
Boundary for River Rch & Prof#=WICKSONCRTRB38,Reach-1         , 7
Up Type= 0
Dn Type= 3
Dn Slope=0.005
DSS Import GetInterval= 0
DSS Import GetPeak= 0
DSS Import FillOption= 0

--- WICKSONCREEKTRIB.g01 (geometry) ---

Geom Title=Existing Conditions
Program Version=4.10

River Reach=WICKSONCRTRB38  ,Reach-1
Reach XY= 30
      3545209.91     10261076.04      3545292.81     10261371.05
        3545429.     10261299.11      3545468.83     10261342.61
      3545422.71     10261611.15      3545578.36     10261609.37
      3545687.01     10261801.88      3545919.21     10261676.01
      3546016.87     10261680.35      3546040.74     10261728.09
      3545906.19     10261847.45      3545927.89     10261929.92
      3546006.02     10261940.77      3546114.97     10261882.47
      3546254.94       10261902.      3546295.09     10261932.39
      3546294.01     10262057.17       3546450.9     10262060.13
      3546481.72     10262146.14      3546610.85     10262161.34
      3546682.46     10262293.71      3546658.59      10262381.6
      3546569.61      10262461.9      3546577.21     10262542.19
      3546683.55     10262557.39      3546731.29     10262655.04
      3546806.16     10262634.43       3547055.6     10262994.27
      3547259.04     10263007.51      3547382.11     10263151.64

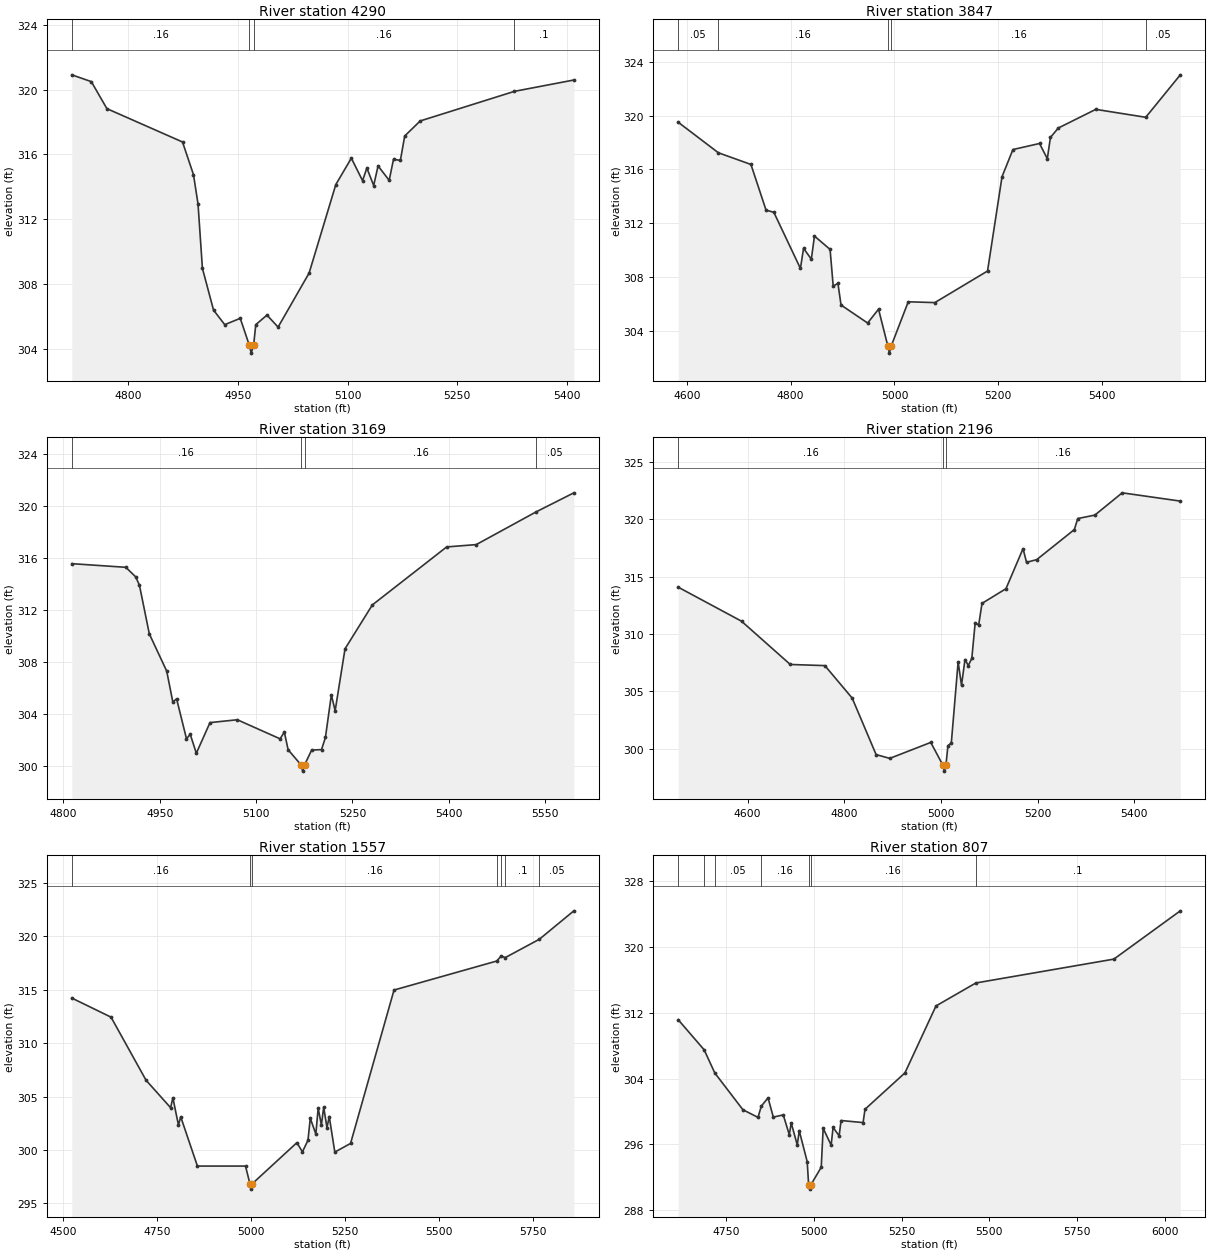
Type RM Length L Ch R = 1 ,4290    ,443,443,443
BEGIN DESCRIPTION:
UNT05127 IN WICK 8.0
END DESCRIPTION:
XS GIS Cut Line= 3
      3545041.53     10261388.97      3545618.76      10261024.4
      3545618.76     10261027.68
#Sta/Elev= 30
  4723.2  320.92  4749.9   320.5  4771.2  318.83  4874.5  316.77  4889.5  314.75
  4895.7  312.94  4901.7  308.96  4916.9  306.38  4932.2  305.48  4953.4  305.87
  4965.7  304.22  4968.4  303.72  4971.7  304.22  4974.6  305.48  4989.9  306.07
  5005.1  305.33  5047.5  308.67    5084  314.14  5105.2  315.77  5120.5  314.38
  5126.4  315.16  5135.7  314.08  5141.7  315.29  5156.9   314.4  5162.8   315.7
  5172.2  315.63  5178.1  317.14  5199.3  318.07  5328.1   319.9  5409.2   320.6
#Mann= 4 ,-1 , 0
  4723.2     .16       0  4965.7     .07       0  4971.7     .16       0
  5328.1      .1       0
Bank Sta=4965.7,4971.7
XS Rating Curve= 0 ,0
Exp/Cntr=0.3,0.1

Type RM Length L Ch R = 1 ,3847    ,678,678,678
BEGIN DESCRIPTION:
UNT05127 IN WICK 7.0
END DESCRIPTION:
XS GIS Cut Line= 2
      3545115.32     10261649.38      3545921.74      10261116.1
#Sta/Elev= 30
  4583.6   319.5  4660.9  317.23  4723.6  316.36  4752.7  312.96  4767.7   312.8
  4818.9  308.62  4824.9  310.12  4839.9  309.31  4845.9  311.03    4876  310.04
    4882  307.31  4891.1  307.51  4897.1   305.9  4948.3  304.56  4969.3  305.59
  4987.4  302.82  4990.1  302.32  4993.4  302.82  5026.5  306.14  5077.7  306.08
  5179.2  308.43  5207.1  315.45  5228.1  317.47  5279.3  317.92  5294.3  316.79
  5300.3  318.37  5315.4  319.07  5387.6  320.46  5483.8  319.87  5550.4  323.03
#Mann= 5 ,-1 , 0
  4583.6     .05       0  4660.9     .16       0  4987.4     .07       0
  4993.4     .16       0  5483.8     .05       0
Bank Sta=4987.4,4993.4
XS Rating Curve= 0 ,0
Exp/Cntr=0.3,0.1

Type RM Length L Ch R = 1 ,3169    ,973,973,973
BEGIN DESCRIPTION:
UNT05127 IN WICK 6.0
END DESCRIPTION:
XS GIS Cut Line= 2
      3545662.18     10261927.15      3546074.47     10261263.14
#Sta/Elev= 30
    4813  315.57  4897.1  315.29  4912.4  314.56  4918.3  313.92  4933.7  310.16
  4960.8  307.29  4970.3  304.91  4976.2  305.15  4991.6  302.07  4997.4  302.42
  5006.9  300.96  5028.2  303.32  5070.7  303.54  5137.3  302.07  5143.9  302.59
  5149.8  301.23  5169.6  300.08  5172.4  299.58  5175.6  300.08  5186.4   301.2
  5201.8  301.24  5207.9  302.18  5217.1  305.46    5223  304.23  5238.4  309.01
  5280.9  312.39  5396.6  316.86  5442.7  317.04  5535.8  319.56  5594.6  321.03
#Mann= 4 ,-1 , 0
    4813     .16       0  5169.6     .07       0  5175.6     .16       0
  5535.8     .05       0
Bank Sta=5169.6,5175.6
XS Rating Curve= 0 ,0
Exp/Cntr=0.3,0.1

Type RM Length L Ch R = 1 ,2196    ,639,639,639
BEGIN DESCRIPTION:
UNT05127 IN WICK 5.0
END DESCRIPTION:
XS GIS Cut Line= 3
      3545792.38     10262131.17      3546064.66     10262094.64
      3546597.72     10261547.22
#Sta/Elev= 30
  4456.4  314.08  4587.3  311.12  4688.2  307.35  4759.8  307.25  4816.3  304.42
  4865.8   299.5  4894.1  299.17  4978.9  300.56  5004.2  298.56    5007  298.06
  5010.2  298.56  5014.4  300.27  5021.4  300.51  5035.5  307.57  5042.5  305.54
  5049.7  307.78  5056.6  307.26  5063.8  307.88  5070.8  310.99    5078  310.78
  5084.9  312.67  5134.5  313.95  5169.8  317.44    5177  316.25  5198.1  316.48
    5276   319.1    5283  320.06  5318.4  320.36    5375   322.3  5495.2  321.58
#Mann= 3 ,-1 , 0
  4456.4     .16       0  5004.2     .07       0  5010.2     .16       0
Bank Sta=5004.2,5010.2
XS Rating Curve= 0 ,0
Exp/Cntr=0.3,0.1

Type RM Length L Ch R = 1 ,1557    ,750,750,750
BEGIN DESCRIPTION:
UNT05127 IN WICK 4.0
END DESCRIPTION:
XS GIS Cut Line= 3
      3546256.75     10262491.43      3547155.22     10261857.73
      3547385.23     10261801.31
#Sta/Elev= 30
  4522.3  314.23  4626.8  312.44    4720  306.53  4785.3  303.96  4791.4  304.88
  4806.2  302.34  4812.3   303.1  4856.7  298.49  4984.7  298.49  4996.5  296.83
  4999.3  296.33  5002.5  296.83  5121.4  300.68  5136.2  299.82    5151  300.91
  5157.1  302.97  5171.9  301.49  5178.1  303.91  5186.7  302.34  5192.8  304.01
  5201.5  302.09  5207.6  303.13  5222.4   299.8  5264.3  300.61    5380  314.98
  5653.7   317.7  5665.1  318.17  5676.1  318.02  5766.9  319.74  5858.6   322.4
#Mann= 7 ,-1 , 0
  4522.3     .16       0  4996.5     .07       0  5002.5     .16       0
  5653.7      .1       0  5665.1     .05       0  5676.1      .1       0
  5766.9     .05       0
Bank Sta=4996.5,5002.5
XS Rating Curve= 0 ,0
Exp/Cntr=0.3,0.1

Type RM Length L Ch R = 1 ,807     ,128,128,128
BEGIN DESCRIPTION:
UNT05127 IN WICK 3.0
END DESCRIPTION:
XS GIS Cut Line= 6
      3546564.92     10262934.13      3546660.43     10262895.06
      3546781.95     10262795.23      3547129.18     10262113.81
      3547242.02     10262040.02      3547506.81     10261979.25
#Sta/Elev= 30
  4612.7  311.15  4686.7  307.49    4717  304.68  4797.2  300.21  4840.2  299.28
  4849.8  300.66  4868.9  301.65  4883.9  299.32  4912.3  299.58  4929.5  297.17
    4935  298.61  4952.3  295.92  4957.8  297.67  4980.6   293.9  4984.7  291.06
  4987.5  290.56  4990.7  291.06  5020.6  293.22  5026.1  297.95  5048.9  295.91
  5054.4  298.06  5071.7  297.04  5077.2   298.9    5140  298.65  5145.5  300.27
  5259.4  304.69    5348  312.83  5461.7  315.62  5855.4  318.52  6044.9  324.39
#Mann= 7 ,-1 , 0
  4612.7     .05       0  4686.7      .1       0    4717     .05       0
  4849.8     .16       0  4984.7     .07       0  4990.7     .16       0
  5461.7      .1       0
Bank Sta=4984.7,4990.7
XS Rating Curve= 0 ,0
Exp/Cntr=0.3,0.1

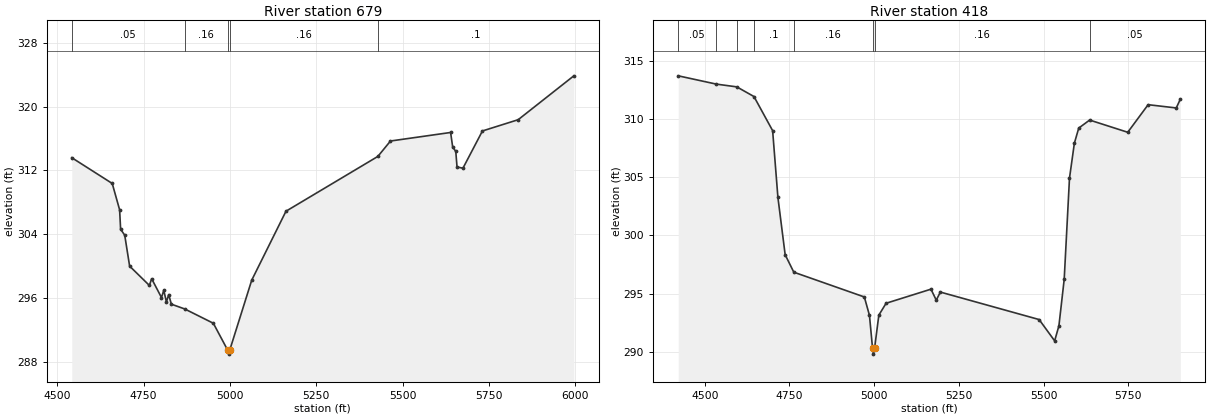
Type RM Length L Ch R = 1 ,679     ,261,261,261
BEGIN DESCRIPTION:
UNT05127 IN WICK 2.0
END DESCRIPTION:
XS GIS Cut Line= 6
      3546586.67     10263077.33      3546877.44     10262860.33
      3547133.52     10262356.86      3547237.68     10262200.61
      3547315.81     10262122.49      3547537.15     10262070.41
#Sta/Elev= 30
  4541.8   313.6    4659  310.37  4680.4  307.07  4683.3  304.63  4695.2  303.89
  4709.4  300.01  4766.6  297.59  4773.2  298.43  4801.7  296.07  4808.3  296.98
    4816  295.52  4822.6  296.44  4830.3  295.24  4869.1  294.64  4951.9  292.85
  4993.4  289.48  4996.1  288.98  4999.4  289.48  5063.1  298.25  5162.3  306.89
  5428.5  313.76    5465  315.69  5639.2  316.76  5645.2  314.95  5654.2  314.38
  5657.8  312.44  5674.9  312.28  5731.4  316.95  5834.9  318.36  5996.2  323.86
#Mann= 5 ,-1 , 0
  4541.8     .05       0  4869.1     .16       0  4993.4     .07       0
  4999.4     .16       0  5428.5      .1       0
Bank Sta=4993.4,4999.4
XS Rating Curve= 0 ,0
Exp/Cntr=0.3,0.1

Type RM Length L Ch R = 1 ,418     ,0,0,0
BEGIN DESCRIPTION:
UNT05127 IN WICK 1.0
END DESCRIPTION:
XS GIS Cut Line= 4
      3546538.85     10263185.85        3546683.     10263213.63
      3547646.54     10262640.72       3547625.7     10262427.13
#Sta/Elev= 30
  4421.5  313.71  4533.6     313  4594.5  312.76  4645.1  311.93  4700.2     309
  4715.8  303.26  4737.2  298.34  4762.7  296.84    4971  294.71  4986.1  293.13
  4995.2   290.3    4998   289.8  5001.2   290.3  5013.8  293.15  5035.2  294.17
  5167.7  295.38  5183.3  294.44  5195.5  295.13  5487.1  292.77  5532.9  290.94
  5545.5  292.24  5561.1  296.23  5576.7  304.92  5591.1  307.92    5604  309.22
  5636.2  309.91  5748.7  308.86  5808.9  311.23  5891.9  310.95  5903.9   311.7
#Mann= 8 ,-1 , 0
  4421.5     .05       0  4533.6      .1       0  4594.5     .05       0
  4645.1      .1       0  4762.7     .16       0  4995.2     .07       0
  5001.2     .16       0  5636.2     .05       0
Bank Sta=4995.2,5001.2
XS Rating Curve= 0 ,0
Exp/Cntr=0.3,0.1

Chan Stop Cuts=-1
Use User Specified Reach Order=0
Composite Channel Slope=5