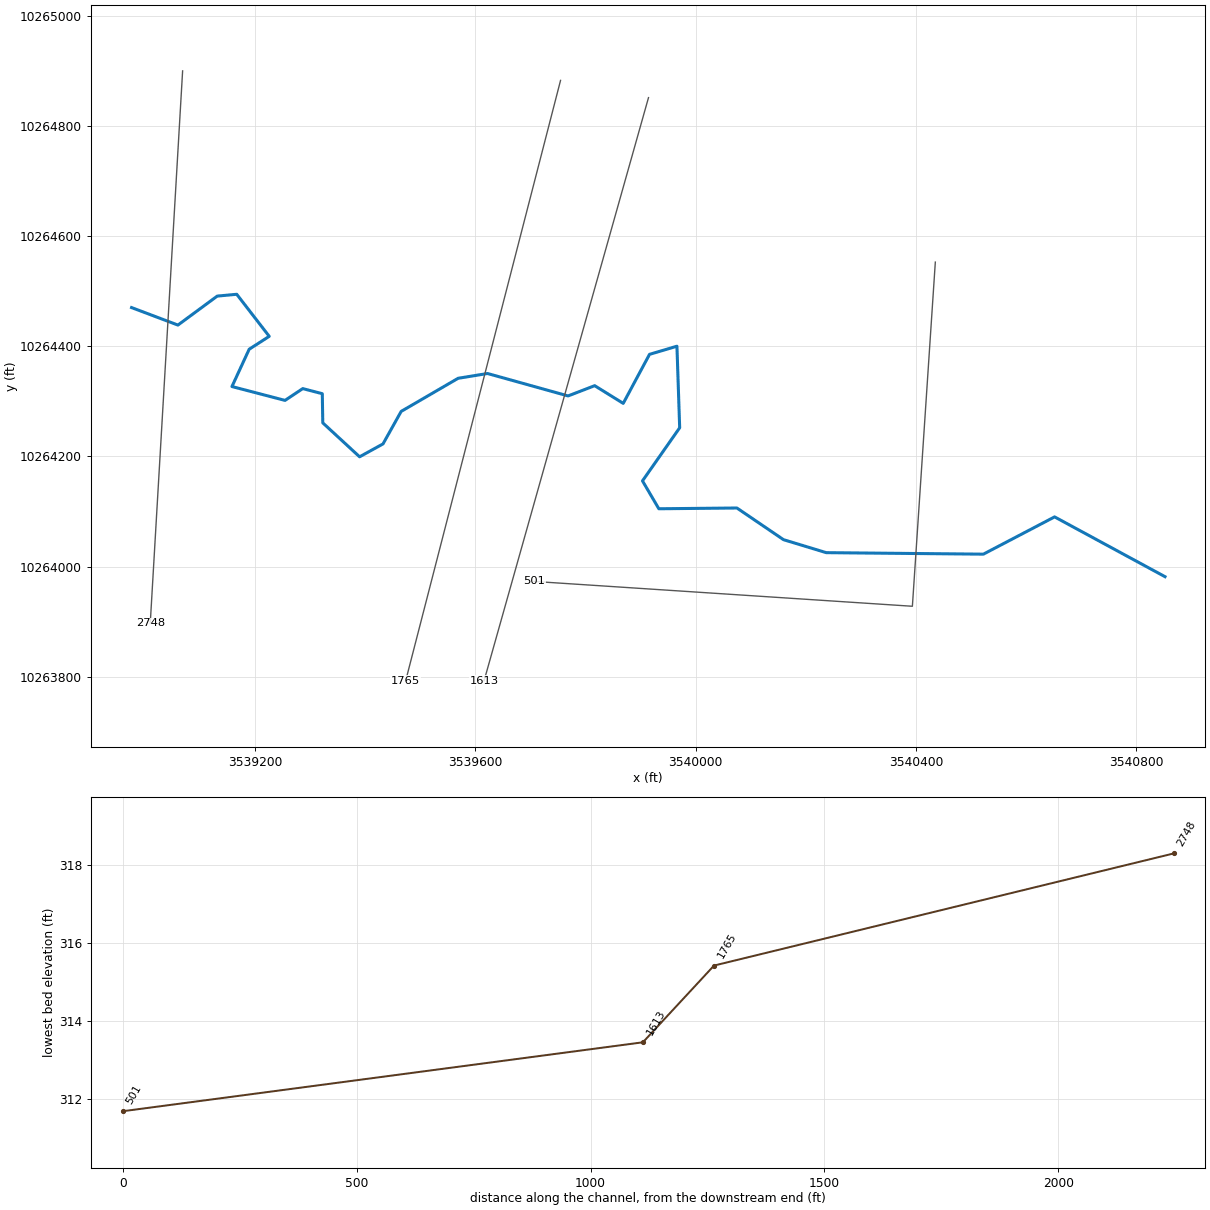
--- WICKSON CREEK TRIB 39 2.prj (project) ---

Proj Title=WICKSON CREEK TRIB 39 2 Base Level Engineering
Current Plan=p01
Default Exp/Contr=0.3,0.1
English Units
Geom File=g01
Flow File=f01
Plan File=p01
Y Axis Title=Elevation
X Axis Title(PF)=Main Channel Distance
X Axis Title(XS)=Station
BEGIN DESCRIPTION:
WICKSON CREEK TRIB 39 2
END DESCRIPTION:
DSS Export Rating Curves= 0
DSS Export Rating Curve Sorted= 0
DSS Export Volume Flow Curves= 0
DXF OffsetX= 0
DXF OffsetY= 0
DXF ScaleX= 1
DXF ScaleY= 10

--- WICKSON CREEK TRIB 39 2.p01 (plan) ---

Plan Title=Multiple Run
Short Identifier=Multiple
Geom File=g01
Flow File=f01
Subcritical Flow
K Sum by GR= 0
Std Step Tol= 0.01
Critical Tol= 0.01
Num of Std Step Trials= 20
Max Error Tol= 0.3
Flow Tol Ratio= 0.001
Split Flow NTrial= 30
Split Flow Tol= 0.02
Split Flow Ratio= 0.02
Log Output Level= 0
Friction Slope Method= 1
Unsteady Friction Slope Method= 2
Unsteady Bridges Friction Slope Method= 1
Parabolic Critical Depth
Global Vel Dist=  1 , 1 , 1
Global Log Level= 0
CheckData=True
Encroach Param= -1, 0, 0, 0
BEGIN DESCRIPTION:
Multiple Run
END DESCRIPTION:

--- WICKSON CREEK TRIB 39 2.f01 (steady flow) ---

Flow Title=Multiple
Program Version=4.10
Number of Profiles= 7
Profile Names=10-year,25-year,50-year,1pct_min,100-year,1pct_plu,500-year
River Rch & RM=WICKSON CREEK TR,Reach-1         ,2748
     588     789     951     840    1136    1536    1623
Boundary for River Rch & Prof#=WICKSON CREEK TR,Reach-1         , 1
Up Type= 0
Dn Type= 3
Dn Slope=0.005
Boundary for River Rch & Prof#=WICKSON CREEK TR,Reach-1         , 2
Up Type= 0
Dn Type= 3
Dn Slope=0.005
Boundary for River Rch & Prof#=WICKSON CREEK TR,Reach-1         , 3
Up Type= 0
Dn Type= 3
Dn Slope=0.005
Boundary for River Rch & Prof#=WICKSON CREEK TR,Reach-1         , 4
Up Type= 0
Dn Type= 3
Dn Slope=0.005
Boundary for River Rch & Prof#=WICKSON CREEK TR,Reach-1         , 5
Up Type= 0
Dn Type= 3
Dn Slope=0.005
Boundary for River Rch & Prof#=WICKSON CREEK TR,Reach-1         , 6
Up Type= 0
Dn Type= 3
Dn Slope=0.005
Boundary for River Rch & Prof#=WICKSON CREEK TR,Reach-1         , 7
Up Type= 0
Dn Type= 3
Dn Slope=0.005
DSS Import GetInterval= 0
DSS Import GetPeak= 0
DSS Import FillOption= 0

--- WICKSON CREEK TRIB 39 2.g01 (geometry) ---

Geom Title=Existing Conditions

River Reach=WICKSON CREEK TR,Reach-1
Reach XY= 30
      3538975.50     10264470.31      3539059.67     10264438.54
      3539131.06     10264491.15      3539166.47     10264494.44
      3539225.50     10264418.06      3539189.04     10264394.62
      3539157.79     10264326.91      3539254.15     10264301.74
      3539286.39     10264323.18      3539321.85     10264313.89
      3539322.72     10264260.94      3539389.56     10264199.31
      3539432.10     10264222.74      3539465.08     10264281.77
      3539568.49     10264341.88      3539621.88     10264350.57
      3539768.15     10264309.85      3539816.46     10264328.48
      3539868.27     10264296.35      3539916.03     10264385.37
      3539965.83     10264400.15      3539970.79     10264252.02
      3539903.26     10264155.62      3539932.96     10264104.97
      3540074.72     10264106.35      3540159.36     10264048.84
      3540236.94     10264025.26      3540522.30     10264022.54
      3540651.62     10264090.20      3540852.11     10263981.64

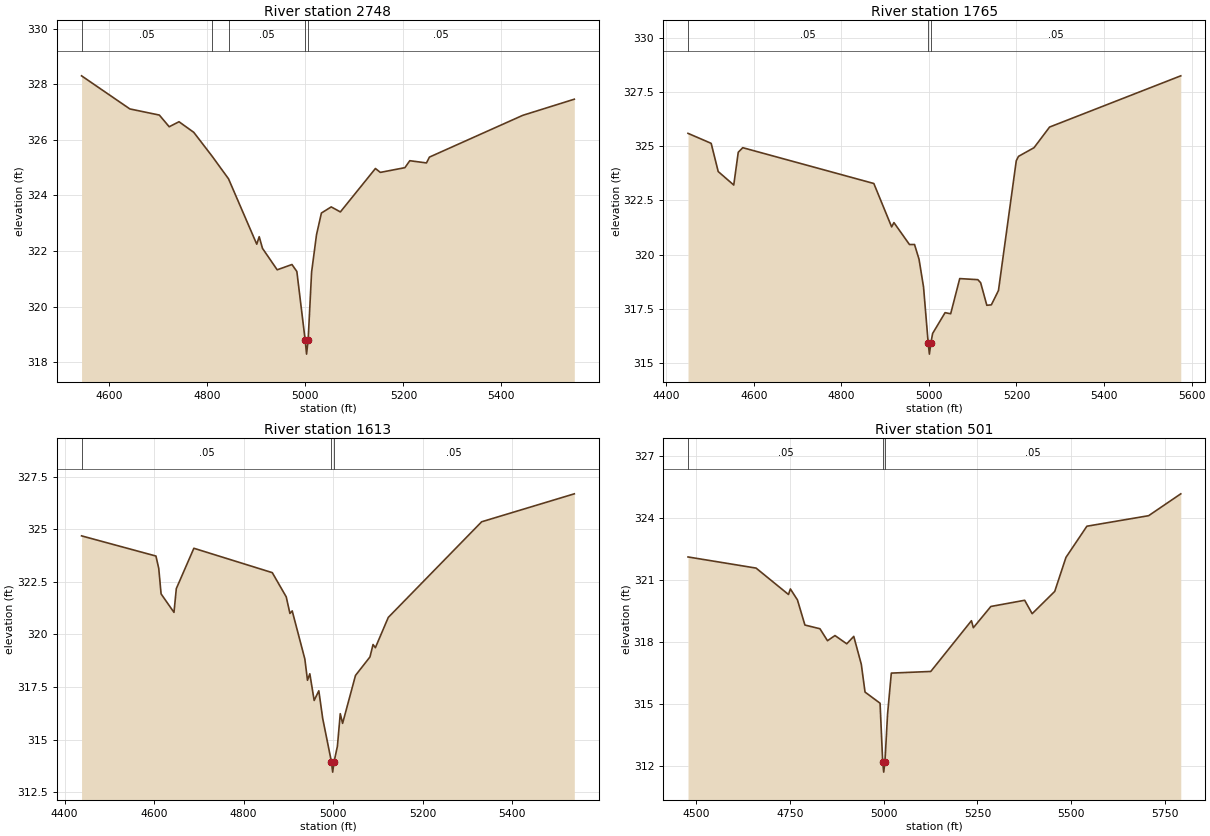
Type RM Length L Ch R = 1,2748,983,983,983
BEGIN DESCRIPTION:
WICKSON CREEK TRIB 39 2 3.0
END DESCRIPTION:
XS GIS Cut Line= 2
      3539068.20     10264900.11      3539009.40     10263896.63
#Sta/Elev= 30
  4543.5  328.30  4642.1  327.11  4702.2  326.89  4722.3  326.47  4742.3  326.65
  4772.4  326.27  4809.9  325.41  4843.3  324.60  4900.9  322.25  4905.9  322.52
  4912.6  322.10  4942.6  321.33  4972.7  321.52  4982.7  321.27  4999.7  318.80
  5002.5  318.30  5005.7  318.80  5012.8  321.25  5022.8  322.59  5032.8  323.37
  5052.8  323.59  5071.5  323.41  5143.0  324.97  5153.0  324.83  5203.1  325.00
  5213.1  325.25  5247.1  325.17  5253.2  325.38  5443.5  326.88  5548.7  327.46
#Mann=5,-1,0
  4543.5    0.05       0  4809.9    0.07       0  4843.3    0.05       0
  4999.7    0.03       0  5005.7    0.05       0
Bank Sta=4999.7,5005.7
Exp/Cntr=0.3,0.1

Type RM Length L Ch R = 1,1765,152,152,152
BEGIN DESCRIPTION:
WICKSON CREEK TRIB 39 2 2.0
END DESCRIPTION:
XS GIS Cut Line= 2
      3539754.48     10264882.82      3539473.23     10263792.51
#Sta/Elev= 30
  4449.5  325.59  4502.4  325.13  4518.5  323.83  4554.0  323.21  4564.3  324.72
  4574.6  324.93  4874.1  323.28  4914.8  321.28  4920.0  321.48  4955.5  320.47
  4967.1  320.47  4977.4  319.79  4987.7  318.51  4998.4  315.92  5001.1  315.42
  5004.4  315.92  5008.4  316.37  5036.9  317.33  5049.7  317.28  5070.4  318.90
  5111.7  318.85  5118.2  318.71  5132.3  317.67  5142.6  317.69  5158.9  318.35
  5199.6  324.33  5204.7  324.53  5240.2  324.93  5275.7  325.88  5575.5  328.24
#Mann=3,-1,0
  4449.5    0.05       0  4998.4    0.04       0  5004.4    0.05       0
Bank Sta=4998.4,5004.4
Exp/Cntr=0.3,0.1

Type RM Length L Ch R = 1,1613,1112,1112,1112
BEGIN DESCRIPTION:
WICKSON CREEK TRIB 39 2 2.2
END DESCRIPTION:
XS GIS Cut Line= 2
      3539914.19     10264851.52      3539615.59     10263792.51
#Sta/Elev= 30
  4438.0  324.69  4604.1  323.73  4610.4  323.14  4615.6  321.93  4644.4  321.05
  4649.6  322.18  4688.8  324.10  4863.9  322.94  4895.0  321.79  4903.3  321.00
  4908.4  321.12  4936.6  318.83  4942.5  317.82  4947.7  318.13  4957.4  316.86
  4967.8  317.32  4976.5  316.00  4995.9  313.95  4998.7  313.45  5001.9  313.95
  5009.3  314.68  5015.7  316.23  5020.9  315.77  5049.7  318.05  5082.0  318.93
  5088.9  319.52  5094.1  319.37  5122.9  320.81  5331.4  325.36  5538.3  326.69
#Mann=3,-1,0
  4438.0    0.05       0  4995.9    0.04       0  5001.9    0.05       0
Bank Sta=4995.9,5001.9
Exp/Cntr=0.3,0.1

Type RM Length L Ch R = 1,501,0,0,0
BEGIN DESCRIPTION:
WICKSON CREEK TRIB 39 2 1.0
END DESCRIPTION:
XS GIS Cut Line= 3
      3540435.03     10264552.88      3540393.36     10263927.91
      3539706.49     10263973.01
#Sta/Elev= 30
  4477.8  322.11  4659.4  321.57  4745.9  320.29  4750.9  320.56  4769.7  320.03
  4789.7  318.81  4829.8  318.63  4849.9  318.05  4869.9  318.30  4901.3  317.90
  4920.0  318.26  4940.1  316.91  4950.1  315.56  4990.2  315.02  4997.2  312.18
  4999.9  311.68  5003.2  312.18  5010.2  314.49  5020.2  316.48  5125.5  316.56
  5234.0  319.02  5239.1  318.68  5285.8  319.71  5376.0  320.01  5396.0  319.36
  5456.2  320.44  5486.2  322.09  5542.0  323.60  5706.7  324.11  5792.5  325.17
#Mann=3,-1,0
  4477.8    0.05       0  4997.2   0.035       0  5003.2    0.05       0
Bank Sta=4997.2,5003.2
Exp/Cntr=0.3,0.1

Chan Stop Cuts=-1