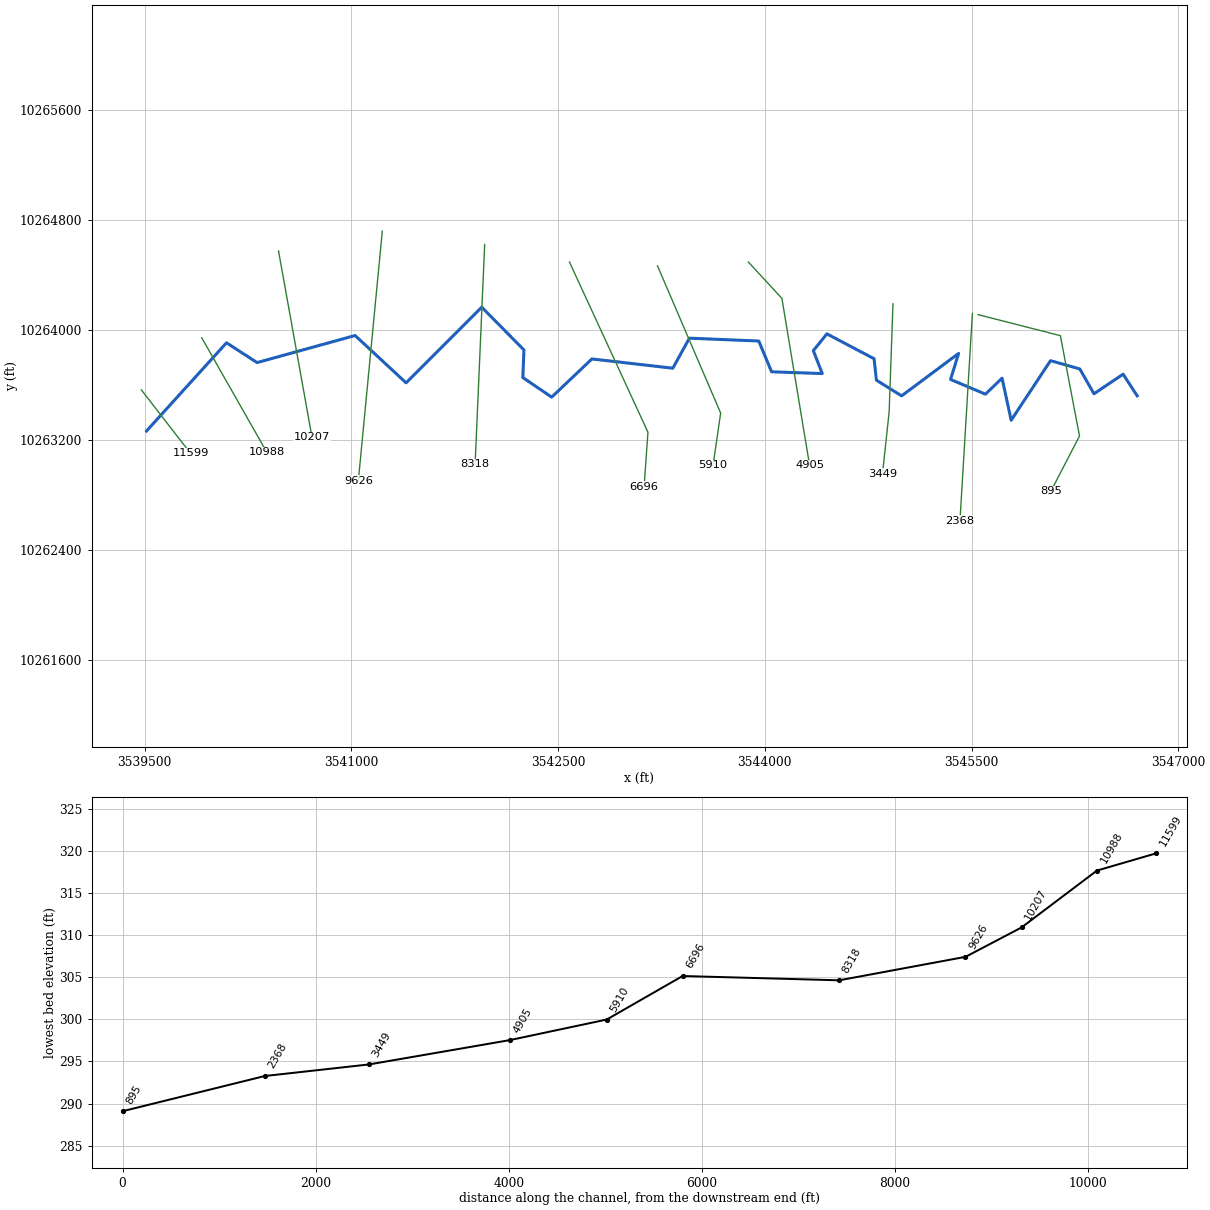
--- WICKSONCREEKTRIB.prj (project) ---

Proj Title=WICKSON CREEK TRIB 39
Current Plan=p01
Default Exp/Contr=0.3,0.1
English Units
Geom File=g01
Flow File=f01
Plan File=p01
Y Axis Title=Elevation
X Axis Title(PF)=Main Channel Distance
X Axis Title(XS)=Station
BEGIN DESCRIPTION:
UNT0494 IN WICK
END DESCRIPTION:
DSS Export Rating Curves= 0
DSS Export Rating Curve Sorted= 0
DSS Export Volume Flow Curves= 0
DXF OffsetX= 0
DXF OffsetY= 0
DXF ScaleX= 1
DXF ScaleY= 10

--- WICKSONCREEKTRIB.p01 (plan) ---

Plan Title=Multiple Run
Short Identifier=Multiple
Geom File=g01
Flow File=f01
Subcritical Flow
K Sum by GR= 0
Std Step Tol= 0.01
Critical Tol= 0.01
Num of Std Step Trials= 20
Max Error Tol= 0.3
Flow Tol Ratio= 0.001
Split Flow NTrial= 30
Split Flow Tol= 0.02
Split Flow Ratio= 0.02
Log Output Level= 0
Friction Slope Method= 1
Unsteady Friction Slope Method= 2
Unsteady Bridges Friction Slope Method= 1
Parabolic Critical Depth
Global Vel Dist=  1 , 1 , 1
Global Log Level= 0
CheckData=True
Encroach Param= -1, 0, 0, 0
BEGIN DESCRIPTION:
Multiple Run
END DESCRIPTION:

--- WICKSONCREEKTRIB.f01 (steady flow) ---

Flow Title=Multiple
Program Version=4.10
Number of Profiles= 7
Profile Names=10-year,25-year,50-year,1pct_min,100-year,1pct_plu,500-year
River Rch & RM=WICKSONCRTRB39,Reach-1         ,11599
     356     465     551     480     649     878     900
River Rch & RM=WICKSONCRTRB39,Reach-1         ,10207
     800    1089    1326    1181    1597    2160    2324
River Rch & RM=WICKSONCRTRB39,Reach-1         ,6696
     917    1256    1535    1371    1855    2508    2716
Boundary for River Rch & Prof#=WICKSONCRTRB39,Reach-1         , 1
Up Type= 0
Dn Type= 3
Dn Slope=0.005
Boundary for River Rch & Prof#=WICKSONCRTRB39,Reach-1         , 2
Up Type= 0
Dn Type= 3
Dn Slope=0.005
Boundary for River Rch & Prof#=WICKSONCRTRB39,Reach-1         , 3
Up Type= 0
Dn Type= 3
Dn Slope=0.005
Boundary for River Rch & Prof#=WICKSONCRTRB39,Reach-1         , 4
Up Type= 0
Dn Type= 3
Dn Slope=0.005
Boundary for River Rch & Prof#=WICKSONCRTRB39,Reach-1         , 5
Up Type= 0
Dn Type= 3
Dn Slope=0.005
Boundary for River Rch & Prof#=WICKSONCRTRB39,Reach-1         , 6
Up Type= 0
Dn Type= 3
Dn Slope=0.005
Boundary for River Rch & Prof#=WICKSONCRTRB39,Reach-1         , 7
Up Type= 0
Dn Type= 3
Dn Slope=0.005
DSS Import GetInterval= 0
DSS Import GetPeak= 0
DSS Import FillOption= 0

--- WICKSONCREEKTRIB.g01 (geometry) ---

Geom Title=Existing Conditions
Program Version=4.10

River Reach=WICKSONCRTRB39  ,Reach-1
Reach XY= 30
      3539513.04     10263266.48       3540093.1      10263907.1
      3540314.92     10263763.14      3541026.51     10263959.79
       3541396.6     10263615.75      3541945.43     10264165.58
      3542251.68     10263854.82      3542243.69     10263654.47
      3542453.07     10263512.11      3542745.08     10263789.54
      3543332.23     10263722.18      3543452.43     10263940.44
      3543956.01     10263919.69       3544048.9     10263696.14
      3544416.54     10263683.39      3544351.95     10263849.84
      3544450.26     10263971.78      3544792.63     10263791.23
      3544809.64     10263635.26      3544992.58     10263521.21
      3545406.25     10263829.72      3545347.76     10263640.57
      3545601.07     10263533.55      3545721.51       10263650.
      3545787.61     10263344.08      3546073.15     10263777.08
      3546285.67     10263716.98      3546388.79      10263536.4
      3546600.05     10263678.77      3546702.11     10263521.64

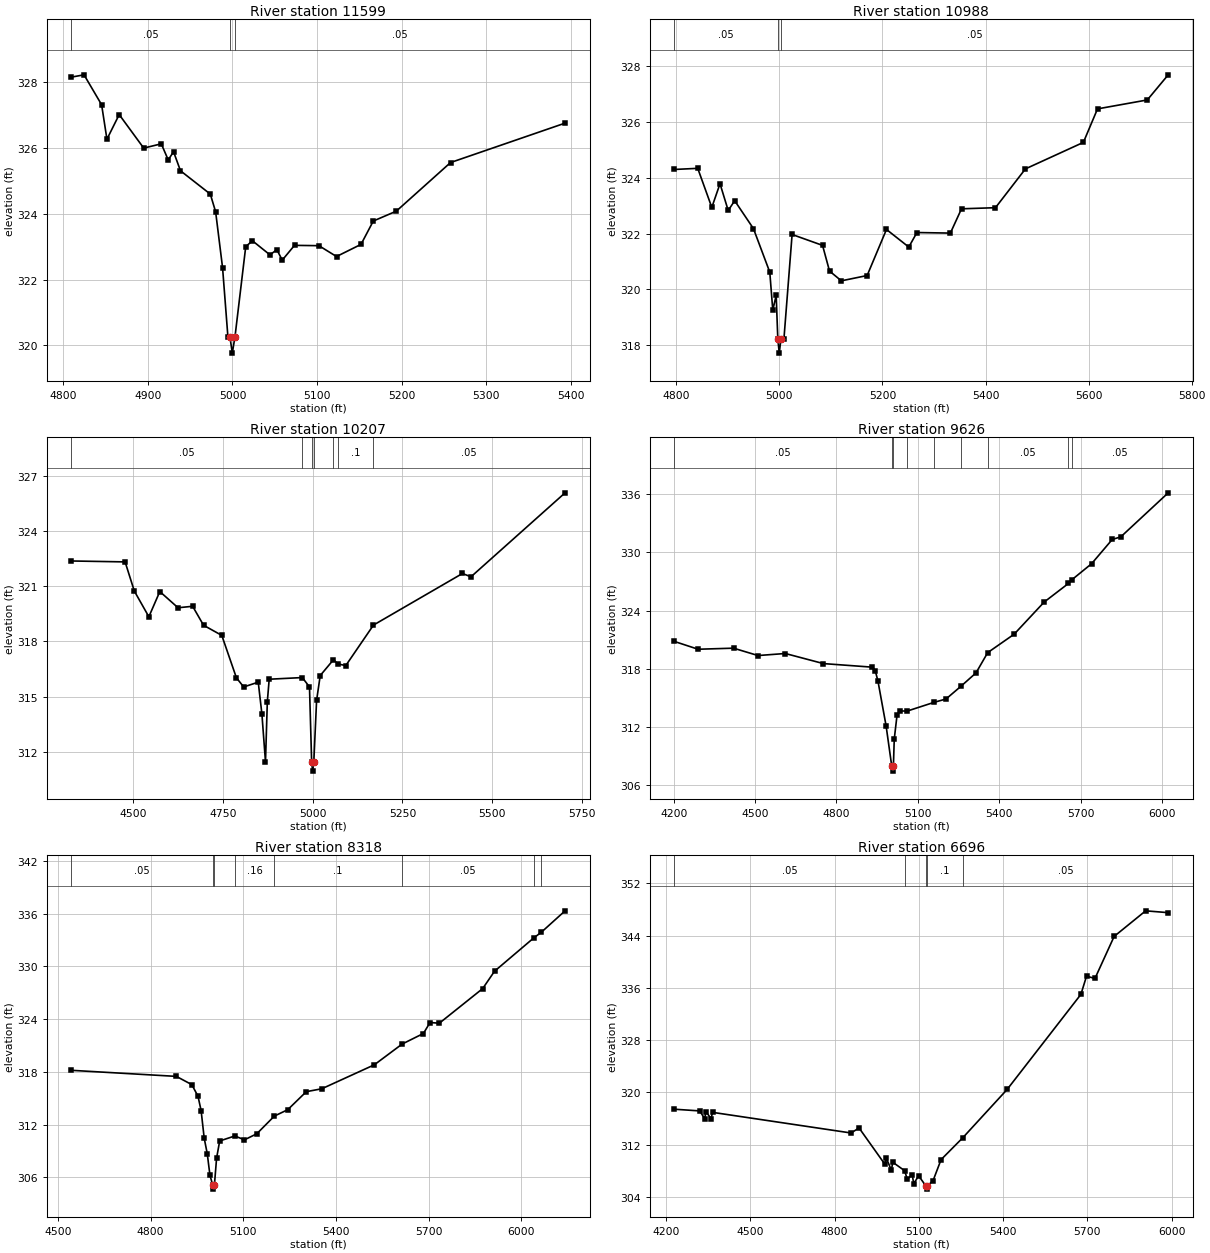
Type RM Length L Ch R = 1 ,11599   ,611,611,611
BEGIN DESCRIPTION:
UNT0494 IN WICK 16.0
END DESCRIPTION:
XS GIS Cut Line= 2
      3539475.01     10263564.72      3539832.65     10263102.91
#Sta/Elev= 30
  4809.4  328.16  4824.4  328.23  4845.2  327.32  4851.5  326.27    4866  327.02
    4895     326  4915.8  326.13    4924  325.64  4930.3  325.89  4938.5  325.31
  4973.8   324.6  4980.1  324.06  4988.3  322.36  4994.6  320.26    4997  320.26
  4999.8  319.76    5003  320.26  5015.7     323  5023.6  323.18  5044.4  322.75
  5052.5  322.91  5058.9  322.59  5073.4  323.04  5102.3  323.03  5123.1   322.7
  5152.1  323.07  5166.6  323.78  5193.8  324.08    5258  325.56  5393.5  326.76
#Mann= 3 ,-1 , 0
  4809.4     .05       0    4997     .04       0    5003     .05       0
Bank Sta=4997,5003
XS Rating Curve= 0 ,0
Exp/Cntr=0.3,0.1

Type RM Length L Ch R = 1 ,10988   ,781,781,781
BEGIN DESCRIPTION:
Mapping XS 01619a78
END DESCRIPTION:
XS GIS Cut Line= 2
      3539913.36     10263943.22      3540386.51     10263110.21
#Sta/Elev= 30
  4796.5   324.3  4841.6  324.34  4868.9  322.94  4884.8  323.79  4900.7  322.83
  4913.3  323.18  4949.7  322.18  4981.4  320.62  4987.2  319.26  4993.8  319.79
    4997  318.22  4999.8  317.72    5003  318.22  5008.8  318.22  5024.7  321.97
  5083.8  321.58  5097.3  320.66  5120.3  320.31  5170.3   320.5  5207.8  322.15
  5251.1  321.52  5266.9  322.04  5331.8  322.02  5353.4  322.89  5419.3  322.93
  5477.4  324.32  5589.9  325.27  5617.3  326.47  5713.9  326.79  5754.5  327.69
#Mann= 3 ,-1 , 0
  4796.5     .05       0    4997    .035       0    5003     .05       0
Bank Sta=4997,5003
XS Rating Curve= 0 ,0
Exp/Cntr=0.3,0.1

Type RM Length L Ch R = 1 ,10207   ,581,581,581
BEGIN DESCRIPTION:
UNT0494 IN WICK 14.0
END DESCRIPTION:
XS GIS Cut Line= 2
      3540470.66     10264574.28      3540713.71     10263220.12
#Sta/Elev= 30
  4327.4  322.36  4477.2  322.31  4502.8  320.73  4543.4  319.33  4573.9   320.7
  4624.7  319.82  4665.4   319.9  4695.8  318.87  4746.6  318.32  4787.3  316.02
  4807.6  315.52  4848.2  315.78  4858.4  314.05  4868.4  311.45  4873.5  314.72
  4878.7  315.94    4971  316.03    4991  315.52    4997  311.45  4999.8  310.95
    5003  311.45  5010.8  314.79  5020.9  316.14  5057.9     317  5070.1  316.77
  5092.1  316.68  5169.3  318.88  5417.2  321.68    5441   321.5  5703.2  326.06
#Mann= 7 ,-1 , 0
  4327.4     .05       0    4971      .1       0    4997     .07       0
    5003      .1       0  5057.9     .05       0  5070.1      .1       0
  5169.3     .05       0
Bank Sta=4997,5003
XS Rating Curve= 0 ,0
Exp/Cntr=0.3,0.1

Type RM Length L Ch R = 1 ,9626    ,1308,1308,1308
BEGIN DESCRIPTION:
UNT0494 IN WICK 12.0
END DESCRIPTION:
XS GIS Cut Line= 2
      3541223.67     10264718.27       3541050.1     10262906.16
#Sta/Elev= 30
  4202.7  320.82  4289.7  320.02  4420.3  320.13  4510.7  319.37  4611.2  319.58
  4751.8  318.54  4932.7  318.17  4942.7  317.82  4952.7  316.76  4982.9  312.12
  5003.8  307.95  5006.6  307.45  5009.8  307.95    5013  310.76  5023.1  313.19
  5033.1  313.66  5060.3  313.64  5159.4  314.54  5203.9  314.89  5258.4  316.19
  5314.4  317.58  5357.5  319.67    5455  321.57  5565.5  324.88    5655   326.8
    5669  327.21  5740.6  328.84  5816.7  331.34  5848.3  331.61  6023.1  336.15
#Mann= 9 ,-1 , 0
  4202.7     .05       0  5003.8     .03       0  5009.8     .05       0
  5060.3     .16       0  5159.4     .05       0  5258.4      .1       0
  5357.5     .05       0    5655      .1       0    5669     .05       0
Bank Sta=5003.8,5009.8
XS Rating Curve= 0 ,0
Exp/Cntr=0.3,0.1

Type RM Length L Ch R = 1 ,8318    ,1622,1622,1622
BEGIN DESCRIPTION:
UNT0494 IN WICK 11.0
END DESCRIPTION:
XS GIS Cut Line= 2
      3541966.73     10264621.07      3541897.35     10263025.27
#Sta/Elev= 30
  4543.7  318.18  4883.4  317.49  4933.5  316.55  4953.5  315.22  4963.5   313.6
  4973.5  310.46  4983.5  308.67    4992  306.26  5000.6  305.16  5003.3  304.66
  5006.6  305.16  5013.6  308.19  5023.6  310.14  5072.6  310.71  5103.7  310.27
  5143.7  310.96  5200.4  312.97  5243.8   313.7  5303.8  315.75  5353.9  316.08
    5524  318.81  5613.9  321.17  5682.6  322.37  5704.2  323.62  5734.2  323.54
  5874.4  327.48  5912.9  329.46  6039.8  333.25  6063.8  333.88    6141  336.33
#Mann= 8 ,-1 , 0
  4543.7     .05       0  5000.6     .03       0  5006.6     .05       0
  5072.6     .16       0  5200.4      .1       0  5613.9     .05       0
  6039.8      .1       0  6063.8     .05       0
Bank Sta=5000.6,5006.6
XS Rating Curve= 0 ,0
Exp/Cntr=0.3,0.1

Type RM Length L Ch R = 1 ,6696    ,786,786,786
BEGIN DESCRIPTION:
UNT0494 IN WICK 10.0
END DESCRIPTION:
XS GIS Cut Line= 3
      3542582.17     10264493.47      3543151.62     10263257.34
      3543123.85     10262861.51
#Sta/Elev= 30
  4229.8  317.41  4319.9  317.15  4336.8  315.98  4342.3  317.02  4359.8  315.96
  4365.3  316.93  4858.4  313.77  4886.9  314.54  4978.8  308.98  4984.3  309.89
  5001.7  308.09  5007.2  309.28  5049.2  307.99  5058.6  306.67  5076.1   307.4
  5081.6  306.01  5099.1  307.21  5124.5  305.67  5127.3  305.17  5130.5  305.67
  5150.5  306.48  5178.9  309.69  5256.2  313.04  5414.1  320.44  5676.7     335
  5696.8  337.79  5726.8  337.44  5795.1  343.88  5907.3   347.8  5987.6  347.52
#Mann= 5 ,-1 , 0
  4229.8     .05       0  5049.2      .1       0  5124.5    .035       0
  5130.5      .1       0  5256.2     .05       0
Bank Sta=5124.5,5130.5
XS Rating Curve= 0 ,0
Exp/Cntr=0.3,0.1

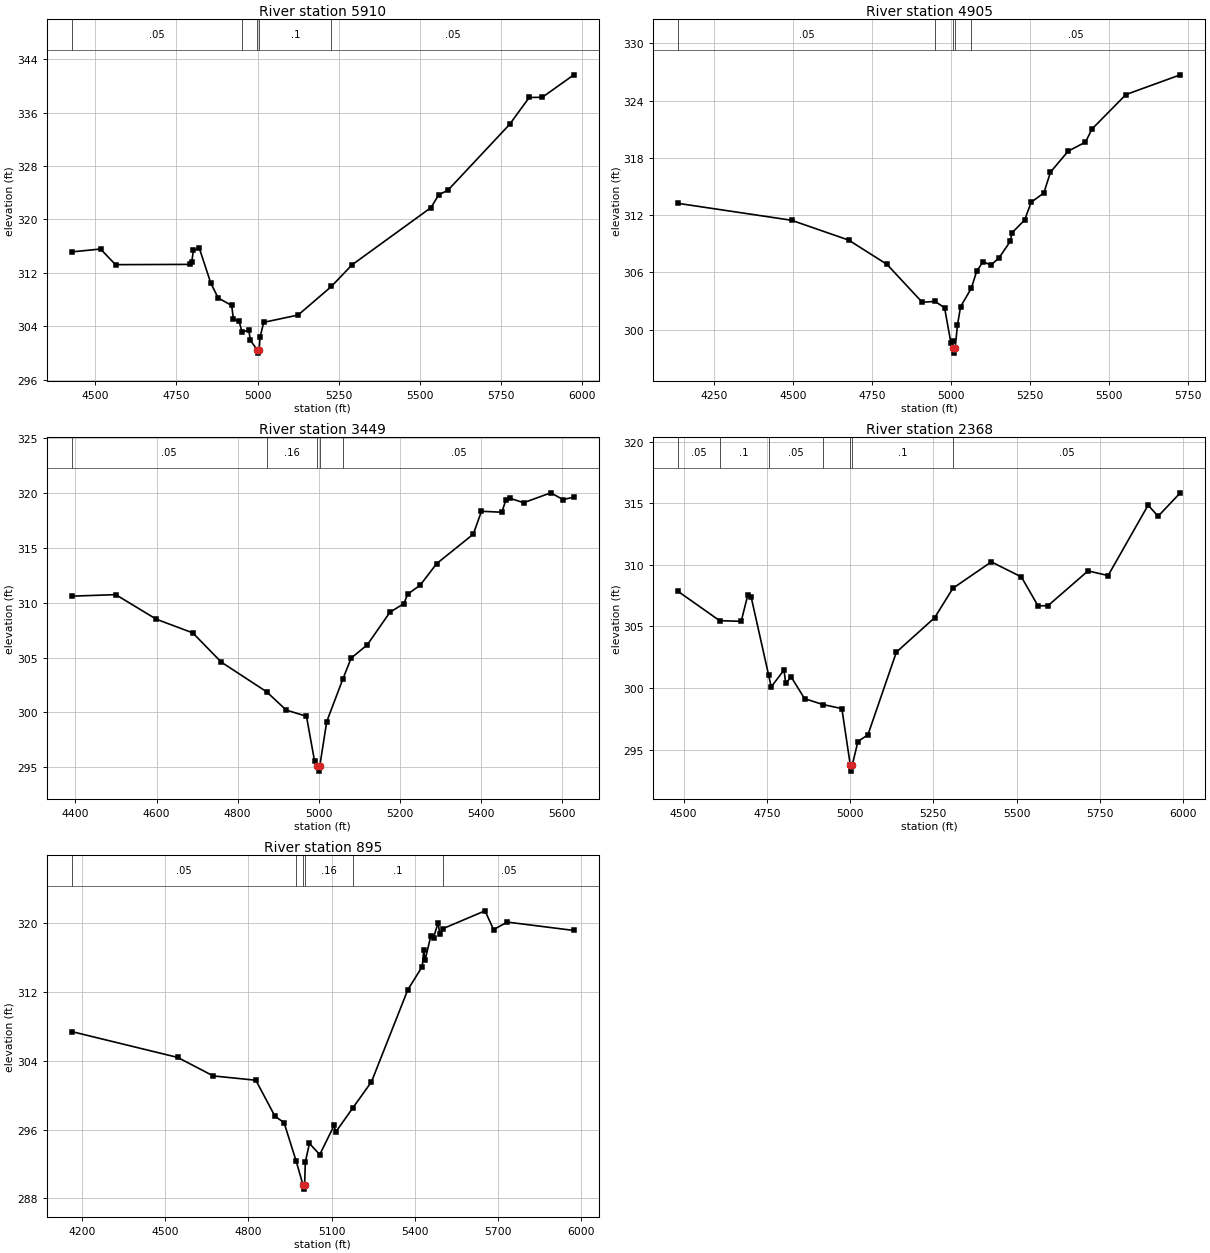
Type RM Length L Ch R = 1 ,5910    ,1005,1005,1005
BEGIN DESCRIPTION:
UNT0494 IN WICK 7.0
END DESCRIPTION:
XS GIS Cut Line= 3
      3543221.07     10264465.66       3543679.4     10263396.22
      3543624.01     10263015.44
#Sta/Elev= 30
  4427.1  315.14  4515.8  315.57    4562  313.23  4790.5  313.27  4796.9  313.62
  4802.3  315.37  4820.5  315.68  4855.8  310.47  4878.5  308.25  4920.2  307.12
  4925.6  305.06  4942.8  304.77  4952.4  303.15  4972.8  303.45  4978.2  301.88
  4998.8  300.49  5001.5  299.99  5004.8  300.49  5008.1  302.45    5019   304.6
  5125.1  305.69  5227.8  309.97    5291  313.19  5534.9  321.77  5558.5  323.66
  5587.5  324.39  5777.1  334.21  5837.8  338.25  5878.2  338.28  5975.4  341.64
#Mann= 5 ,-1 , 0
  4427.1     .05       0  4952.4      .1       0  4998.8     .07       0
  5004.8      .1       0  5227.8     .05       0
Bank Sta=4998.8,5004.8
XS Rating Curve= 0 ,0
Exp/Cntr=0.3,0.1

Type RM Length L Ch R = 1 ,4905    ,1456,1456,1456
BEGIN DESCRIPTION:
UNT0494 IN WICK 6.0
END DESCRIPTION:
XS GIS Cut Line= 3
      3543880.78     10264493.45      3544123.84     10264229.56
      3544325.03     10263015.49
#Sta/Elev= 30
  4137.5  313.23  4496.3  311.46  4676.6  309.39  4798.3  306.84  4909.8  302.87
  4950.5  302.96  4980.7  302.29  5000.7   298.6  5005.8  298.78  5008.1  298.04
  5010.9  297.54  5014.1  298.04  5021.3  300.46  5031.4  302.41  5065.4  304.34
  5082.1  306.11  5102.3  307.11  5127.8  306.77    5153  307.52  5188.8  309.26
  5193.9  310.14  5234.1  311.49  5254.8  313.35  5294.9  314.32  5315.8   316.5
  5371.8   318.7  5426.7  319.65    5447  321.01  5554.7  324.63  5726.9   326.7
#Mann= 5 ,-1 , 0
  4137.5     .05       0  4950.5      .1       0  5008.1     .07       0
  5014.1      .1       0  5065.4     .05       0
Bank Sta=5008.1,5014.1
XS Rating Curve= 0 ,0
Exp/Cntr=0.3,0.1

Type RM Length L Ch R = 1 ,3449    ,1081,1081,1081
BEGIN DESCRIPTION:
UNT0494 IN WICK 4.0
END DESCRIPTION:
XS GIS Cut Line= 3
      3544929.92     10264189.89      3544902.14     10263405.14
      3544853.69     10262955.18
#Sta/Elev= 30
  4391.1   310.6  4499.4  310.74  4599.5   308.5  4689.5  307.25  4759.6  304.59
  4871.2  301.89  4919.7  300.22  4969.7  299.65  4989.7  295.56  4996.7  295.15
  4999.5  294.65  5002.7  295.15  5019.7  299.17  5059.3  303.03  5079.8  304.95
  5119.8  306.17  5175.6  309.14    5210  309.92  5219.2  310.78  5250.3  311.61
  5290.5  313.56    5381  316.25  5401.1  318.34  5451.4  318.25  5461.5  319.39
  5471.5  319.52  5505.1  319.12  5572.1  320.02  5602.3   319.4  5628.9  319.63
#Mann= 5 ,-1 , 0
  4391.1     .05       0  4871.2     .16       0  4996.7     .07       0
  5002.7     .16       0  5059.3     .05       0
Bank Sta=4996.7,5002.7
XS Rating Curve= 0 ,0
Exp/Cntr=0.3,0.1

Type RM Length L Ch R = 1 ,2368    ,1473,1473,1473
BEGIN DESCRIPTION:
UNT0494 IN WICK 3.0
END DESCRIPTION:
XS GIS Cut Line= 2
      3545506.31     10264120.38      3545416.13     10262615.08
#Sta/Elev= 30
  4483.9  307.84  4608.3  305.47    4673  305.42    4693  307.57    4703  307.38
  4755.6  301.03  4763.1   300.1  4801.6  301.47  4806.6   300.4  4823.2   300.9
  4863.3  299.15  4918.5  298.67  4975.4  298.34  5000.6  293.77  5003.3  293.27
  5006.6  293.77  5023.6  295.67  5053.7  296.22  5139.1  302.92    5254  305.71
  5308.9   308.1  5424.3  310.24  5514.5  309.02  5564.6  306.67  5594.6  306.69
  5714.8  309.51    5775  309.13  5895.2  314.84  5925.2  313.94  5991.9  315.84
#Mann= 7 ,-1 , 0
  4483.9     .05       0  4608.3      .1       0  4755.6     .05       0
  4918.5      .1       0  5000.6     .07       0  5006.6      .1       0
  5308.9     .05       0
Bank Sta=5000.6,5006.6
XS Rating Curve= 0 ,0
Exp/Cntr=0.3,0.1

Type RM Length L Ch R = 1 ,895     ,0,0,0
BEGIN DESCRIPTION:
UNT0494 IN WICK 1.0
END DESCRIPTION:
XS GIS Cut Line= 4
      3545547.42     10264111.51      3546144.68     10263958.72
      3546283.57     10263229.56      3546075.25     10262826.81
#Sta/Elev= 30
  4162.5  307.38  4544.7  304.38  4673.1  302.23  4826.9  301.73    4896  297.54
  4928.7  296.81  4972.2  292.36    4997  289.58  4999.7  289.08    5003  289.58
  5005.4   292.2  5020.3  294.39  5057.6  293.09  5109.7   296.5  5114.8  295.69
    5176  298.47  5244.3  301.55  5375.7  312.26  5427.5  314.93    5433  316.84
    5438   315.7  5458.1  318.46  5468.2  318.31  5485.1  320.05  5490.2  318.72
  5503.1  319.35    5654  321.41  5684.9  319.24  5734.8   320.1  5974.7  319.13
#Mann= 6 ,-1 , 0
  4162.5     .05       0  4972.2     .16       0    4997     .07       0
    5003     .16       0    5176      .1       0  5503.1     .05       0
Bank Sta=4997,5003
XS Rating Curve= 0 ,0
Exp/Cntr=0.3,0.1

Chan Stop Cuts=-1
Use User Specified Reach Order=0
Composite Channel Slope=5