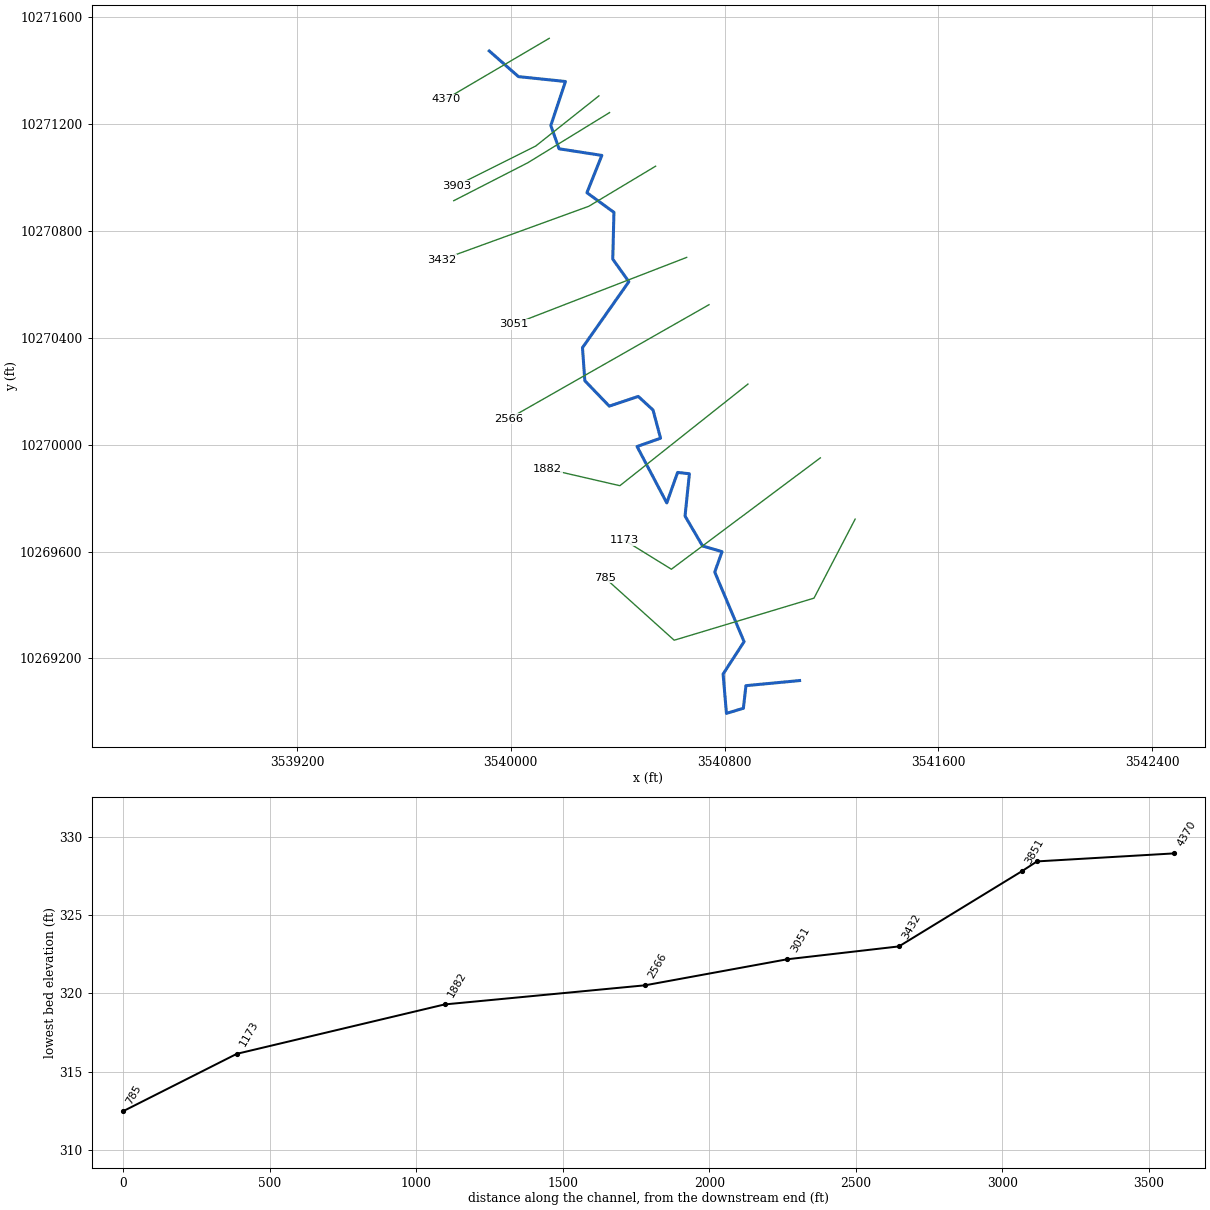
--- WICKSONCREEKTRIB.prj (project) ---

Proj Title=WICKSON CREEK TRIB 41 1
Current Plan=p01
Default Exp/Contr=0.3,0.1
English Units
Geom File=g01
Flow File=f01
Plan File=p01
Y Axis Title=Elevation
X Axis Title(PF)=Main Channel Distance
X Axis Title(XS)=Station
BEGIN DESCRIPTION:
UNT05117 IN WICK
END DESCRIPTION:
DSS Export Rating Curves= 0
DSS Export Rating Curve Sorted= 0
DSS Export Volume Flow Curves= 0
DXF OffsetX= 0
DXF OffsetY= 0
DXF ScaleX= 1
DXF ScaleY= 10

--- WICKSONCREEKTRIB.p01 (plan) ---

Plan Title=Multiple Run
Short Identifier=Multiple
Geom File=g01
Flow File=f01
Subcritical Flow
K Sum by GR= 0
Std Step Tol= 0.01
Critical Tol= 0.01
Num of Std Step Trials= 20
Max Error Tol= 0.3
Flow Tol Ratio= 0.001
Split Flow NTrial= 30
Split Flow Tol= 0.02
Split Flow Ratio= 0.02
Log Output Level= 0
Friction Slope Method= 1
Unsteady Friction Slope Method= 2
Unsteady Bridges Friction Slope Method= 1
Parabolic Critical Depth
Global Vel Dist=  1 , 1 , 1
Global Log Level= 0
CheckData=True
Encroach Param= -1, 0, 0, 0
BEGIN DESCRIPTION:
Multiple Run
END DESCRIPTION:

--- WICKSONCREEKTRIB.f01 (steady flow) ---

Flow Title=Multiple
Program Version=4.10
Number of Profiles= 7
Profile Names=10-year,25-year,50-year,1pct_min,100-year,1pct_plu,500-year
River Rch & RM=UNT05117 IN WICK,Reach-1         ,4370
     368     482     572     499     674     912     937
River Rch & RM=WICKSONCRTRB411,Reach-1         ,4370
     368     482     572     499     674     912     937
Boundary for River Rch & Prof#=WICKSONCRTRB411,Reach-1         , 1
Up Type= 0
Dn Type= 3
Dn Slope=0.005
Boundary for River Rch & Prof#=WICKSONCRTRB411,Reach-1         , 2
Up Type= 0
Dn Type= 3
Dn Slope=0.005
Boundary for River Rch & Prof#=WICKSONCRTRB411,Reach-1         , 3
Up Type= 0
Dn Type= 3
Dn Slope=0.005
Boundary for River Rch & Prof#=WICKSONCRTRB411,Reach-1         , 4
Up Type= 0
Dn Type= 3
Dn Slope=0.005
Boundary for River Rch & Prof#=WICKSONCRTRB411,Reach-1         , 5
Up Type= 0
Dn Type= 3
Dn Slope=0.005
Boundary for River Rch & Prof#=WICKSONCRTRB411,Reach-1         , 6
Up Type= 0
Dn Type= 3
Dn Slope=0.005
Boundary for River Rch & Prof#=WICKSONCRTRB411,Reach-1         , 7
Up Type= 0
Dn Type= 3
Dn Slope=0.005
DSS Import GetInterval= 0
DSS Import GetPeak= 0
DSS Import FillOption= 0

--- WICKSONCREEKTRIB.g01 (geometry) ---

Geom Title=Existing Conditions
Program Version=4.10

River Reach=WICKSONCRTRB411 ,Reach-1
Reach XY= 30
      3539919.63     10271472.66      3540028.88     10271376.61
      3540204.66     10271358.38      3540149.89     10271193.88
      3540180.79     10271106.64      3540340.82     10271081.89
      3540285.01     10270942.33      3540386.08     10270868.92
      3540381.74     10270693.88      3540441.92     10270609.53
      3540268.46     10270362.72      3540277.14     10270239.02
      3540368.64     10270143.88      3540477.16     10270180.21
      3540532.28     10270129.43      3540560.49     10270023.96
      3540472.64     10269992.74      3540583.73     10269781.78
      3540624.29     10269895.92      3540668.42     10269890.93
      3540652.07     10269732.73      3540717.61     10269620.75
      3540790.53     10269599.48      3540763.18     10269523.09
      3540872.99     10269262.67      3540794.43     10269141.58
      3540807.02     10268994.45      3540870.39     10269013.54
      3540879.94     10269098.18      3541080.69     10269117.18

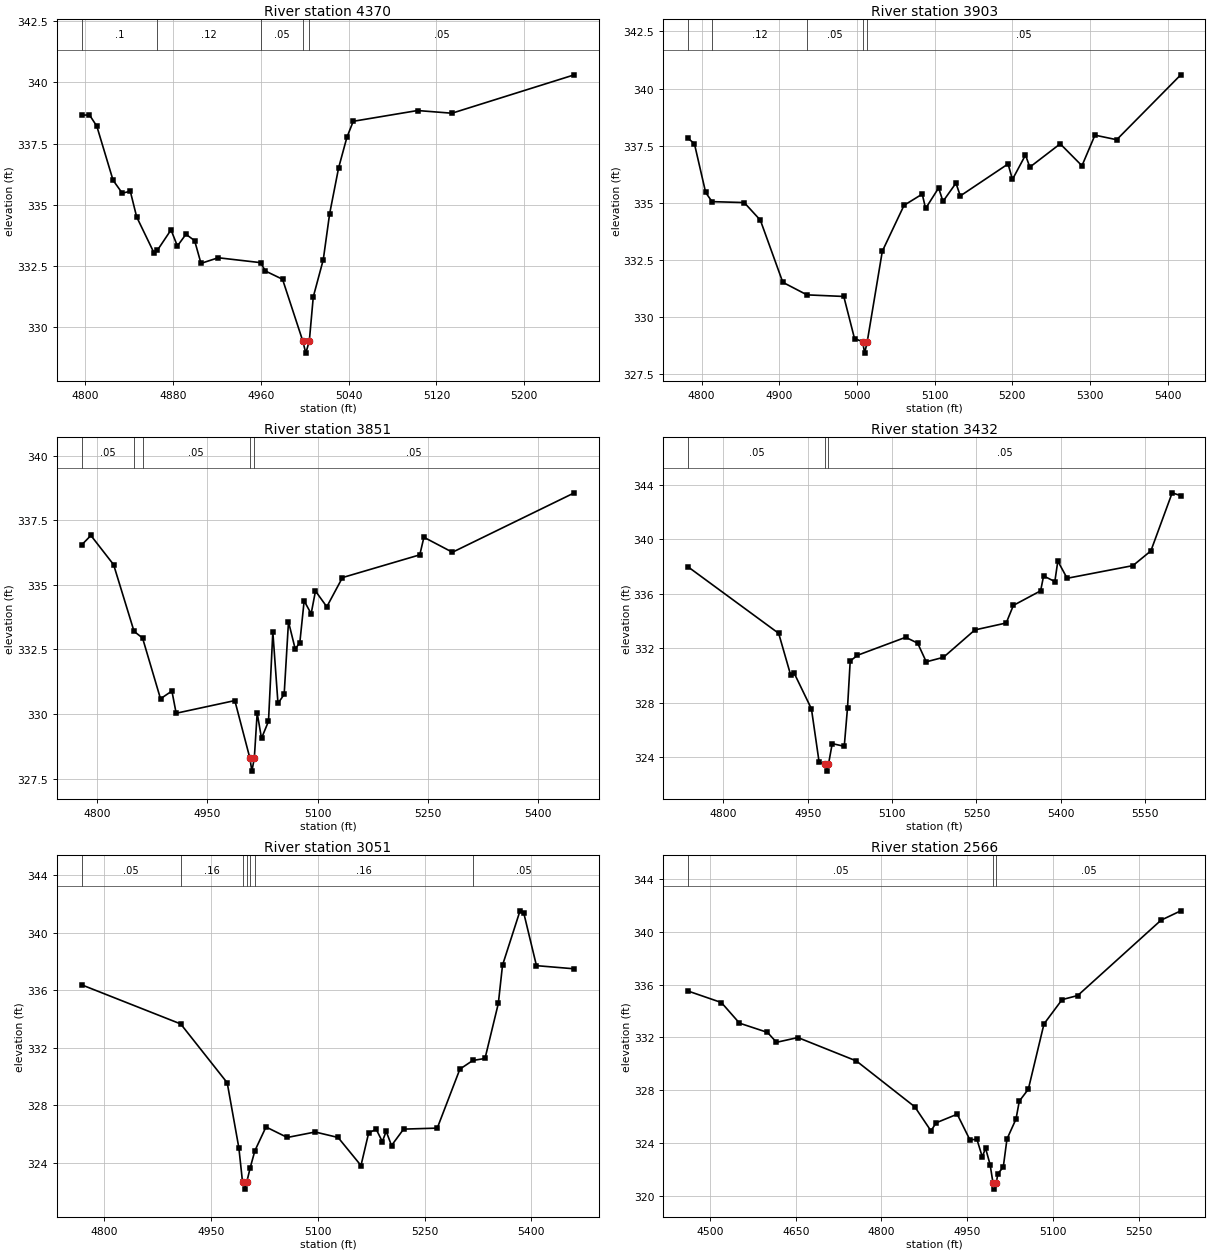
Type RM Length L Ch R = 1 ,4370    ,467,467,467
BEGIN DESCRIPTION:
UNT05117 IN WICK 7.0
END DESCRIPTION:
XS GIS Cut Line= 2
      3540144.08     10271519.88      3539757.02     10271292.51
#Sta/Elev= 30
  4796.7  338.66  4803.9  338.67  4810.6  338.21  4825.4     336  4833.8  335.47
  4841.1  335.55  4846.9   334.5  4862.6  333.04  4865.7  333.13  4878.2  333.97
    4884  333.31  4891.8  333.79  4899.7  333.53  4905.5   332.6  4921.2  332.83
  4959.8  332.63  4964.1  332.29  4979.8  331.95  4998.2  329.43    5001  328.93
  5004.2  329.43  5007.8  331.23  5016.9  332.75  5022.7  334.63  5030.9  336.51
  5038.4  337.75  5044.2  338.41  5102.8  338.85  5134.1  338.74  5245.6  340.31
#Mann= 5 ,-1 , 0
  4796.7      .1       0  4865.7     .12       0  4959.8     .05       0
  4998.2     .03       0  5004.2     .05       0
Bank Sta=4998.2,5004.2
XS Rating Curve= 0 ,0
Exp/Cntr=0.3,0.1

Type RM Length L Ch R = 1 ,3903    ,52,52,52
BEGIN DESCRIPTION:
Mapping XS 773426ad
END DESCRIPTION:
XS GIS Cut Line= 3
      3540329.91     10271304.65      3540093.76     10271117.12
      3539796.14     10270968.31
#Sta/Elev= 30
  4782.6  337.82  4790.8  337.59  4805.3  335.45  4813.5  335.05  4854.9  335.01
  4875.7  334.24  4904.6  331.52  4935.7  330.97  4983.1   330.9  4996.9  329.06
  5007.3  328.92    5010  328.42  5013.3  328.92  5032.7  332.88  5060.7  334.89
  5084.1  335.38  5088.4  334.75  5105.2  335.65  5110.8  335.06  5127.5  335.86
  5133.1   335.3  5194.6   336.7  5200.2  336.02    5217  337.09  5222.6  336.56
  5261.7  337.58  5289.7  336.62  5306.4  337.96  5334.4  337.76  5416.9   340.6
#Mann= 5 ,-1 , 0
  4782.6     .05       0  4813.5     .12       0  4935.7     .05       0
  5007.3     .03       0  5013.3     .05       0
Bank Sta=5007.3,5013.3
XS Rating Curve= 0 ,0
Exp/Cntr=0.3,0.1

Type RM Length L Ch R = 1 ,3851    ,419,419,419
BEGIN DESCRIPTION:
Mapping XS 60086fef
END DESCRIPTION:
XS GIS Cut Line= 3
      3540369.82     10271242.13      3540064.25     10271054.62
      3539786.78     10270912.42
#Sta/Elev= 30
  4778.8  336.54  4791.5  336.91  4822.4  335.78  4850.2   333.2  4861.8  332.94
  4886.2  330.59  4901.7  330.89  4907.5  330.03  4987.3  330.52  5007.8  328.29
  5010.5  327.79  5013.8  328.29  5017.7  330.04  5023.6  329.06  5033.1  329.72
    5039  333.18    5046  330.41  5054.4  330.76  5060.3  333.57  5069.4  332.52
  5075.7  332.76  5081.6  334.38  5091.1  333.88    5097  334.76  5112.4  334.15
  5133.7  335.28  5238.9  336.16  5244.5  336.84  5283.3  336.26  5449.1  338.56
#Mann= 5 ,-1 , 0
  4778.8     .05       0  4850.2     .12       0  4861.8     .05       0
  5007.8     .03       0  5013.8     .05       0
Bank Sta=5007.8,5013.8
XS Rating Curve= 0 ,0
Exp/Cntr=0.3,0.1

Type RM Length L Ch R = 1 ,3432    ,381,381,381
BEGIN DESCRIPTION:
UNT05117 IN WICK 6.0
END DESCRIPTION:
XS GIS Cut Line= 3
      3540542.12     10271041.65      3540292.11     10270891.64
       3539742.1     10270691.64
#Sta/Elev= 30
  4736.9  337.99  4898.2  333.11  4919.6  330.04  4925.4  330.22  4956.5  327.57
  4970.2  323.65  4980.8   323.5  4983.5     323  4986.8   323.5  4993.5  325.02
  5014.9  324.82  5020.7  327.65  5025.5  331.08  5038.4   331.5  5124.2  332.82
  5145.5  332.39  5160.8  331.02  5191.4  331.35  5247.3  333.36  5303.1  333.87
  5315.8  335.16  5364.3  336.23  5369.6  337.32  5389.6  336.91  5394.9  338.41
  5411.5  337.15  5528.6  338.08  5560.5  339.16  5598.4  343.42  5613.7  343.21
#Mann= 3 ,-1 , 0
  4736.9     .05       0  4980.8    .035       0  4986.8     .05       0
Bank Sta=4980.8,4986.8
XS Rating Curve= 0 ,0
Exp/Cntr=0.3,0.1

Type RM Length L Ch R = 1 ,3051    ,485,485,485
BEGIN DESCRIPTION:
UNT05117 IN WICK 5.0
END DESCRIPTION:
XS GIS Cut Line= 2
      3540658.31     10270700.39      3540012.51      10270450.4
#Sta/Elev= 30
  4767.9  336.38  4907.2  333.66  4972.6  329.57    4989  325.04  4994.1  322.68
  4996.9  322.18  5000.1  322.68    5005  323.68  5011.5  324.85  5027.1   326.5
    5057  325.77  5096.2  326.15  5128.4  325.77  5160.6  323.82  5171.4  326.09
    5182  326.34  5190.6  325.48    5196   326.2  5203.5  325.21  5220.5  326.35
  5267.8  326.42  5299.6  330.52  5317.7  331.12  5334.9  331.26  5353.6  335.08
  5359.5  337.74  5384.1  341.52  5389.4  341.36  5407.2  337.71  5460.4  337.49
#Mann= 7 ,-1 , 0
  4767.9     .05       0  4907.2     .16       0  4994.1     .07       0
  5000.1     .16       0    5005     .05       0  5011.5     .16       0
  5317.7     .05       0
Bank Sta=4994.1,5000.1
XS Rating Curve= 0 ,0
Exp/Cntr=0.3,0.1

Type RM Length L Ch R = 1 ,2566    ,684,684,684
BEGIN DESCRIPTION:
UNT05117 IN WICK 4.0
END DESCRIPTION:
XS GIS Cut Line= 2
      3540741.68     10270523.32        3539992.     10270096.42
#Sta/Elev= 30
  4461.3  335.51  4519.7  334.64  4551.4  333.08  4600.4  332.38  4616.2  331.63
  4653.7  331.99    4756  330.22  4858.3  326.75  4886.6  324.93  4895.8  325.54
  4932.6  326.19  4954.8  324.25  4967.1  324.29  4976.5  322.96  4982.2  323.62
  4990.2  322.37  4995.1  321.02  4997.8  320.52  5001.1  321.02  5003.8  321.69
  5013.2  322.18  5019.7  324.31  5035.5  325.82  5041.3  327.18  5057.1  328.08
  5084.5  333.02  5116.2  334.86  5143.6  335.17  5289.4  340.87    5324  341.58
#Mann= 3 ,-1 , 0
  4461.3     .05       0  4995.1     .03       0  5001.1     .05       0
Bank Sta=4995.1,5001.1
XS Rating Curve= 0 ,0
Exp/Cntr=0.3,0.1

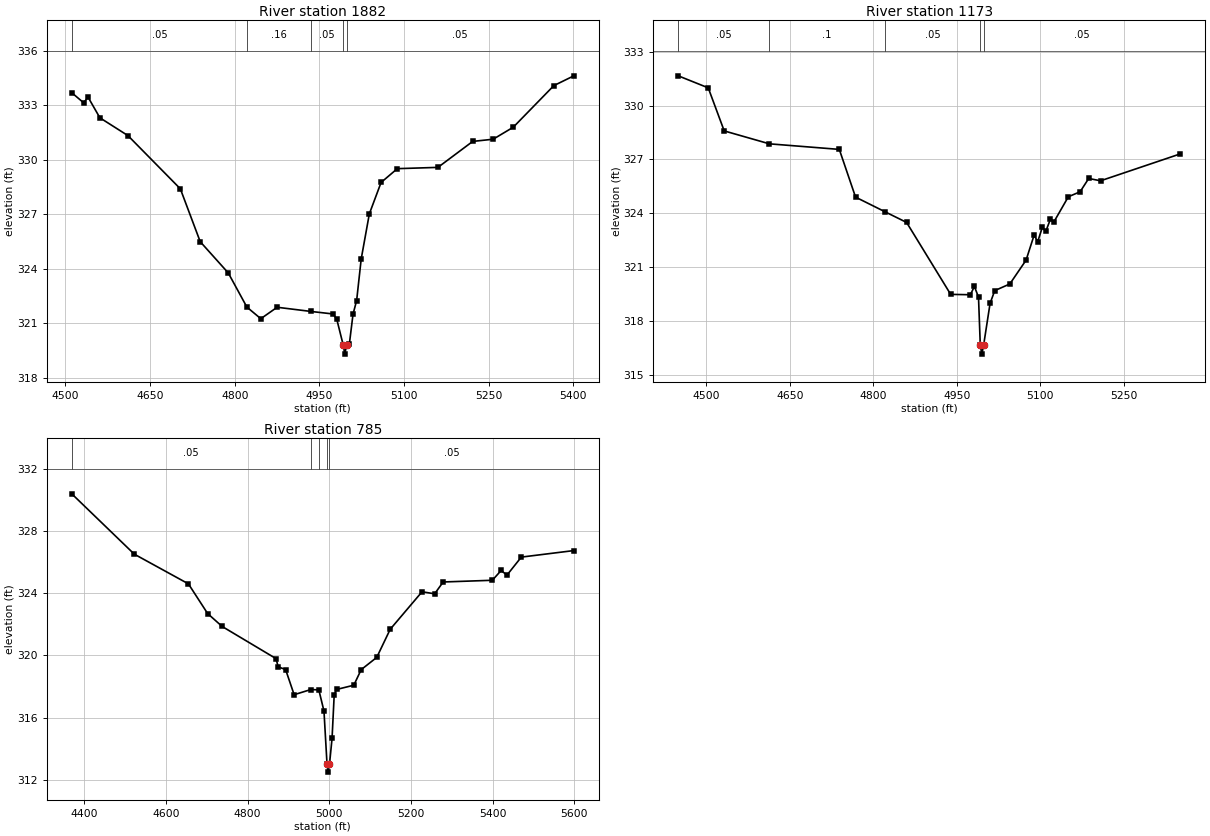
Type RM Length L Ch R = 1 ,1882    ,709,709,709
BEGIN DESCRIPTION:
UNT05117 IN WICK 3.0
END DESCRIPTION:
XS GIS Cut Line= 3
      3540887.53     10270226.47      3540408.33     10269846.23
      3540137.48     10269908.73
#Sta/Elev= 30
  4511.2  333.69  4532.1  333.14  4540.2  333.44    4561  332.31  4610.7  331.33
  4703.6   328.4  4738.8  325.49  4788.5  323.77  4821.5  321.89  4846.2  321.25
  4875.1  321.88    4935  321.65  4974.4  321.51  4980.8  321.22  4992.2   319.8
    4995   319.3  4998.2   319.8  5003.2  319.88  5009.6   321.5    5016  322.25
  5024.1  324.54  5038.5  327.02  5059.3  328.75  5088.1  329.51  5160.1  329.58
  5221.7  331.01  5257.9  331.13  5293.5  331.79  5365.4  334.08  5400.9  334.62
#Mann= 5 ,-1 , 0
  4511.2     .05       0  4821.5     .16       0    4935     .05       0
  4992.2     .03       0  4998.2     .05       0
Bank Sta=4992.2,4998.2
XS Rating Curve= 0 ,0
Exp/Cntr=0.3,0.1

Type RM Length L Ch R = 1 ,1173    ,388,388,388
BEGIN DESCRIPTION:
UNT05117 IN WICK 2.0
END DESCRIPTION:
XS GIS Cut Line= 3
      3541158.29     10269950.37      3540601.04     10269533.73
      3540425.51     10269642.14
#Sta/Elev= 30
  4449.7  331.66  4503.6  330.99  4532.3  328.59  4613.5  327.87  4739.1  327.56
  4768.3   324.9  4820.8  324.09    4860  323.49  4939.2  319.48  4974.6  319.46
  4981.8  319.92  4989.2  319.33  4992.4  316.65  4995.2  316.15  4998.4  316.65
    5010  318.98  5018.4  319.69  5045.5  320.06  5074.7  321.39  5089.2  322.79
  5095.5  322.41  5103.8  323.21  5110.1  322.99  5118.4  323.67  5124.7  323.52
  5150.6  324.92  5171.8   325.2  5187.2  325.94  5208.5  325.81  5351.8  327.31
#Mann= 5 ,-1 , 0
  4449.7     .05       0  4613.5      .1       0  4820.8     .05       0
  4992.4    .035       0  4998.4     .05       0
Bank Sta=4992.4,4998.4
XS Rating Curve= 0 ,0
Exp/Cntr=0.3,0.1

Type RM Length L Ch R = 1 ,785     ,0,0,0
BEGIN DESCRIPTION:
UNT05117 IN WICK 1.0
END DESCRIPTION:
XS GIS Cut Line= 4
      3541288.52      10269721.2      3541134.47     10269425.53
      3540611.45      10269268.1      3540351.07     10269502.45
#Sta/Elev= 30
  4369.3  330.39  4522.4  326.51    4655   324.6  4702.1  322.69  4737.6  321.86
  4869.7  319.79  4874.9  319.26  4893.1  319.09    4914  317.47  4954.7   317.8
  4974.5  317.78  4987.1  316.42  4994.6  312.99  4997.3  312.49  5000.6  312.99
  5006.9  314.66  5012.2  317.48  5018.5  317.81  5060.2  318.08  5078.2  319.08
  5116.4  319.87  5149.4  321.68  5227.3  324.09  5258.2  323.96  5279.1  324.72
  5399.5  324.83  5421.1  325.46  5435.3  325.16  5470.5  326.32  5599.2  326.74
#Mann= 5 ,-1 , 0
  4369.3     .05       0  4954.7     .16       0  4974.5     .05       0
  4994.6    .035       0  5000.6     .05       0
Bank Sta=4994.6,5000.6
XS Rating Curve= 0 ,0
Exp/Cntr=0.3,0.1

Chan Stop Cuts=-1
Use User Specified Reach Order=0
Composite Channel Slope=5