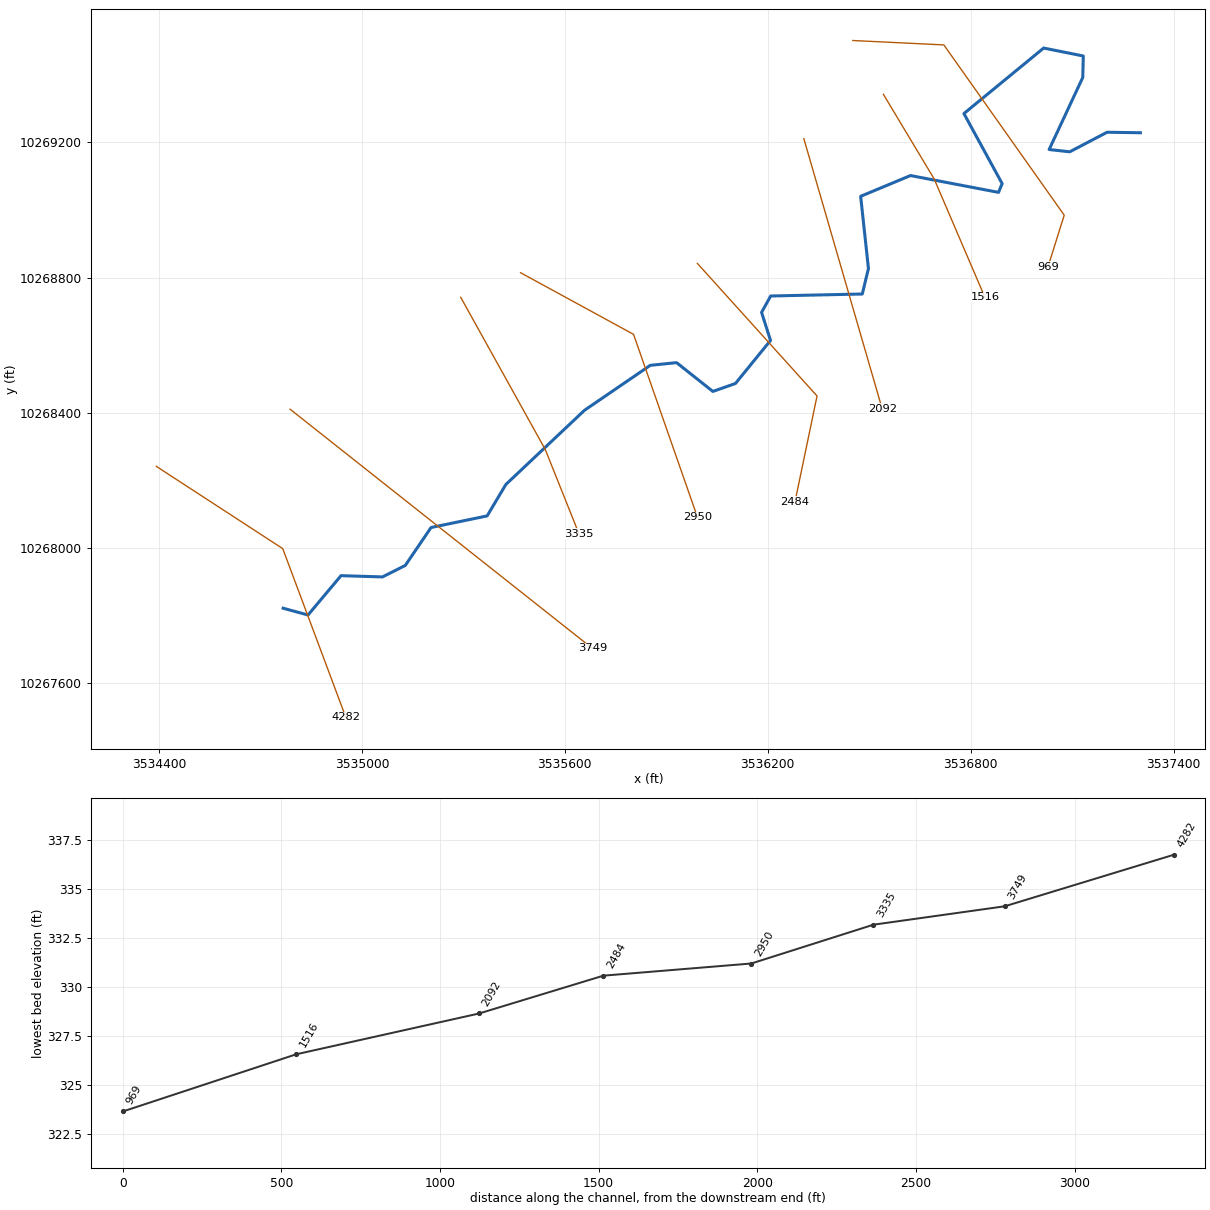
--- WICKSONCREEKTRIB.prj (project) ---

Proj Title=WICKSON CREEK TRIB 41 2
Current Plan=p01
Default Exp/Contr=0.3,0.1
English Units
Geom File=g01
Flow File=f01
Plan File=p01
Y Axis Title=Elevation
X Axis Title(PF)=Main Channel Distance
X Axis Title(XS)=Station
BEGIN DESCRIPTION:
UNT05115 IN WICK
END DESCRIPTION:
DSS Export Rating Curves= 0
DSS Export Rating Curve Sorted= 0
DSS Export Volume Flow Curves= 0
DXF OffsetX= 0
DXF OffsetY= 0
DXF ScaleX= 1
DXF ScaleY= 10

--- WICKSONCREEKTRIB.p01 (plan) ---

Plan Title=Multiple Run
Short Identifier=Multiple
Geom File=g01
Flow File=f01
Subcritical Flow
K Sum by GR= 0
Std Step Tol= 0.01
Critical Tol= 0.01
Num of Std Step Trials= 20
Max Error Tol= 0.3
Flow Tol Ratio= 0.001
Split Flow NTrial= 30
Split Flow Tol= 0.02
Split Flow Ratio= 0.02
Log Output Level= 0
Friction Slope Method= 1
Unsteady Friction Slope Method= 2
Unsteady Bridges Friction Slope Method= 1
Parabolic Critical Depth
Global Vel Dist=  1 , 1 , 1
Global Log Level= 0
CheckData=True
Encroach Param= -1, 0, 0, 0
BEGIN DESCRIPTION:
Multiple Run
END DESCRIPTION:

--- WICKSONCREEKTRIB.f01 (steady flow) ---

Flow Title=Multiple
Program Version=4.10
Number of Profiles= 7
Profile Names=10-year,25-year,50-year,1pct_min,100-year,1pct_plu,500-year
River Rch & RM=UNT05115 IN WICK,Reach-1         ,4282
     435     574     685     599     809    1095    1133
River Rch & RM=WICKSONCRTRB412,Reach-1         ,4282
     435     574     685     599     809    1095    1133
Boundary for River Rch & Prof#=WICKSONCRTRB412,Reach-1         , 1
Up Type= 0
Dn Type= 3
Dn Slope=0.005
Boundary for River Rch & Prof#=WICKSONCRTRB412,Reach-1         , 2
Up Type= 0
Dn Type= 3
Dn Slope=0.005
Boundary for River Rch & Prof#=WICKSONCRTRB412,Reach-1         , 3
Up Type= 0
Dn Type= 3
Dn Slope=0.005
Boundary for River Rch & Prof#=WICKSONCRTRB412,Reach-1         , 4
Up Type= 0
Dn Type= 3
Dn Slope=0.005
Boundary for River Rch & Prof#=WICKSONCRTRB412,Reach-1         , 5
Up Type= 0
Dn Type= 3
Dn Slope=0.005
Boundary for River Rch & Prof#=WICKSONCRTRB412,Reach-1         , 6
Up Type= 0
Dn Type= 3
Dn Slope=0.005
Boundary for River Rch & Prof#=WICKSONCRTRB412,Reach-1         , 7
Up Type= 0
Dn Type= 3
Dn Slope=0.005
DSS Import GetInterval= 0
DSS Import GetPeak= 0
DSS Import FillOption= 0

--- WICKSONCREEKTRIB.g01 (geometry) ---

Geom Title=Existing Conditions
Program Version=4.10

River Reach=WICKSONCRTRB412 ,Reach-1
Reach XY= 30
      3534767.05      10267822.2      3534840.65     10267802.11
      3534938.22     10267918.43      3535060.81     10267914.68
      3535128.23     10267948.63      3535204.54     10268060.79
      3535370.25      10268095.1      3535425.74     10268188.14
      3535658.06     10268407.34      3535852.77     10268540.37
      3535930.53     10268548.32      3536037.83     10268463.17
       3536104.7     10268486.79      3536208.25     10268614.02
      3536181.81     10268697.02      3536208.77     10268745.39
      3536479.67     10268751.28      3536497.82     10268826.67
      3536474.81     10269040.17      3536622.15     10269101.53
      3536882.47      10269051.8      3536893.14     10269077.75
      3536780.13     10269284.85      3537015.96     10269478.54
      3537133.14      10269455.1      3537131.58     10269391.56
       3537032.1     10269178.54      3537093.04     10269171.77
      3537203.46     10269229.58      3537301.99     10269228.08

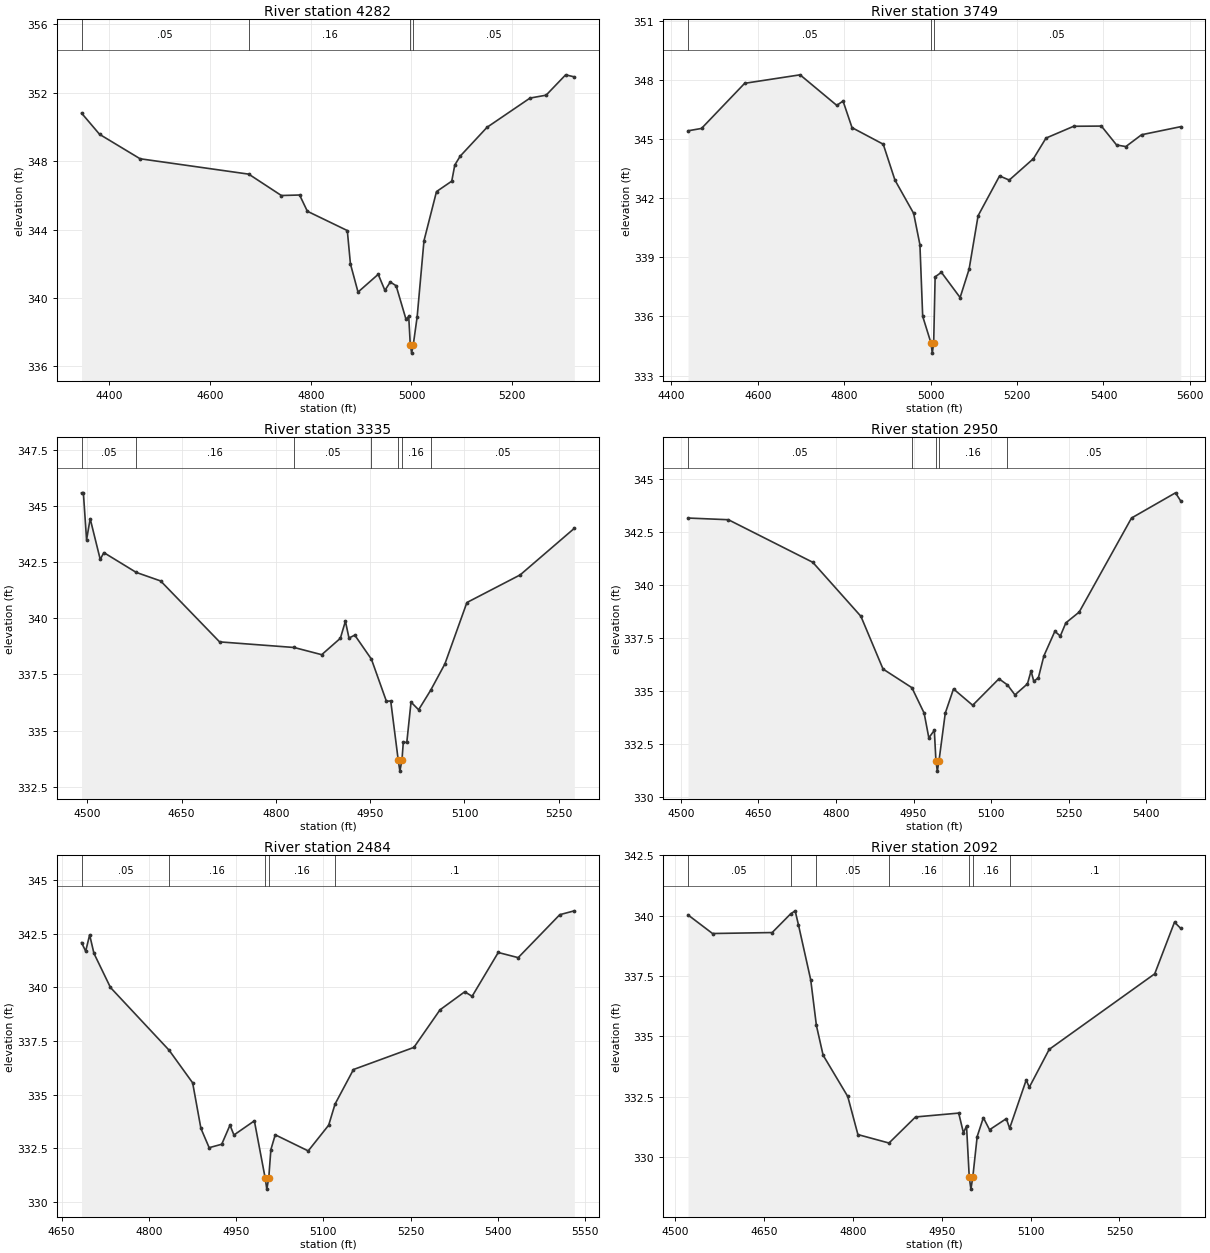
Type RM Length L Ch R = 1 ,4282    ,533,533,533
BEGIN DESCRIPTION:
UNT05115 IN WICK 8.0
END DESCRIPTION:
XS GIS Cut Line= 3
      3534392.07     10268241.67      3534765.97     10267998.31
       3534952.6     10267499.18
#Sta/Elev= 30
  4344.5  350.81  4380.3  349.57  4460.8  348.14  4676.7  347.24  4741.5  345.99
  4777.7  346.02  4793.1  345.07  4872.5  343.94  4878.7  341.99  4893.8  340.34
  4933.9  341.38  4947.2  340.44  4957.9  340.93  4969.5  340.71  4989.2  338.74
  4994.5  338.92  4997.6  337.27  5000.3  336.77  5003.6  337.27  5011.3   338.9
  5024.8  343.34  5049.7  346.22    5080  346.83    5086  347.77  5096.7  348.29
  5150.1  349.98  5235.5  351.69  5267.5  351.86  5306.3  353.05  5323.5  352.93
#Mann= 4 ,-1 , 0
  4344.5     .05       0  4676.7     .16       0  4997.6     .03       0
  5003.6     .05       0
Bank Sta=4997.6,5003.6
XS Rating Curve= 0 ,0
Exp/Cntr=0.3,0.1

Type RM Length L Ch R = 1 ,3749    ,414,414,414
BEGIN DESCRIPTION:
UNT05115 IN WICK 7.0
END DESCRIPTION:
XS GIS Cut Line= 2
      3534787.65     10268410.65       3535681.8     10267703.15
#Sta/Elev= 30
  4438.7  345.42  4469.9  345.54  4569.8  347.83    4698  348.26  4782.9  346.71
  4797.4  346.93  4818.2  345.58  4890.4  344.74  4917.5  342.92  4960.8  341.23
  4975.3  339.64  4981.7  336.01  5001.1  334.64  5003.9  334.14  5007.1  334.64
  5010.5  338.01    5025  338.24  5068.3  336.96  5089.1   338.4  5109.9  341.11
  5159.6  343.13    5182  342.92  5238.1  344.01    5267  345.05  5331.1  345.65
  5395.2  345.66  5430.4   344.7  5451.8  344.62  5488.2  345.22  5578.9  345.63
#Mann= 3 ,-1 , 0
  4438.7     .05       0  5001.1    .035       0  5007.1     .05       0
Bank Sta=5001.1,5007.1
XS Rating Curve= 0 ,0
Exp/Cntr=0.3,0.1

Type RM Length L Ch R = 1 ,3335    ,385,385,385
BEGIN DESCRIPTION:
UNT05115 IN WICK 6.0
END DESCRIPTION:
XS GIS Cut Line= 3
      3535292.11     10268741.64      3535542.11     10268291.64
      3535642.09     10268041.67
#Sta/Elev= 30
  4490.8  345.58  4493.7  345.58  4498.8  343.49  4504.5  344.43  4520.5  342.62
  4526.3  342.92  4577.8  342.04  4616.6  341.66  4710.4  338.95    4829   338.7
  4872.9  338.38  4902.6  339.11  4910.6  339.87  4916.3  339.12  4925.5  339.25
    4952  338.18  4975.8  336.31  4982.7  336.32  4994.6   333.7  4997.3   333.2
  5000.6   333.7  5002.7  334.48  5008.3  334.48    5015  336.27  5027.1  335.93
  5046.3   336.8  5068.9  337.97  5103.9   340.7  5188.7  341.93  5274.8     344
#Mann= 7 ,-1 , 0
  4490.8     .05       0  4577.8     .16       0    4829     .05       0
    4952     .16       0  4994.6     .07       0  5000.6     .16       0
  5046.3     .05       0
Bank Sta=4994.6,5000.6
XS Rating Curve= 0 ,0
Exp/Cntr=0.3,0.1

Type RM Length L Ch R = 1 ,2950    ,466,466,466
BEGIN DESCRIPTION:
UNT05115 IN WICK 5.0
END DESCRIPTION:
XS GIS Cut Line= 3
      3535469.06      10268814.3      3535803.29     10268631.99
       3535992.1     10268091.65
#Sta/Elev= 30
  4513.8  343.17  4591.9  343.09  4755.1  341.08  4848.2  338.53    4891  336.04
  4946.8  335.16  4970.5  333.96  4979.6  332.79  4990.2  333.15  4993.3  331.72
    4996  331.22  4999.3  331.72  5011.4  333.96  5027.3   335.1  5064.4  334.33
  5115.2  335.58  5131.7  335.29  5146.2  334.82  5170.3  335.34  5177.3  335.95
  5182.6  335.46  5191.5  335.63  5202.1  336.66  5223.3  337.82  5233.9   337.6
  5244.6  338.22  5270.4  338.73  5371.6  343.17  5456.7  344.36  5466.9  343.97
#Mann= 5 ,-1 , 0
  4513.8     .05       0  4946.8     .16       0  4993.3     .07       0
  4999.3     .16       0  5131.7     .05       0
Bank Sta=4993.3,4999.3
XS Rating Curve= 0 ,0
Exp/Cntr=0.3,0.1

Type RM Length L Ch R = 1 ,2484    ,392,392,392
BEGIN DESCRIPTION:
UNT05115 IN WICK 4.0
END DESCRIPTION:
XS GIS Cut Line= 3
      3535992.09     10268841.66      3536345.83      10268449.7
      3536280.72     10268137.19
#Sta/Elev= 30
  4684.3  342.08  4691.4  341.68  4698.2  342.44  4705.6  341.58    4734  339.99
  4834.8  337.07  4875.3  335.55  4889.5  333.43  4903.7  332.53  4925.3  332.69
  4939.5  333.58  4946.3  333.12  4981.4  333.78  5000.1   331.1  5002.8   330.6
  5006.1   331.1  5009.8  332.44  5017.3  333.13    5074  332.38  5109.2  333.58
  5120.1  334.56  5151.8  336.17  5255.7   337.2  5300.6  338.95  5343.1  339.79
  5355.8  339.58  5400.7  341.62    5435  341.38  5506.5  343.38  5531.5  343.56
#Mann= 5 ,-1 , 0
  4684.3     .05       0  4834.8     .16       0  5000.1     .07       0
  5006.1     .16       0  5120.1      .1       0
Bank Sta=5000.1,5006.1
XS Rating Curve= 0 ,0
Exp/Cntr=0.3,0.1

Type RM Length L Ch R = 1 ,2092    ,576,576,576
BEGIN DESCRIPTION:
UNT05115 IN WICK 3.0
END DESCRIPTION:
XS GIS Cut Line= 2
       3536306.8     10269210.67      3536538.49     10268411.48
#Sta/Elev= 30
  4521.5  340.03  4562.9  339.26  4663.6   339.3  4694.6  340.07  4702.4   340.2
  4707.9  339.63  4728.7  337.34  4738.3  335.45  4749.6  334.22  4791.2  332.51
  4808.4  330.93  4860.9  330.58  4905.7  331.66  4978.6  331.82  4986.6     331
  4991.8  331.29  4996.4  329.17  4999.2  328.67  5002.4  329.17  5009.8  330.85
  5020.2  331.63  5030.7  331.13    5059  331.59  5064.6  331.19  5092.6  333.19
  5097.8  332.89  5131.4  334.46  5309.6  337.59    5343  339.73  5353.6  339.47
#Mann= 7 ,-1 , 0
  4521.5     .05       0  4694.6     .16       0  4738.3     .05       0
  4860.9     .16       0  4996.4     .07       0  5002.4     .16       0
  5064.6      .1       0
Bank Sta=4996.4,5002.4
XS Rating Curve= 0 ,0
Exp/Cntr=0.3,0.1

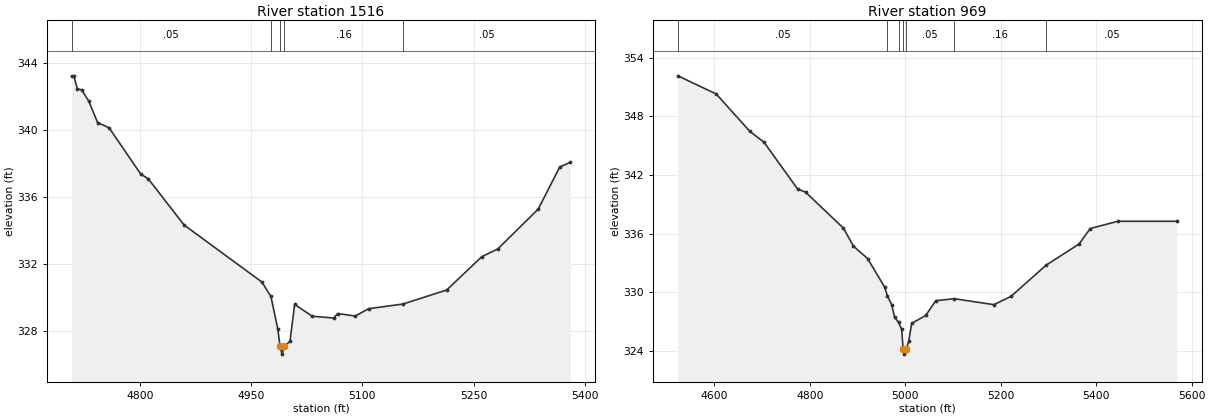
Type RM Length L Ch R = 1 ,1516    ,547,547,547
BEGIN DESCRIPTION:
UNT05115 IN WICK 2.0
END DESCRIPTION:
XS GIS Cut Line= 3
      3536542.11     10269341.64      3536692.11     10269091.64
      3536842.09     10268741.67
#Sta/Elev= 30
  4708.2  343.25  4711.1  343.25    4716  342.47  4721.8  342.41  4731.5  341.72
  4743.2  340.45  4758.7  340.14  4801.5  337.36  4811.2   337.1  4859.8  334.32
  4964.8   330.9  4976.8  330.04  4986.1  328.09    4989  327.09  4991.7  326.59
    4995  327.09  5002.5  327.35  5008.8  329.57  5032.4  328.86  5061.4  328.75
  5066.8  329.02  5090.4  328.87  5108.5  329.31  5154.9  329.59  5213.7  330.43
  5260.9  332.42  5282.6  332.89    5337  335.27    5366  337.79  5380.5  338.08
#Mann= 5 ,-1 , 0
  4708.2     .05       0  4976.8     .16       0    4989     .07       0
    4995     .16       0  5154.9     .05       0
Bank Sta=4989,4995
XS Rating Curve= 0 ,0
Exp/Cntr=0.3,0.1

Type RM Length L Ch R = 1 ,969     ,0,0,0
BEGIN DESCRIPTION:
UNT05115 IN WICK 1.0
END DESCRIPTION:
XS GIS Cut Line= 4
      3536451.68     10269500.84       3536720.8     10269487.82
       3537076.7     10268984.35      3537028.97     10268832.47
#Sta/Elev= 30
  4523.6  352.14  4604.1  350.28  4674.2  346.47  4704.2  345.34  4774.3  340.57
  4791.2  340.24  4870.6  336.55  4891.5  334.71  4921.1  333.45  4956.8  330.53
  4962.5  329.65  4971.6  328.72  4977.7  327.45    4986  326.91  4992.5   326.2
  4995.6  324.17  4998.3  323.67  5001.6  324.17  5007.3  324.97  5013.4  326.81
    5043  327.63  5063.9  329.13  5102.6  329.34  5185.7  328.73  5221.4  329.57
  5295.1  332.77  5364.2  334.94  5387.6  336.52  5445.4  337.26  5568.8  337.26
#Mann= 7 ,-1 , 0
  4523.6     .05       0  4962.5     .16       0    4986     .05       0
  4995.6     .03       0  5001.6     .05       0  5102.6     .16       0
  5295.1     .05       0
Bank Sta=4995.6,5001.6
XS Rating Curve= 0 ,0
Exp/Cntr=0.3,0.1

Chan Stop Cuts=-1
Use User Specified Reach Order=0
Composite Channel Slope=5