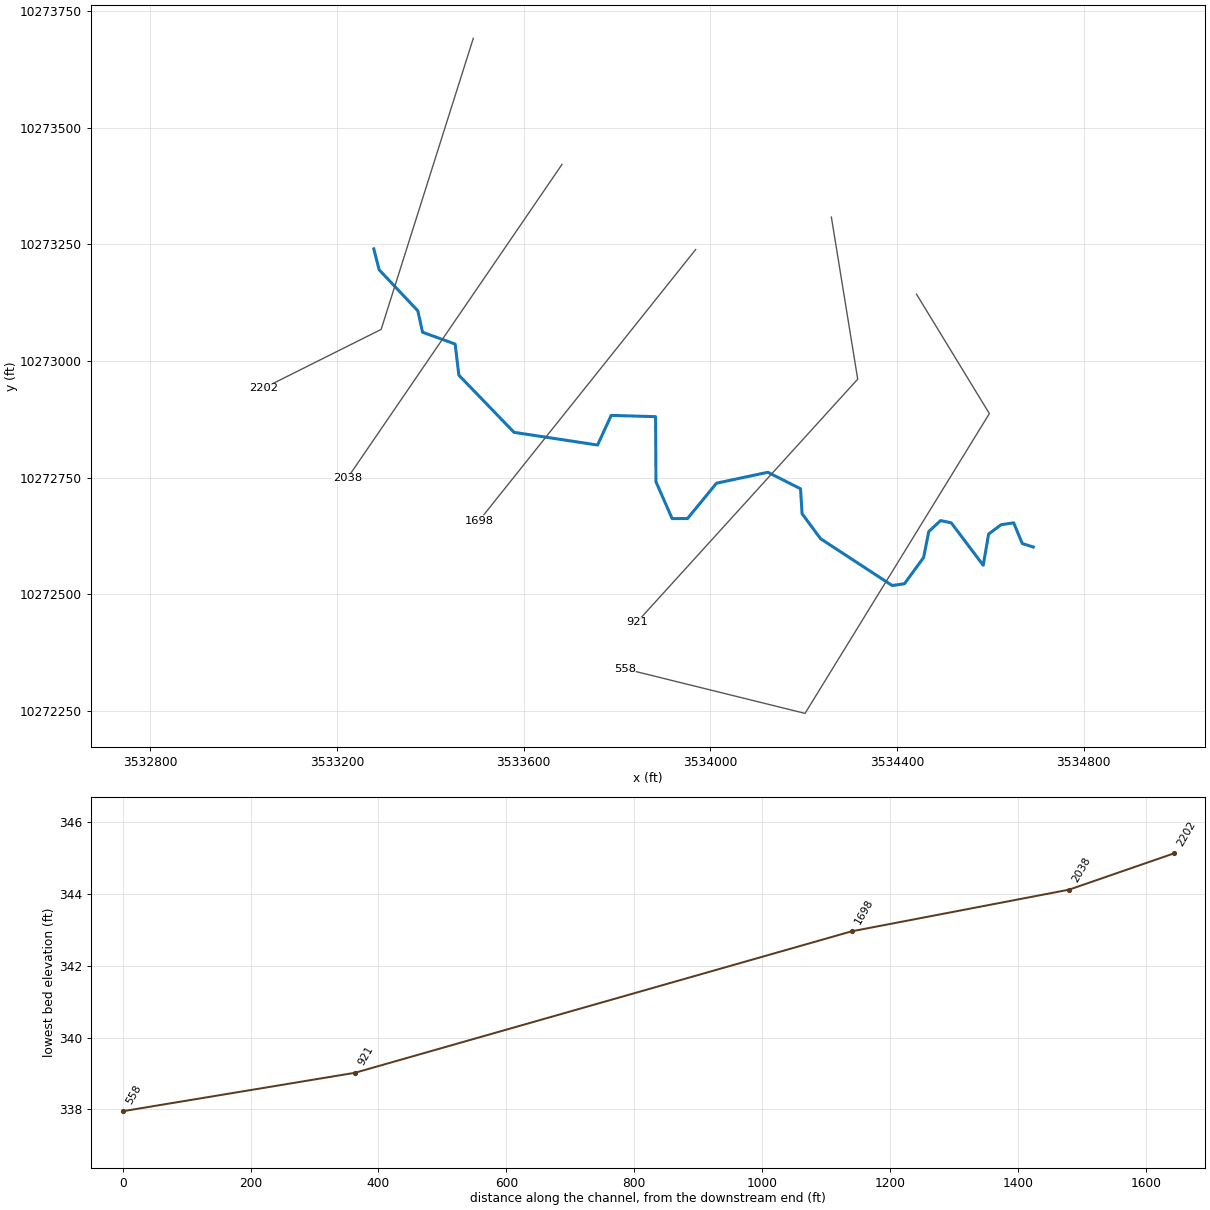
--- WICKSONCREEKTRIB.prj (project) ---

Proj Title=WICKSON CREEK TRIB 41 3 1
Current Plan=p01
Default Exp/Contr=0.3,0.1
English Units
Geom File=g01
Flow File=f01
Plan File=p01
Y Axis Title=Elevation
X Axis Title(PF)=Main Channel Distance
X Axis Title(XS)=Station
BEGIN DESCRIPTION:
UNT1527 IN WICK
END DESCRIPTION:
DSS Export Rating Curves= 0
DSS Export Rating Curve Sorted= 0
DSS Export Volume Flow Curves= 0
DXF OffsetX= 0
DXF OffsetY= 0
DXF ScaleX= 1
DXF ScaleY= 10

--- WICKSONCREEKTRIB.p01 (plan) ---

Plan Title=Multiple Run
Short Identifier=Multiple
Geom File=g01
Flow File=f01
Subcritical Flow
K Sum by GR= 0
Std Step Tol= 0.01
Critical Tol= 0.01
Num of Std Step Trials= 20
Max Error Tol= 0.3
Flow Tol Ratio= 0.001
Split Flow NTrial= 30
Split Flow Tol= 0.02
Split Flow Ratio= 0.02
Log Output Level= 0
Friction Slope Method= 1
Unsteady Friction Slope Method= 2
Unsteady Bridges Friction Slope Method= 1
Parabolic Critical Depth
Global Vel Dist=  1 , 1 , 1
Global Log Level= 0
CheckData=True
Encroach Param= -1, 0, 0, 0
BEGIN DESCRIPTION:
Multiple Run
END DESCRIPTION:

--- WICKSONCREEKTRIB.f01 (steady flow) ---

Flow Title=Multiple
Program Version=4.10
Number of Profiles= 7
Profile Names=10-year,25-year,50-year,1pct_min,100-year,1pct_plu,500-year
River Rch & RM=UNT1527 IN WICK,Reach-1         ,2202
     328     431     512     447     604     817     843
River Rch & RM=ICKSONCRTRIB4131,Reach-1         ,2202
     328     431     512     447     604     817     843
River Rch & RM=WICKSONCRTRB4131,Reach-1         ,2202
     328     431     512     447     604     817     843
Boundary for River Rch & Prof#=WICKSONCRTRB4131,Reach-1         , 1
Up Type= 0
Dn Type= 3
Dn Slope=0.005
Boundary for River Rch & Prof#=WICKSONCRTRB4131,Reach-1         , 2
Up Type= 0
Dn Type= 3
Dn Slope=0.005
Boundary for River Rch & Prof#=WICKSONCRTRB4131,Reach-1         , 3
Up Type= 0
Dn Type= 3
Dn Slope=0.005
Boundary for River Rch & Prof#=WICKSONCRTRB4131,Reach-1         , 4
Up Type= 0
Dn Type= 3
Dn Slope=0.005
Boundary for River Rch & Prof#=WICKSONCRTRB4131,Reach-1         , 5
Up Type= 0
Dn Type= 3
Dn Slope=0.005
Boundary for River Rch & Prof#=WICKSONCRTRB4131,Reach-1         , 6
Up Type= 0
Dn Type= 3
Dn Slope=0.005
Boundary for River Rch & Prof#=WICKSONCRTRB4131,Reach-1         , 7
Up Type= 0
Dn Type= 3
Dn Slope=0.005
DSS Import GetInterval= 0
DSS Import GetPeak= 0
DSS Import FillOption= 0

--- WICKSONCREEKTRIB.g01 (geometry) ---

Geom Title=Existing Conditions
Program Version=4.10

River Reach=WICKSONCRTRB4131,Reach-1
Reach XY= 30
       3533278.9     10273240.44      3533290.38     10273195.63
      3533373.25     10273107.78      3533383.34     10273061.87
      3533453.19     10273036.49      3533461.18     10272969.82
      3533579.43     10272847.36       3533758.4     10272820.17
      3533787.56     10272883.71       3533882.7     10272880.93
      3533883.48     10272741.65      3533918.16     10272662.54
      3533951.15     10272662.74      3534013.31     10272738.43
      3534123.26     10272761.79      3534193.37     10272726.38
      3534196.59     10272673.17      3534236.15     10272619.54
      3534389.61     10272519.15      3534416.04     10272522.95
      3534457.01      10272579.2      3534468.07     10272634.75
       3534493.4      10272658.3      3534516.23     10272653.49
      3534584.79     10272562.53      3534596.33     10272629.45
      3534623.09     10272649.46      3534650.06      10272653.5
      3534668.47     10272609.06      3534692.11     10272601.64

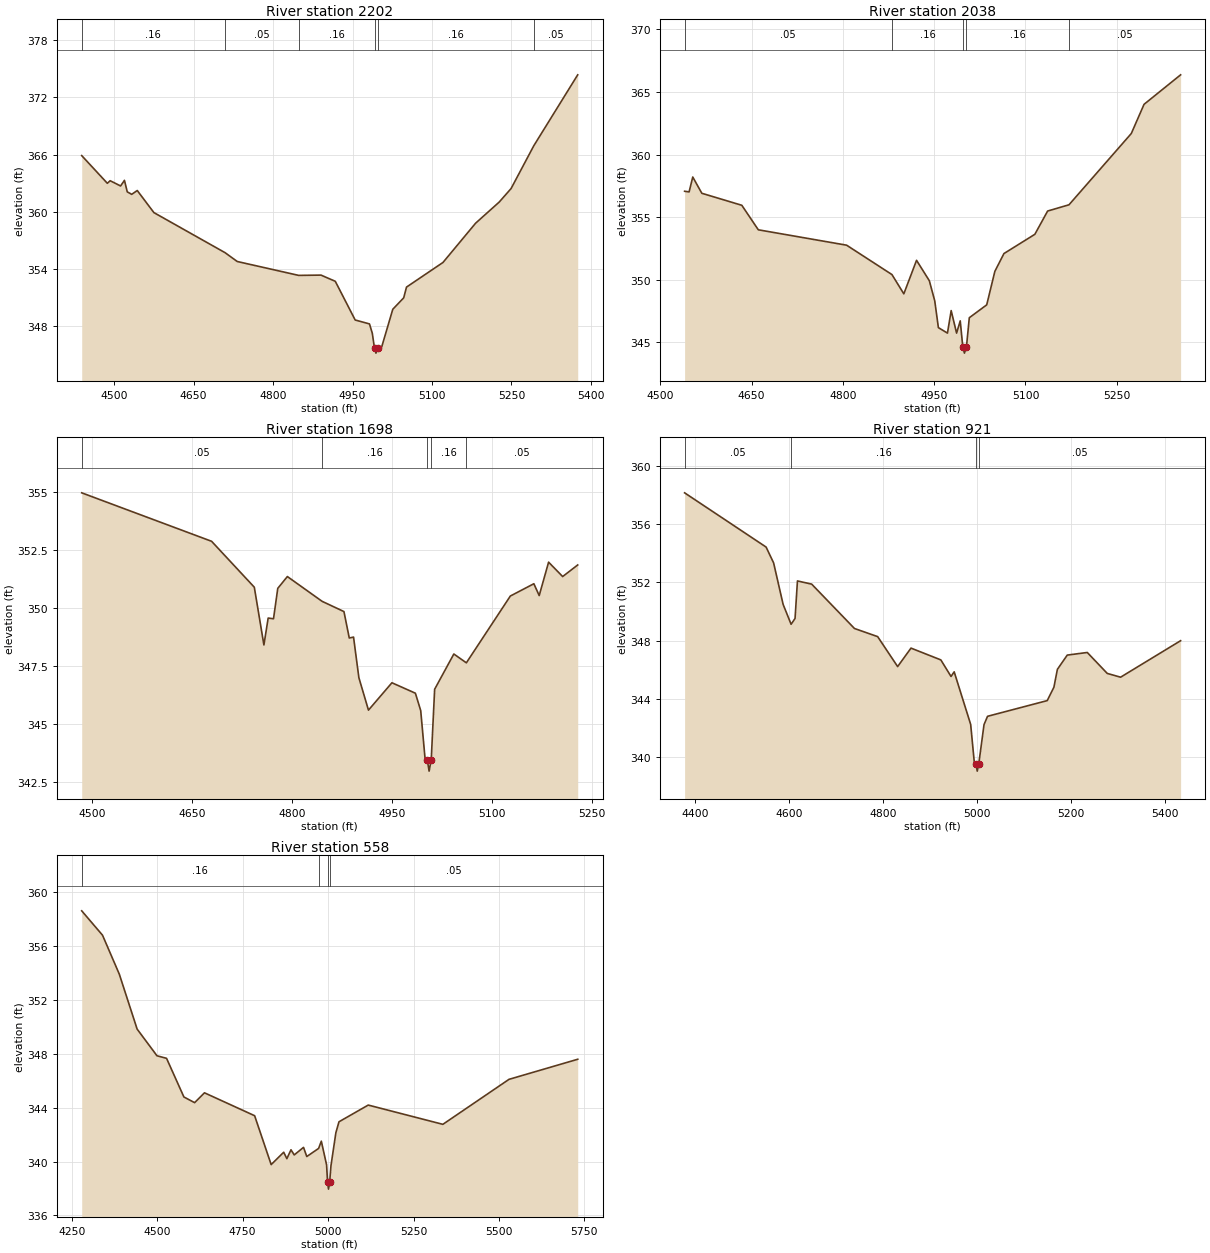
Type RM Length L Ch R = 1 ,2202    ,164,164,164
BEGIN DESCRIPTION:
UNT1527 IN WICK 2.0
END DESCRIPTION:
XS GIS Cut Line= 3
      3533492.09     10273691.61      3533294.66     10273067.92
      3533042.07     10272941.62
#Sta/Elev= 30
  4438.6  365.89    4487  362.98  4492.3  363.25    4512   362.7  4519.3  363.29
  4524.6  362.08    4533  361.82  4543.5  362.22  4574.9   359.9  4709.2  355.69
  4732.3  354.76  4848.3   353.3  4890.4  353.33  4917.4  352.68    4955  348.61
    4982   348.2  4987.3  347.22  4991.5  345.63  4994.2  345.13  4997.5  345.63
    5005  345.77    5026  349.74  5046.6  350.94  5051.9  352.07  5120.8  354.66
  5182.3  358.78    5227  361.01  5249.4  362.43  5292.3  366.93  5375.2  374.38
#Mann= 6 ,-1 , 0
  4438.6     .16       0  4709.2     .05       0  4848.3     .16       0
  4991.5     .07       0  4997.5     .16       0  5292.3     .05       0
Bank Sta=4991.5,4997.5
XS Rating Curve= 0 ,0
Exp/Cntr=0.3,0.1

Type RM Length L Ch R = 1 ,2038    ,340,340,340
BEGIN DESCRIPTION:
Mapping XS c313293d
END DESCRIPTION:
XS GIS Cut Line= 2
      3533682.14     10273421.41      3533222.08     10272748.68
#Sta/Elev= 30
  4539.9  357.06  4547.3  357.01  4553.3   358.2  4568.2   356.9  4633.9  355.94
    4661  353.98  4806.1  352.75  4880.6   350.4  4900.1  348.86    4921  351.54
    4942  349.91  4950.9   348.3  4956.9  346.16  4971.8  345.72  4977.9  347.52
  4986.8  345.72  4992.8   346.7    4997  344.62  4999.7  344.12    5003  344.62
  5007.7  346.95  5036.3  347.98  5049.7  350.66  5064.6  352.08  5115.4  353.62
  5136.4  355.48  5171.5  355.98  5273.9  361.68  5294.8  364.01  5354.9  366.37
#Mann= 5 ,-1 , 0
  4539.9     .05       0  4880.6     .16       0    4997     .07       0
    5003     .16       0  5171.5     .05       0
Bank Sta=4997,5003
XS Rating Curve= 0 ,0
Exp/Cntr=0.3,0.1

Type RM Length L Ch R = 1 ,1698    ,777,777,777
BEGIN DESCRIPTION:
Mapping XS 86e919ba
END DESCRIPTION:
XS GIS Cut Line= 2
      3533968.61     10273239.13      3533504.17     10272657.51
#Sta/Elev= 30
  4484.4  354.96  4679.3  352.87  4743.4  350.89  4757.8   348.4  4764.2  349.56
  4772.2  349.53  4778.6  350.84    4793  351.35  4845.2  350.28  4877.9  349.84
  4885.9   348.7  4892.3  348.74  4900.3  346.99  4914.7  345.59  4949.9  346.77
  4985.1  346.32  4993.1  345.57  4999.5  343.54  5002.9  343.46  5005.7  342.96
  5008.9  343.46    5014  346.49  5042.8  348.01  5061.6  347.63  5127.6  350.51
  5162.9  351.04  5170.9  350.53    5185  351.97  5206.1  351.35  5228.7  351.85
#Mann= 5 ,-1 , 0
  4484.4     .05       0  4845.2     .16       0  5002.9     .07       0
  5008.9     .16       0  5061.6     .05       0
Bank Sta=5002.9,5008.9
XS Rating Curve= 0 ,0
Exp/Cntr=0.3,0.1

Type RM Length L Ch R = 1 ,921     ,363,363,363
BEGIN DESCRIPTION:
UNT1527 IN WICK 1.0
END DESCRIPTION:
XS GIS Cut Line= 3
       3534259.4     10273308.56      3534315.82     10272961.35
      3533842.72      10272440.5
#Sta/Elev= 30
  4377.1  358.16  4550.5  354.43  4566.5  353.34  4586.7  350.49  4603.7  349.12
  4612.1  349.52  4617.2   352.1  4647.5  351.88  4738.5  348.83  4787.9  348.27
  4830.4  346.21  4858.8  347.48  4922.3  346.67    4944  345.53  4950.7  345.85
  4985.8  342.23  4993.3  339.69    4997  339.52  4999.8  339.02    5003  339.52
  5014.2  342.22  5021.7  342.79  5148.7  343.87  5162.9  344.79  5170.3  346.02
  5191.3     347  5233.9  347.18  5276.4  345.74  5304.8  345.48  5432.5  347.99
#Mann= 4 ,-1 , 0
  4377.1     .05       0  4603.7     .16       0    4997     .03       0
    5003     .05       0
Bank Sta=4997,5003
XS Rating Curve= 0 ,0
Exp/Cntr=0.3,0.1

Type RM Length L Ch R = 1 ,558     ,0,0,0
BEGIN DESCRIPTION:
UNT0492 IN WICK 1.0
END DESCRIPTION:
XS GIS Cut Line= 4
      3534441.72      10273143.6      3534597.94     10272887.56
      3534202.98      10272245.2       3533816.9     10272340.64
#Sta/Elev= 30
  4278.9  358.61  4339.8   356.8  4388.9  353.91  4441.1  349.83  4499.2  347.85
  4527.2  347.66    4578  344.79  4609.3  344.37  4638.2   345.1    4785   343.4
  4833.4  339.77  4870.1  340.69  4879.3  340.21  4891.4  340.87  4900.9  340.49
  4928.1  341.05  4937.6  340.37  4972.2  340.97  4980.2  341.51  4995.6  339.75
  4998.5  338.45  5001.2  337.95  5004.5  338.45  5008.4  339.69  5022.8  342.14
  5031.9  342.95  5117.5  344.19  5335.9  342.76  5529.5   346.1  5730.6  347.59
#Mann= 4 ,-1 , 0
  4278.9     .16       0  4972.2     .05       0  4998.5     .03       0
  5004.5     .05       0
Bank Sta=4998.5,5004.5
XS Rating Curve= 0 ,0
Exp/Cntr=0.3,0.1

Chan Stop Cuts=-1
Use User Specified Reach Order=0
Composite Channel Slope=5