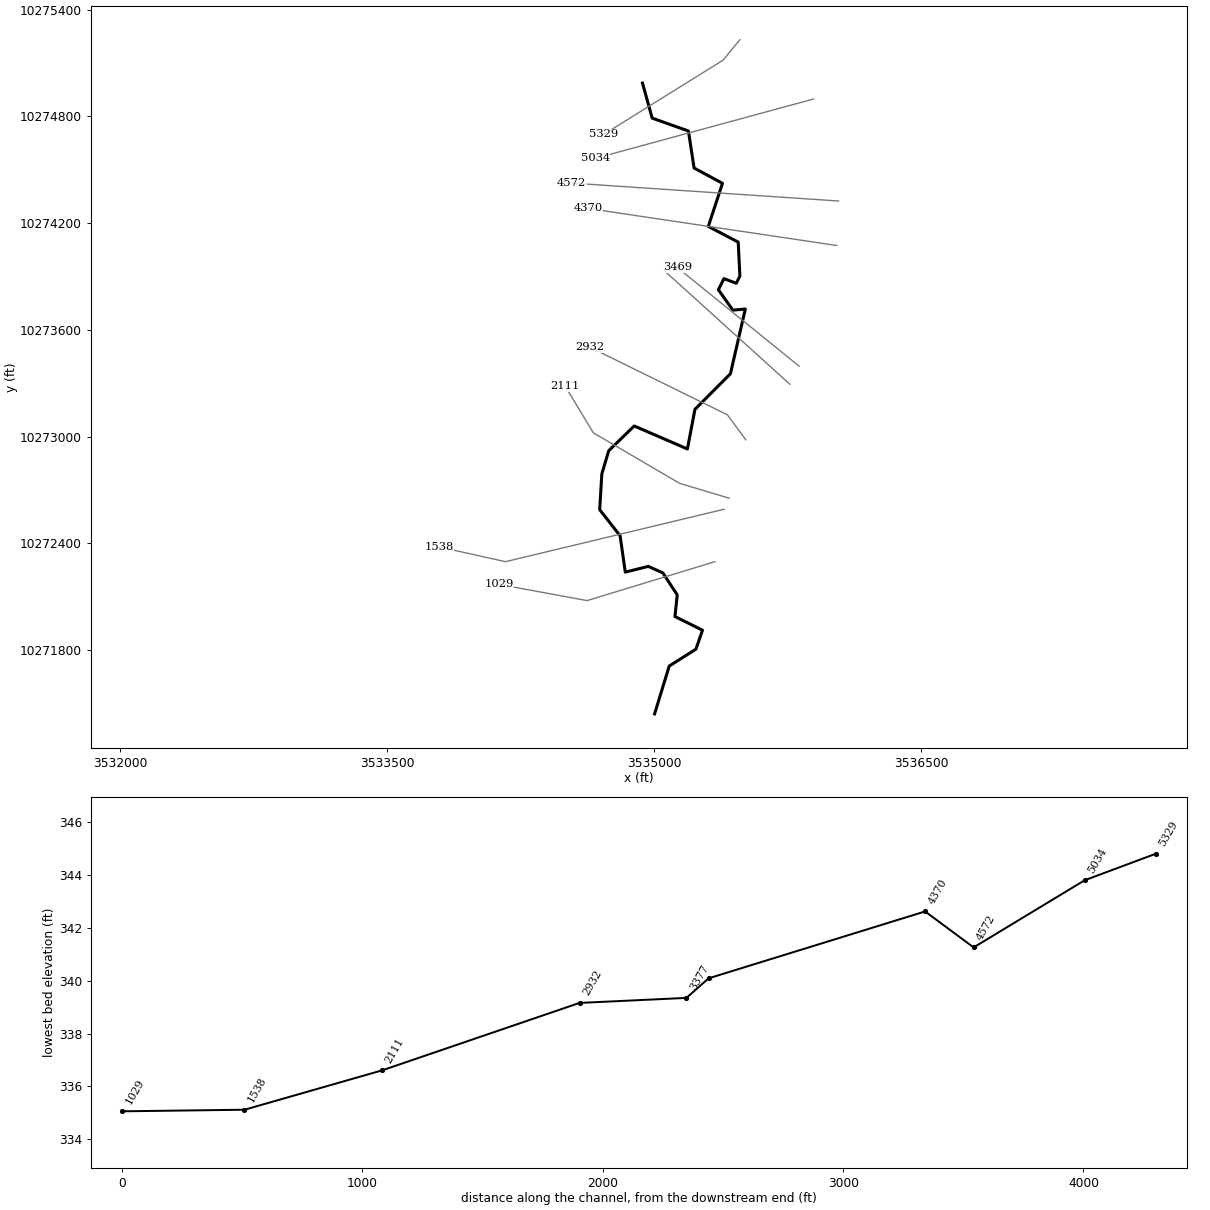
--- WICKSON CREEK TRIB 41 3.prj (project) ---

Proj Title=WICKSON CREEK TRIB 41 3 Base Level Engineering
Current Plan=p01
Default Exp/Contr=0.3,0.1
English Units
Geom File=g01
Flow File=f01
Plan File=p01
BEGIN DESCRIPTION:
WICKSON CREEK TRIB 41 3
END DESCRIPTION:

--- WICKSON CREEK TRIB 41 3.p01 (plan) ---

Plan Title=Multiple Run
Short Identifier=Multiple
Geom File=g01
Flow File=f01
Subcritical Flow
K Sum by GR= 0
Std Step Tol= 0.01
Critical Tol= 0.01
Num of Std Step Trials= 20
Max Error Tol= 0.3
Flow Tol Ratio= 0.001
Split Flow NTrial= 30
Split Flow Tol= 0.02
Split Flow Ratio= 0.02
Log Output Level= 0
Friction Slope Method= 1
Unsteady Friction Slope Method= 2
Unsteady Bridges Friction Slope Method= 1
Parabolic Critical Depth
Global Vel Dist=  1 , 1 , 1
Global Log Level= 0
CheckData=True
Encroach Param= -1, 0, 0, 0
BEGIN DESCRIPTION:
Multiple Run
END DESCRIPTION:

--- WICKSON CREEK TRIB 41 3.f01 (steady flow) ---

Flow Title=Multiple
Number of Profiles=7
Profile Names=10-year,25-year,50-year,1pct_min,100-year,1pct_plu,500-year
River Rch & RM= WICKSON CREEK TR,Reach-1,5329
     594     803     972     863    1167    1578    1685
River Rch & RM= WICKSON CREEK TR,Reach-1,1538
     749    1025    1251    1118    1511    2044    2214
Boundary for River Rch & Prof#=WICKSON CREEK TR,Reach-1,1
Up Type=0
Dn Type=3
Dn Slope=0.005
Boundary for River Rch & Prof#=WICKSON CREEK TR,Reach-1,2
Up Type=0
Dn Type=3
Dn Slope=0.005
Boundary for River Rch & Prof#=WICKSON CREEK TR,Reach-1,3
Up Type=0
Dn Type=3
Dn Slope=0.005
Boundary for River Rch & Prof#=WICKSON CREEK TR,Reach-1,4
Up Type=0
Dn Type=3
Dn Slope=0.005
Boundary for River Rch & Prof#=WICKSON CREEK TR,Reach-1,5
Up Type=0
Dn Type=3
Dn Slope=0.005
Boundary for River Rch & Prof#=WICKSON CREEK TR,Reach-1,6
Up Type=0
Dn Type=3
Dn Slope=0.005
Boundary for River Rch & Prof#=WICKSON CREEK TR,Reach-1,7
Up Type=0
Dn Type=3
Dn Slope=0.005

--- WICKSON CREEK TRIB 41 3.g01 (geometry) ---

Geom Title=Existing Conditions

River Reach=WICKSON CREEK TR,Reach-1
Reach XY= 30
      3534934.20     10274986.82      3534988.68     10274790.02
      3535192.32     10274717.63      3535224.22     10274509.63
      3535383.60     10274423.69      3535304.17     10274181.25
      3535472.14     10274093.22      3535481.52     10273902.34
      3535461.02     10273861.87      3535392.02     10273888.02
      3535360.77     10273825.52      3535442.02     10273710.93
      3535512.16     10273717.18      3535428.34     10273353.29
      3535229.01     10273153.27      3535186.56     10272930.76
      3534887.67     10273059.84      3534744.46     10272920.78
      3534705.62     10272790.53      3534693.66     10272589.48
      3534808.40     10272442.74      3534837.52     10272238.45
      3534967.00     10272270.79      3535048.55     10272234.18
      3535129.64     10272110.41      3535116.49     10271989.04
      3535271.39     10271912.11      3535234.58     10271805.48
      3535084.57     10271710.73      3535002.11     10271441.64

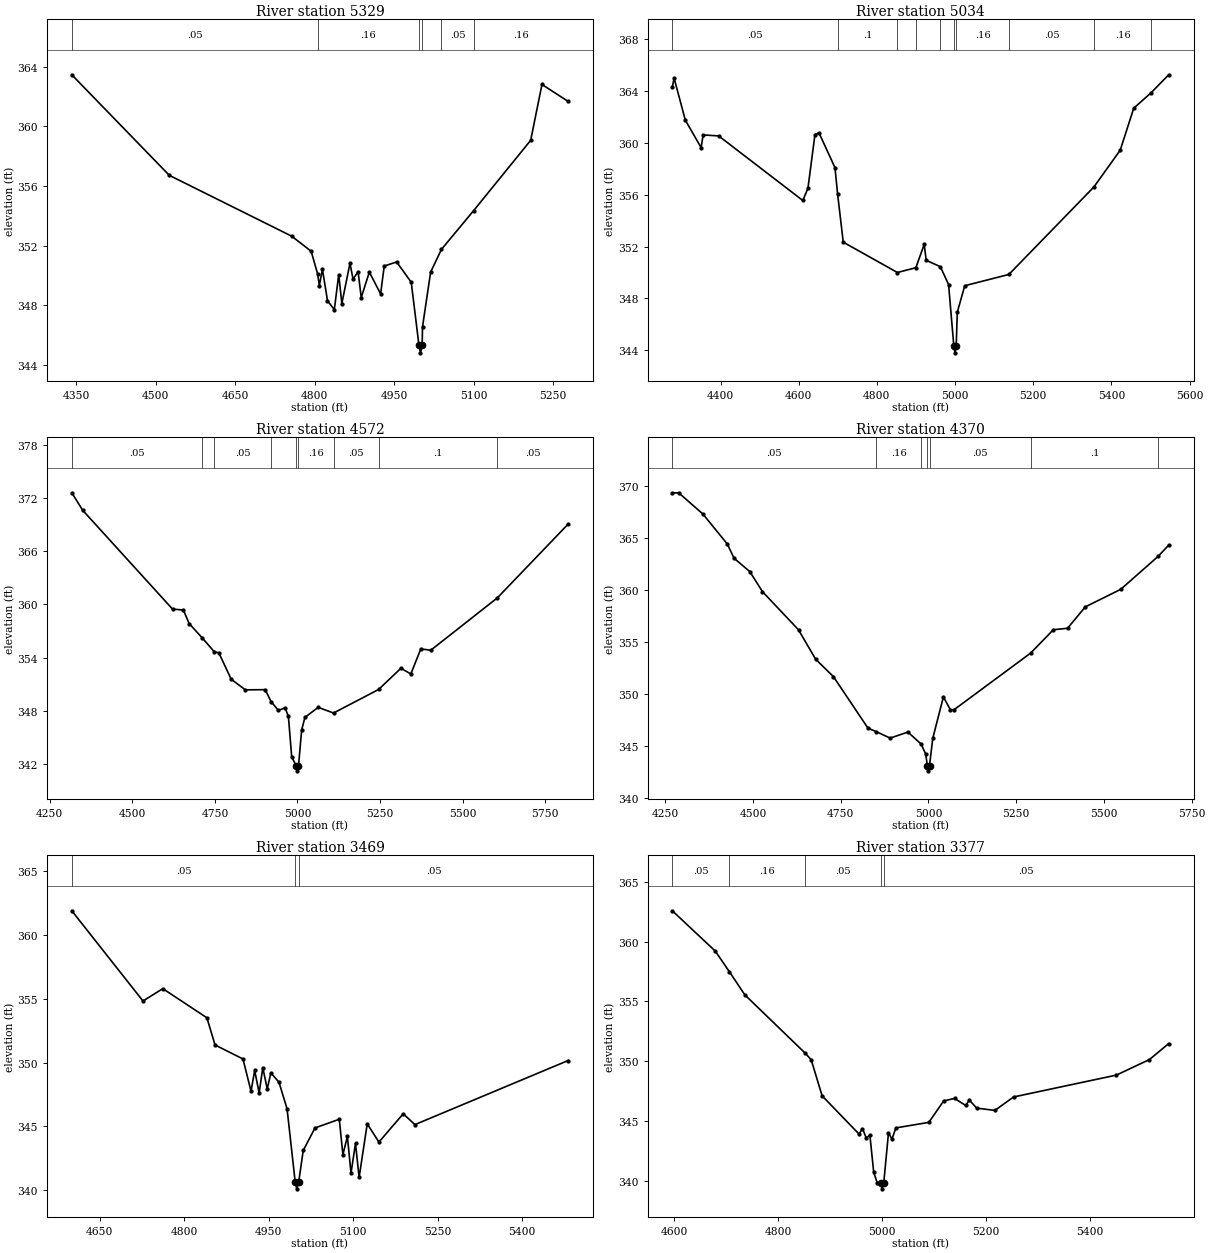
Type RM Length L Ch R = 1,5329,295,295,295
BEGIN DESCRIPTION:
UNT0491 IN WICK 31.0
END DESCRIPTION:
XS GIS Cut Line= 3
      3535480.98     10275230.41      3535387.23     10275115.83
      3534717.14     10274699.20
#Sta/Elev= 30
  4341.6  363.47  4525.6  356.72  4756.9  352.63  4793.5  351.62  4805.8  350.08
  4808.9  349.32  4814.8  350.40  4824.3  348.30  4837.2  347.70  4845.5  350.05
  4851.4  348.11  4866.7  350.81  4872.6  349.75  4882.1  350.25  4888.0  348.51
  4903.3  350.22  4924.6  348.76  4931.4  350.63  4954.9  350.90  4982.4  349.54
  4997.0  345.30  4999.8  344.80  5003.0  345.30  5003.7  346.55  5019.0  350.22
  5039.5  351.75  5100.0  354.34  5207.9  359.07  5229.2  362.82  5278.7  361.68
#Mann=6,-1,0
  4341.6    0.05       0  4805.8    0.16       0  4997.0    0.07       0
  5003.0    0.16       0  5039.5    0.05       0  5100.0    0.16       0
Bank Sta=4997,5003
Exp/Cntr=0.3,0.1

Type RM Length L Ch R = 1,5034,462,462,462
BEGIN DESCRIPTION:
Mapping XS 032c935d
END DESCRIPTION:
XS GIS Cut Line= 2
      3535894.19     10274897.09      3534668.51     10274563.76
#Sta/Elev= 30
  4276.6  364.29  4281.1  365.01  4309.9  361.75  4350.3  359.64  4355.5  360.62
  4395.3  360.54  4610.4  355.56  4623.6  356.49  4641.5  360.63  4651.8  360.79
  4692.8  358.09  4699.4  356.09  4714.0  352.34  4852.6  350.00  4899.8  350.37
  4921.1  352.17  4926.3  350.94  4962.5  350.45  4983.5  349.07  4997.0  344.30
  4999.8  343.80  5003.0  344.30  5005.8  346.93  5024.9  348.98  5137.8  349.85
  5355.3  356.60  5422.7  359.44  5457.3  362.68  5502.0  363.88  5546.8  365.26
#Mann=10,-1,0
  4276.6    0.05       0  4699.4     0.1       0  4852.6    0.05       0
  4899.8     0.1       0  4962.5    0.16       0  4997.0    0.07       0
  5003.0    0.16       0  5137.8    0.05       0  5355.3    0.16       0
  5502.0    0.05       0
Bank Sta=4997,5003
Exp/Cntr=0.3,0.1

Type RM Length L Ch R = 1,4572,202,202,202
BEGIN DESCRIPTION:
UNT0491 IN WICK 30.0
END DESCRIPTION:
XS GIS Cut Line= 2
      3536036.50     10274324.17      3534536.78     10274424.84
#Sta/Elev= 30
  4316.6  372.57  4349.8  370.59  4621.7  359.47  4654.5  359.37  4671.8  357.85
  4712.2  356.20  4747.6  354.69  4762.0  354.54  4799.3  351.57  4842.2  350.38
  4902.3  350.40  4919.9  349.06  4942.4  348.06  4962.4  348.36  4972.5  347.38
  4982.5  342.83  4997.0  341.76  4999.8  341.26  5003.0  341.76  5012.6  345.87
  5022.6  347.28  5062.7  348.41  5109.1  347.77  5245.6  350.42  5313.2  352.81
  5343.3  352.17  5373.4  354.99  5403.6  354.84  5605.3  360.74  5819.7  369.05
#Mann=9,-1,0
  4316.6    0.05       0  4712.2    0.16       0  4747.6    0.05       0
  4919.9    0.16       0  4997.0    0.07       0  5003.0    0.16       0
  5109.1    0.05       0  5245.6     0.1       0  5605.3    0.05       0
Bank Sta=4997,5003
Exp/Cntr=0.3,0.1

Type RM Length L Ch R = 1,4370,901,901,901
BEGIN DESCRIPTION:
Mapping XS 20d310a5
END DESCRIPTION:
XS GIS Cut Line= 2
      3536026.08     10274074.17      3534627.00     10274282.47
#Sta/Elev= 30
  4270.1  369.36  4288.1  369.38  4357.4  367.33  4426.8  364.45  4446.0  363.08
  4491.0  361.79  4526.9  359.87  4629.7  356.19  4678.5  353.36  4729.1  351.69
  4827.6  346.73  4850.6  346.40  4890.8  345.77  4941.4  346.35  4979.0  345.20
  4991.9  344.25  4997.0  343.12  4999.8  342.62  5003.0  343.12  5012.2  345.74
  5042.5  349.73  5062.7  348.49  5072.8  348.50  5291.1  353.95  5355.9  356.20
  5396.4  356.34  5446.9  358.40  5548.0  360.09  5654.1  363.25  5684.6  364.34
#Mann=7,-1,0
  4270.1    0.05       0  4850.6    0.16       0  4979.0    0.05       0
  4997.0    0.03       0  5003.0    0.05       0  5291.1     0.1       0
  5654.1    0.05       0
Bank Sta=4997,5003
Exp/Cntr=0.3,0.1

Type RM Length L Ch R = 1,3469,92,92,92
BEGIN DESCRIPTION:
UNT0491 IN WICK 29.0
END DESCRIPTION:
XS GIS Cut Line= 2
      3535814.28     10273396.24      3535129.41     10273950.90
#Sta/Elev= 30
  4600.3  361.91  4726.7  354.83  4761.9  355.80  4840.2  353.51  4854.6  351.38
  4904.2  350.28  4918.5  347.75  4925.0  349.38  4932.9  347.61  4939.4  349.60
  4947.3  347.93  4953.7  349.19  4968.1  348.46  4982.5  346.37  4997.0  340.59
  4999.8  340.09  5003.0  340.59  5011.2  343.10  5032.1  344.87  5075.2  345.55
  5081.6  342.77  5089.6  344.20  5096.0  341.32  5104.0  343.66  5110.4  340.98
  5124.8  345.19  5145.6  343.76  5188.7  345.98  5209.5  345.13  5481.6  350.16
#Mann=3,-1,0
  4600.3    0.05       0  4997.0    0.04       0  5003.0    0.05       0
Bank Sta=4997,5003
Exp/Cntr=0.3,0.1

Type RM Length L Ch R = 1,3377,445,445,445
BEGIN DESCRIPTION:
UNT0491 IN WICK 28.0
END DESCRIPTION:
XS GIS Cut Line= 2
      3535762.24     10273294.64      3535053.88     10273935.29
#Sta/Elev= 30
  4596.2  362.57  4678.9  359.20  4706.2  357.47  4735.7  355.55  4852.1  350.67
  4863.4  350.13  4884.4  347.12  4955.3  343.93  4962.1  344.37  4969.5  343.58
  4976.3  343.85  4983.7  340.72  4990.5  339.85  4997.0  339.85  4999.8  339.35
  5003.0  339.85  5012.1  344.01  5018.9  343.51  5026.3  344.44  5089.8  344.90
  5118.2  346.69  5139.2  346.90  5160.8  346.31  5167.6  346.77  5181.8  346.09
  5216.9  345.90  5252.7  347.02  5450.8  348.85  5514.3  350.15  5551.3  351.48
#Mann=5,-1,0
  4596.2    0.05       0  4706.2    0.16       0  4852.1    0.05       0
  4997.0    0.03       0  5003.0    0.05       0
Bank Sta=4997,5003
Exp/Cntr=0.3,0.1

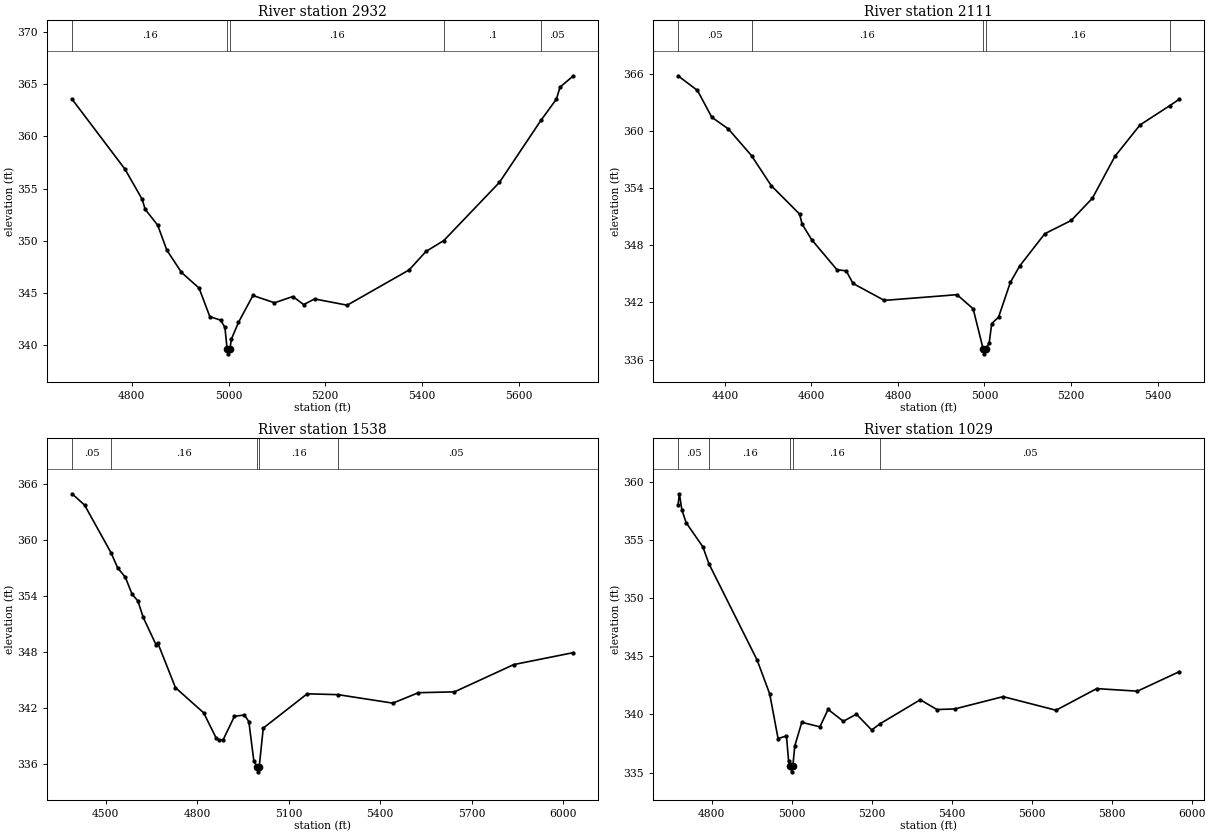
Type RM Length L Ch R = 1,2932,821,821,821
BEGIN DESCRIPTION:
UNT0491 IN WICK 27.0
END DESCRIPTION:
XS GIS Cut Line= 3
      3535514.82     10272982.16      3535410.82     10273122.93
      3534637.25     10273502.97
#Sta/Elev= 30
  4676.4  363.56  4785.9  356.85  4821.4  353.97  4827.6  353.01  4853.5  351.49
  4872.3  349.11  4902.7  346.96  4939.1  345.46  4961.4  342.72  4983.7  342.39
  4992.6  341.69  4997.0  339.66  4999.8  339.16  5003.0  339.66  5006.0  340.58
  5020.6  342.17  5050.5  344.75  5095.1  344.05  5133.0  344.65  5155.5  343.88
  5178.0  344.42  5245.4  343.82  5373.6  347.20  5408.4  348.97  5445.2  350.01
  5560.2  355.58  5646.0  361.52  5678.2  363.57  5685.6  364.71  5713.3  365.80
#Mann=5,-1,0
  4676.4    0.16       0  4997.0    0.07       0  5003.0    0.16       0
  5445.2     0.1       0  5646.0    0.05       0
Bank Sta=4997,5003
Exp/Cntr=0.3,0.1

Type RM Length L Ch R = 1,2111,573,573,573
BEGIN DESCRIPTION:
UNT0491 IN WICK 25.0
END DESCRIPTION:
XS GIS Cut Line= 4
      3535421.10     10272654.02      3535143.59     10272737.23
      3534658.06     10273021.21      3534499.55     10273283.67
#Sta/Elev= 30
  4291.7  365.80  4336.6  364.26  4369.7  361.45  4408.0  360.22  4461.5  357.42
  4507.2  354.26  4572.5  351.29  4578.6  350.22  4600.3  348.61  4659.0  345.44
  4680.4  345.32  4696.1  344.00  4768.5  342.22  4936.6  342.82  4973.8  341.34
  4997.0  337.11  4999.8  336.61  5003.0  337.11  5011.0  337.80  5016.8  339.79
  5032.5  340.46  5059.8  344.11  5081.3  345.83  5139.4  349.22  5200.4  350.61
  5249.5  352.95  5301.3  357.33  5359.5  360.64  5428.5  362.67  5450.5  363.35
#Mann=5,-1,0
  4291.7    0.05       0  4461.5    0.16       0  4997.0    0.07       0
  5003.0    0.16       0  5428.5    0.05       0
Bank Sta=4997,5003
Exp/Cntr=0.3,0.1

Type RM Length L Ch R = 1,1538,509,509,509
BEGIN DESCRIPTION:
UNT0491 IN WICK 24.0
END DESCRIPTION:
XS GIS Cut Line= 3
      3535392.10     10272591.64      3534164.31     10272297.26
      3533791.17     10272380.05
#Sta/Elev= 30
  4389.1  364.95  4430.2  363.74  4517.7  358.58  4538.7  357.00  4563.9  356.00
  4585.9  354.18  4605.0  353.46  4622.7  351.68  4664.7  348.75  4669.9  348.98
  4728.4  344.15  4821.0  341.45  4862.1  338.73  4872.4  338.52  4885.1  338.58
  4921.9  341.08  4954.7  341.22  4969.1  340.51  4985.5  336.29  4997.0  335.62
  4999.8  335.12  5003.0  335.62  5016.4  339.81  5160.4  343.49  5262.1  343.40
  5441.5  342.49  5525.5  343.61  5643.7  343.70  5838.5  346.63  6033.9  347.91
#Mann=5,-1,0
  4389.1    0.05       0  4517.7    0.16       0  4997.0    0.07       0
  5003.0    0.16       0  5262.1    0.05       0
Bank Sta=4997,5003
Exp/Cntr=0.3,0.1

Type RM Length L Ch R = 1,1029,0,0,0
BEGIN DESCRIPTION:
UNT0491 IN WICK 22.0
END DESCRIPTION:
XS GIS Cut Line= 3
      3535341.38     10272297.25      3534622.64     10272078.51
      3534128.80     10272169.28
#Sta/Elev= 30
  4716.0  358.01  4719.3  358.98  4725.7  357.59  4736.1  356.50  4778.0  354.42
  4793.2  352.96  4913.8  344.67  4945.2  341.76  4966.1  337.92  4987.0  338.15
  4992.5  335.97  4997.0  335.56  4999.8  335.06  5003.0  335.56  5007.9  337.30
  5025.4  339.32  5070.6  338.93  5091.1  340.43  5129.2  339.41  5162.0  340.02
  5200.1  338.66  5221.3  339.20  5321.5  341.26  5363.3  340.42  5407.7  340.47
  5528.8  341.53  5661.0  340.36  5762.7  342.22  5864.4  342.00  5969.4  343.68
#Mann=5,-1,0
  4716.0    0.05       0  4793.2    0.16       0  4997.0    0.07       0
  5003.0    0.16       0  5221.3    0.05       0
Bank Sta=4997,5003
Exp/Cntr=0.3,0.1

Chan Stop Cuts=-1