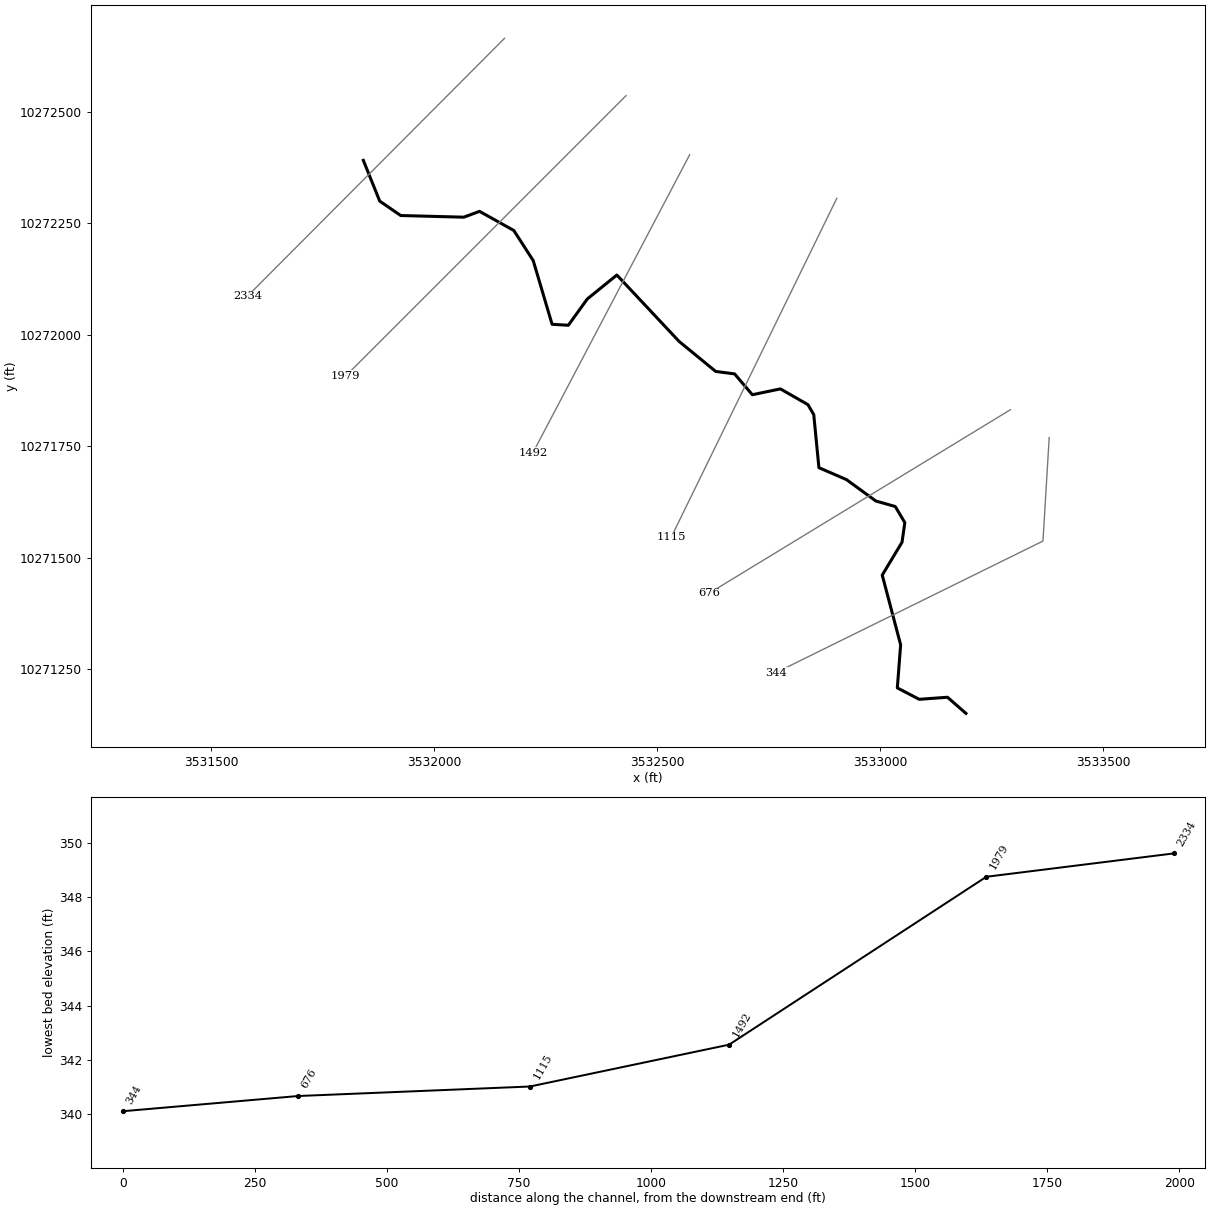
--- WICKSONCREEKTRIB.prj (project) ---

Proj Title=WICKSON CREEK TRIB 41 4
Current Plan=p01
Default Exp/Contr=0.3,0.1
English Units
Geom File=g01
Flow File=f01
Plan File=p01
Y Axis Title=Elevation
X Axis Title(PF)=Main Channel Distance
X Axis Title(XS)=Station
BEGIN DESCRIPTION:
UNT1529 IN WICK
END DESCRIPTION:
DSS Export Rating Curves= 0
DSS Export Rating Curve Sorted= 0
DSS Export Volume Flow Curves= 0
DXF OffsetX= 0
DXF OffsetY= 0
DXF ScaleX= 1
DXF ScaleY= 10

--- WICKSONCREEKTRIB.p01 (plan) ---

Plan Title=Multiple Run
Short Identifier=Multiple
Geom File=g01
Flow File=f01
Subcritical Flow
K Sum by GR= 0
Std Step Tol= 0.01
Critical Tol= 0.01
Num of Std Step Trials= 20
Max Error Tol= 0.3
Flow Tol Ratio= 0.001
Split Flow NTrial= 30
Split Flow Tol= 0.02
Split Flow Ratio= 0.02
Log Output Level= 0
Friction Slope Method= 1
Unsteady Friction Slope Method= 2
Unsteady Bridges Friction Slope Method= 1
Parabolic Critical Depth
Global Vel Dist=  1 , 1 , 1
Global Log Level= 0
CheckData=True
Encroach Param= -1, 0, 0, 0
BEGIN DESCRIPTION:
Multiple Run
END DESCRIPTION:

--- WICKSONCREEKTRIB.f01 (steady flow) ---

Flow Title=Multiple
Program Version=4.10
Number of Profiles= 7
Profile Names=10-year,25-year,50-year,1pct_min,100-year,1pct_plu,500-year
River Rch & RM=UNT1529 IN WICK,Reach-1         ,2334
     339     445     530     463     627     847     877
River Rch & RM=WICKSONCRTRB414,Reach-1         ,2334
     339     445     530     463     627     847     877
Boundary for River Rch & Prof#=WICKSONCRTRB414,Reach-1         , 1
Up Type= 0
Dn Type= 3
Dn Slope=0.005
Boundary for River Rch & Prof#=WICKSONCRTRB414,Reach-1         , 2
Up Type= 0
Dn Type= 3
Dn Slope=0.005
Boundary for River Rch & Prof#=WICKSONCRTRB414,Reach-1         , 3
Up Type= 0
Dn Type= 3
Dn Slope=0.005
Boundary for River Rch & Prof#=WICKSONCRTRB414,Reach-1         , 4
Up Type= 0
Dn Type= 3
Dn Slope=0.005
Boundary for River Rch & Prof#=WICKSONCRTRB414,Reach-1         , 5
Up Type= 0
Dn Type= 3
Dn Slope=0.005
Boundary for River Rch & Prof#=WICKSONCRTRB414,Reach-1         , 6
Up Type= 0
Dn Type= 3
Dn Slope=0.005
Boundary for River Rch & Prof#=WICKSONCRTRB414,Reach-1         , 7
Up Type= 0
Dn Type= 3
Dn Slope=0.005
DSS Import GetInterval= 0
DSS Import GetPeak= 0
DSS Import FillOption= 0

--- WICKSONCREEKTRIB.g01 (geometry) ---

Geom Title=Existing Conditions
Program Version=4.10

River Reach=WICKSONCRTRB414 ,Reach-1
Reach XY= 30
       3531841.2      10272391.4      3531877.96     10272300.03
      3531925.07     10272267.71      3532066.48     10272263.99
       3532101.7     10272277.05      3532178.58      10272234.2
      3532222.07     10272166.72      3532264.37     10272023.86
      3532300.83     10272021.69      3532343.19     10272080.51
      3532409.56     10272134.36      3532549.18     10271985.43
      3532631.21     10271918.15      3532673.53     10271912.67
      3532713.33     10271865.94       3532776.2      10271879.1
      3532838.07     10271843.64      3532850.96     10271821.36
      3532862.55     10271702.42      3532924.23     10271675.74
      3532990.13     10271627.77      3533033.78     10271615.33
      3533055.15     10271579.26      3533048.87     10271535.35
       3533004.5     10271461.62      3533045.75     10271305.38
      3533038.33     10271208.74      3533087.44     10271183.16
      3533150.79     10271187.78      3533192.11     10271151.64

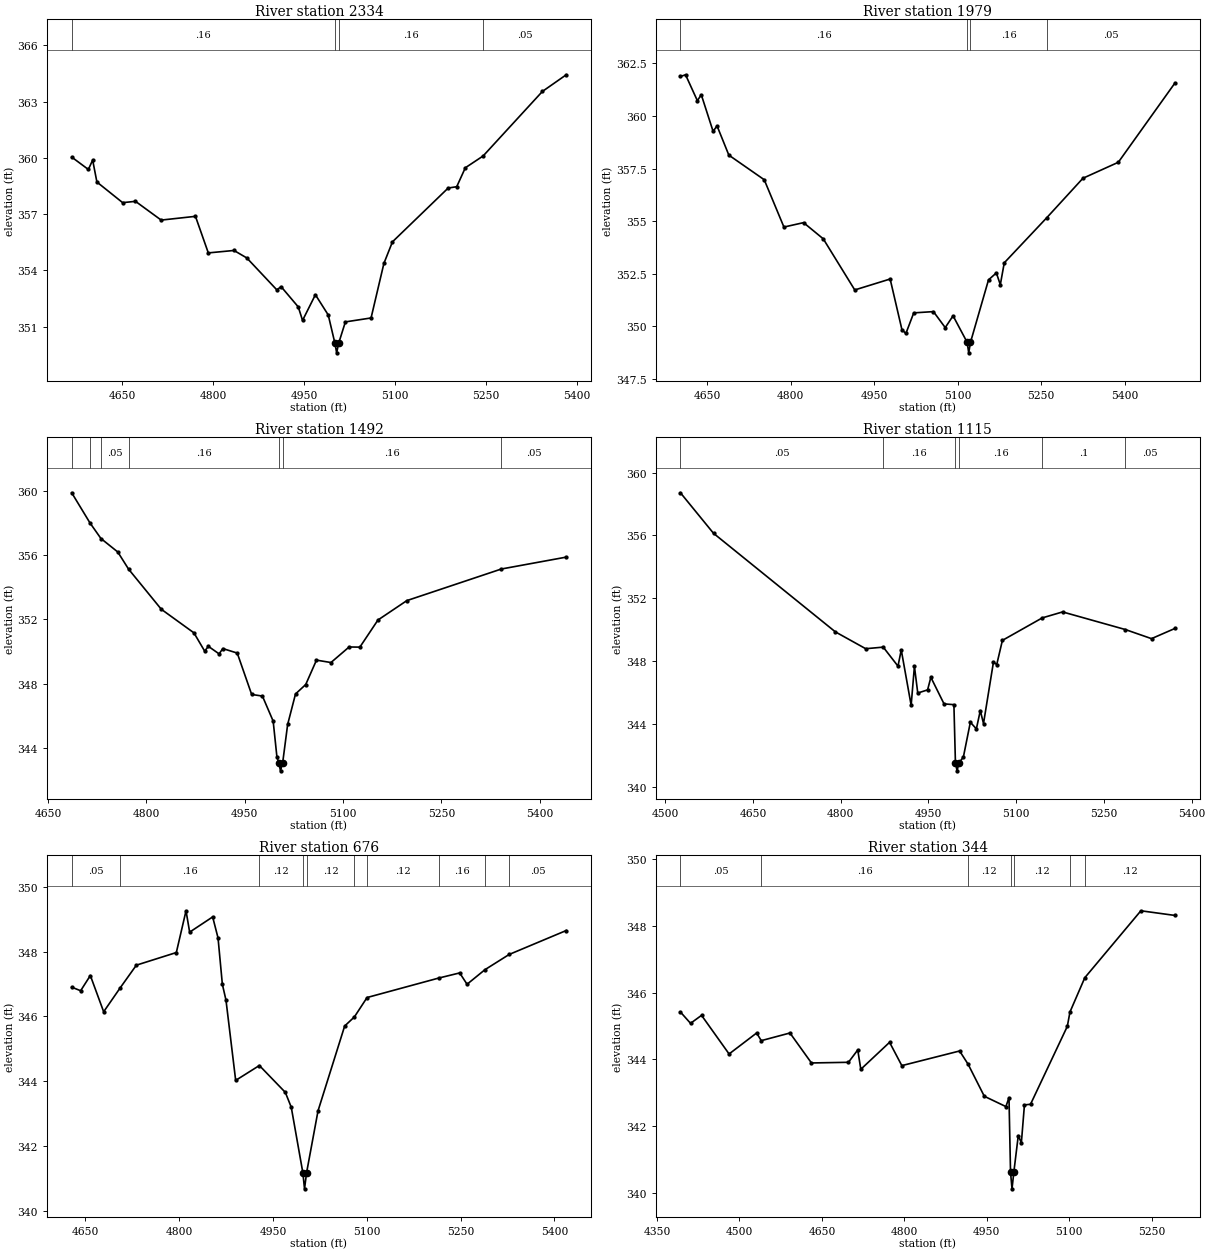
Type RM Length L Ch R = 1 ,2334    ,355,355,355
BEGIN DESCRIPTION:
UNT1529 IN WICK 4.0
END DESCRIPTION:
XS GIS Cut Line= 2
      3532157.71     10272664.93       3531581.3     10272086.78
#Sta/Elev= 30
  4566.6  360.04  4594.1  359.38  4601.2  359.88  4608.2  358.71  4650.7  357.61
  4671.9  357.68  4714.3  356.68  4770.9  356.88  4792.1  354.93  4834.5  355.06
  4855.7  354.66  4905.2  352.96  4912.3  353.13  4940.6  352.05  4947.7  351.33
  4968.9   352.7  4990.1  351.62  5001.2   350.1    5004   349.6  5007.2   350.1
  5018.4  351.25  5060.8  351.46    5082  354.37  5096.1  355.52  5188.1  358.39
  5202.2  358.46  5216.4  359.47  5245.8   360.1  5343.6  363.54    5383  364.43
#Mann= 4 ,-1 , 0
  4566.6     .16       0  5001.2     .07       0  5007.2     .16       0
  5245.8     .05       0
Bank Sta=5001.2,5007.2
XS Rating Curve= 0 ,0
Exp/Cntr=0.3,0.1

Type RM Length L Ch R = 1 ,1979    ,487,487,487
BEGIN DESCRIPTION:
Mapping XS b66ffc76
END DESCRIPTION:
XS GIS Cut Line= 2
      3532430.31     10272536.48      3531801.83       10271908.
#Sta/Elev= 30
  4601.7  361.88  4610.9  361.96  4632.1  360.73  4639.2  361.01  4660.4  359.27
  4667.5  359.53  4688.7  358.14  4752.3  356.97  4787.7  354.72    4823  354.93
  4858.4  354.16    4915  351.73  4978.6  352.25  4999.8  349.84  5006.9  349.66
    5021  350.64  5056.4   350.7  5077.6  349.94  5091.7   350.5    5117  349.24
  5119.8  348.74    5123  349.24  5155.4  352.21  5169.5  352.54  5176.6  351.98
  5183.7  353.02  5260.3  355.17  5325.1  357.04  5388.7   357.8  5490.5  361.57
#Mann= 4 ,-1 , 0
  4601.7     .16       0    5117     .07       0    5123     .16       0
  5260.3     .05       0
Bank Sta=5117,5123
XS Rating Curve= 0 ,0
Exp/Cntr=0.3,0.1

Type RM Length L Ch R = 1 ,1492    ,377,377,377
BEGIN DESCRIPTION:
UNT1529 IN WICK 3.0
END DESCRIPTION:
XS GIS Cut Line= 2
      3532572.75     10272403.88      3532221.48     10271736.03
#Sta/Elev= 30
    4686  359.89  4713.9  358.01  4730.6  357.04  4756.3   356.2  4772.8  355.13
  4822.7  352.63  4872.5  351.16  4888.9  350.02  4894.5  350.32  4910.9  349.85
  4916.6  350.18  4938.6   349.9  4960.6  347.32    4977  347.22  4993.4  345.66
  4999.1  343.44  5001.9  343.06  5004.6  342.56  5007.9  343.06  5015.5  345.45
  5027.5  347.35  5043.1  347.94  5059.5  349.46  5081.6  349.31  5109.3  350.28
  5125.7  350.27  5153.3  351.96  5197.4  353.17  5341.7  355.14  5440.6  355.88
#Mann= 7 ,-1 , 0
    4686     .05       0  4713.9     .16       0  4730.6     .05       0
  4772.8     .16       0  5001.9     .07       0  5007.9     .16       0
  5341.7     .05       0
Bank Sta=5001.9,5007.9
XS Rating Curve= 0 ,0
Exp/Cntr=0.3,0.1

Type RM Length L Ch R = 1 ,1115    ,439,439,439
BEGIN DESCRIPTION:
UNT1529 IN WICK 2.0
END DESCRIPTION:
XS GIS Cut Line= 2
       3532902.6      10272306.2      3532531.48     10271546.61
#Sta/Elev= 30
    4526  358.71  4582.6  356.13  4790.9  349.86  4842.7  348.79  4872.7  348.89
  4897.9  347.68  4903.5  348.71  4920.4  345.19    4926  347.67  4931.7  345.97
  4948.5  346.17  4954.1  346.97  4976.6  345.28  4993.5  345.23  4996.1  341.52
  4998.9  341.02  5002.1  341.52  5009.7   341.9  5021.6  344.11  5031.9  343.69
  5038.6  344.85  5044.1  344.03  5061.1  347.94  5066.7  347.78  5076.4  349.32
  5144.5  350.75  5179.3  351.13  5286.5  350.01  5331.3  349.43  5371.4  350.08
#Mann= 6 ,-1 , 0
    4526     .05       0  4872.7     .16       0  4996.1     .07       0
  5002.1     .16       0  5144.5      .1       0  5286.5     .05       0
Bank Sta=4996.1,5002.1
XS Rating Curve= 0 ,0
Exp/Cntr=0.3,0.1

Type RM Length L Ch R = 1 ,676     ,332,332,332
BEGIN DESCRIPTION:
Mapping XS 40ab9434
END DESCRIPTION:
XS GIS Cut Line= 2
      3533291.99     10271832.47      3532616.62     10271421.07
#Sta/Elev= 30
  4628.1   346.9  4642.4  346.79  4657.9  347.26  4679.2  346.14  4705.3  346.87
  4731.5  347.58  4795.4  347.97  4810.9  349.26  4816.7   348.6  4853.5  349.07
  4862.1  348.42    4869  346.99  4874.8   346.5  4890.3  344.02  4928.2  344.48
  4969.7  343.65  4979.2  343.19  4997.7  341.17  5000.4  340.67  5003.7  341.17
    5022  343.08  5064.6   345.7  5080.1  345.98  5100.4  346.58  5214.7  347.18
  5248.5  347.34  5260.3  346.99  5288.9  347.44  5327.6  347.91  5418.9  348.65
#Mann= 10 ,-1 , 0
  4628.1     .05       0  4705.3     .16       0  4928.2     .12       0
  4997.7     .07       0  5003.7     .12       0  5080.1     .16       0
  5100.4     .12       0  5214.7     .16       0  5288.9      .1       0
  5327.6     .05       0
Bank Sta=4997.7,5003.7
XS Rating Curve= 0 ,0
Exp/Cntr=0.3,0.1

Type RM Length L Ch R = 1 ,344     ,0,0,0
BEGIN DESCRIPTION:
UNT1529 IN WICK 1.0
END DESCRIPTION:
XS GIS Cut Line= 3
      3533378.79       10271770.      3533364.83     10271537.97
      3532766.48     10271243.13
#Sta/Elev= 30
  4392.7  345.42  4411.1  345.08  4431.1  345.32  4481.2  344.16  4531.3  344.79
  4539.7  344.56  4591.9  344.79    4631  343.89  4698.3  343.91  4715.2  344.28
  4720.8   343.7  4773.1  344.51  4795.4  343.81  4900.5  344.25    4916  343.85
  4945.4  342.89  4984.7  342.58  4990.3  342.85  4993.1  340.61  4995.8  340.11
  4999.1  340.61  5007.2  341.71  5012.8  341.49  5018.4  342.63  5029.5  342.65
  5096.4  344.99  5101.2  345.42  5128.2  346.45  5230.2  348.46  5292.2  348.32
#Mann= 7 ,-1 , 0
  4392.7     .05       0  4539.7     .16       0    4916     .12       0
  4993.1     .07       0  4999.1     .12       0  5101.2     .16       0
  5128.2     .12       0
Bank Sta=4993.1,4999.1
XS Rating Curve= 0 ,0
Exp/Cntr=0.3,0.1

Chan Stop Cuts=-1
Use User Specified Reach Order=0
Composite Channel Slope=5