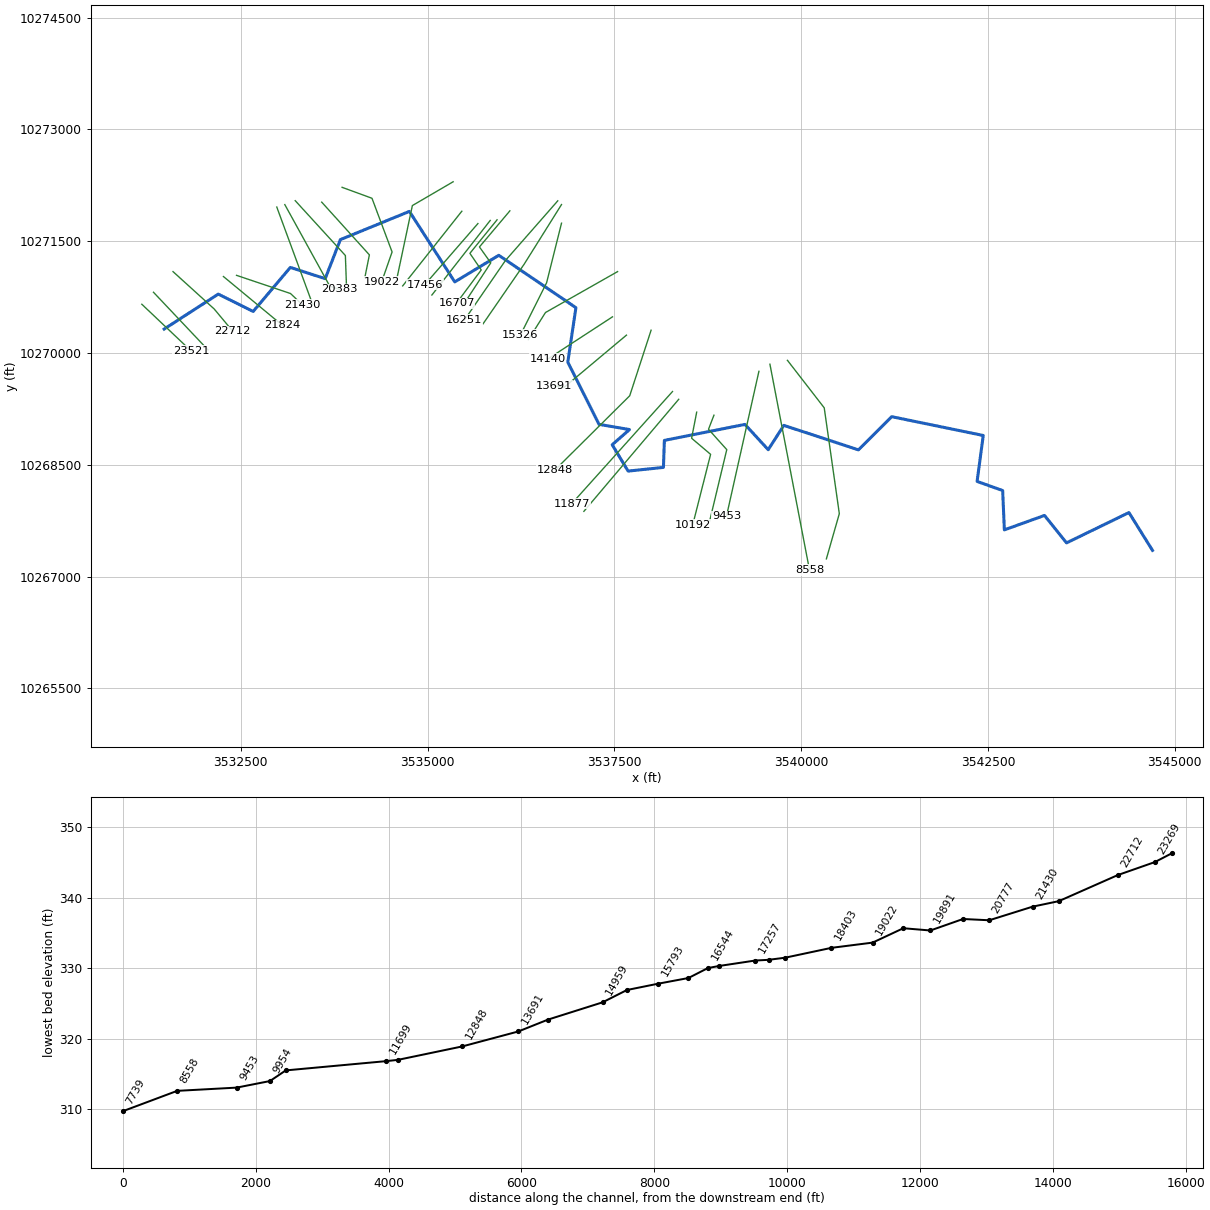
--- WICKSONCREEKTRIB.prj (project) ---

Proj Title=WICKSON CREEK TRIB 41
Current Plan=p01
Default Exp/Contr=0.3,0.1
English Units
Geom File=g01
Flow File=f01
Plan File=p01
Y Axis Title=Elevation
X Axis Title(PF)=Main Channel Distance
X Axis Title(XS)=Station
BEGIN DESCRIPTION:
UNT0491 IN WICK
END DESCRIPTION:
DSS Export Rating Curves= 0
DSS Export Rating Curve Sorted= 0
DSS Export Volume Flow Curves= 0
DXF Filename=UNT0491 IN WICK.
DXF OffsetX= 0
DXF OffsetY= 0
DXF ScaleX= 1
DXF ScaleY= 10

--- WICKSONCREEKTRIB.p01 (plan) ---

Plan Title=Multiple Run
Short Identifier=Multiple
Geom File=g01
Flow File=f01
Subcritical Flow
K Sum by GR= 0
Std Step Tol= 0.01
Critical Tol= 0.01
Num of Std Step Trials= 20
Max Error Tol= 0.3
Flow Tol Ratio= 0.001
Split Flow NTrial= 30
Split Flow Tol= 0.02
Split Flow Ratio= 0.02
Log Output Level= 0
Friction Slope Method= 1
Unsteady Friction Slope Method= 2
Unsteady Bridges Friction Slope Method= 1
Parabolic Critical Depth
Global Vel Dist=  1 , 1 , 1
Global Log Level= 0
CheckData=True
Encroach Param= -1, 0, 0, 0
BEGIN DESCRIPTION:
Multiple Run
END DESCRIPTION:

--- WICKSONCREEKTRIB.f01 (steady flow) ---

Flow Title=Multiple
Program Version=4.10
Number of Profiles= 7
Profile Names=10-year,25-year,50-year,1pct_min,100-year,1pct_plu,500-year
River Rch & RM=WICKSONCRTRB41,Reach-1         ,23521
     436     579     694     610     825    1116    1168
River Rch & RM=WICKSONCRTRB41,Reach-1         ,20777
     716     983    1204    1080    1461    1975    2157
River Rch & RM=WICKSONCRTRB41,Reach-1         ,18403
    1197    1671    2070    1873    2533    3425    3806
River Rch & RM=WICKSONCRTRB41,Reach-1         ,17705
    1197    1671    2070    1873    2533    3425    3806
River Rch & RM=WICKSONCRTRB41,Reach-1         ,12848
    1492    2100    2614    2376    3213    4345    4871
River Rch & RM=WICKSONCRTRB41,Reach-1         ,6530
    1672    2358    2940    2673    3615    4889    5489
Boundary for River Rch & Prof#=WICKSONCRTRB41,Reach-1         , 1
Up Type= 0
Dn Type= 3
Dn Slope=0.005
Boundary for River Rch & Prof#=WICKSONCRTRB41,Reach-1         , 2
Up Type= 0
Dn Type= 3
Dn Slope=0.005
Boundary for River Rch & Prof#=WICKSONCRTRB41,Reach-1         , 3
Up Type= 0
Dn Type= 3
Dn Slope=0.005
Boundary for River Rch & Prof#=WICKSONCRTRB41,Reach-1         , 4
Up Type= 0
Dn Type= 3
Dn Slope=0.005
Boundary for River Rch & Prof#=WICKSONCRTRB41,Reach-1         , 5
Up Type= 0
Dn Type= 3
Dn Slope=0.005
Boundary for River Rch & Prof#=WICKSONCRTRB41,Reach-1         , 6
Up Type= 0
Dn Type= 3
Dn Slope=0.005
Boundary for River Rch & Prof#=WICKSONCRTRB41,Reach-1         , 7
Up Type= 0
Dn Type= 3
Dn Slope=0.005
DSS Import GetInterval= 0
DSS Import GetPeak= 0
DSS Import FillOption= 0

--- WICKSONCREEKTRIB.g01 (geometry) ---

Geom Title=Existing Conditions
Program Version=4.10

River Reach=WICKSONCRTRB41  ,Reach-1
Reach XY= 30
      3531472.98     10270320.43      3532197.66     10270789.78
      3532664.95     10270557.13      3533161.84     10271147.93
      3533629.04      10270997.3      3533831.84     10271520.88
      3534756.18     10271899.64      3535363.03     10270953.63
      3535952.45     10271310.67      3536984.61     10270607.82
      3536876.03      10269877.5      3537293.66     10269042.67
      3537701.99     10268972.53      3537470.04     10268769.06
      3537683.24     10268415.58      3538155.93     10268465.01
       3538168.9     10268827.58       3539247.5     10269041.77
      3539558.42     10268702.27      3539767.44       10269029.
      3540766.06      10268700.3      3541211.89     10269145.44
      3542436.78     10268893.27      3542354.06      10268277.2
      3542696.51     10268154.34      3542719.14     10267626.66
      3543256.12     10267820.44      3543551.41     10267452.27
      3544386.53     10267859.06      3544702.11     10267351.64

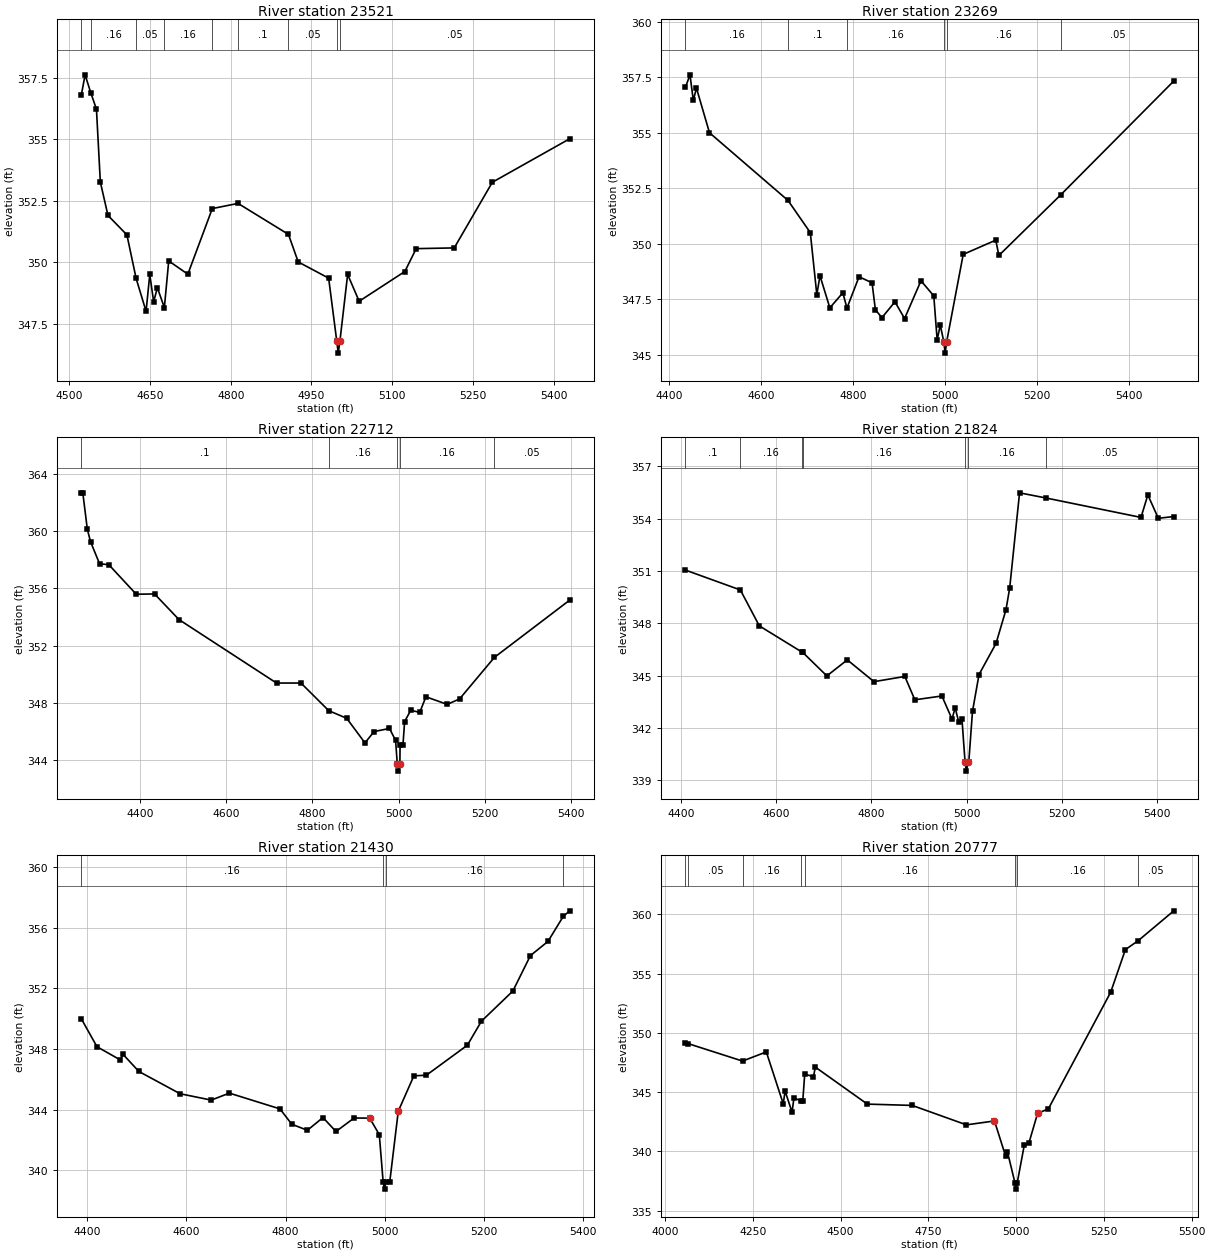
Type RM Length L Ch R = 1 ,23521   ,252,252,252
BEGIN DESCRIPTION:
UNT0492 IN WICK 10.0
END DESCRIPTION:
XS GIS Cut Line= 2
      3531174.57      10270653.9      3531832.46     10270028.66
#Sta/Elev= 30
  4522.4   356.8  4529.4  357.62  4539.8   356.9  4550.5  356.22  4557.7  353.26
  4571.9   351.9  4607.1  351.11  4624.2  349.34  4642.7     348  4649.6   349.5
  4656.8  348.39  4663.7  348.96  4676.7  348.15  4684.8  350.05  4720.3  349.51
  4765.8  352.18  4813.6  352.39  4907.3  351.13  4925.4  350.01    4982  349.35
    4997   346.8  4999.8   346.3    5003   346.8  5017.3   349.5  5038.7  348.41
  5123.6  349.62  5144.7  350.55  5215.4  350.58  5286.2  353.25    5430  355.02
#Mann= 9 ,-1 , 0
  4522.4     .05       0  4539.8     .16       0  4624.2     .05       0
  4676.7     .16       0  4765.8     .05       0  4813.6      .1       0
  4907.3     .05       0    4997     .04       0    5003     .05       0
Bank Sta=4997,5003
XS Rating Curve= 0 ,0
Exp/Cntr=0.3,0.1

Type RM Length L Ch R = 1 ,23269   ,557,557,557
BEGIN DESCRIPTION:
Mapping XS 62747ee4
END DESCRIPTION:
XS GIS Cut Line= 2
      3531330.84     10270814.48      3532059.98     10270041.93
#Sta/Elev= 30
  4434.8  357.04  4444.8  357.61    4452  356.46  4458.9  357.01  4487.2     355
    4658  351.95  4706.5   350.5  4720.7   347.7  4727.5  348.56    4749  347.11
  4777.3  347.79  4786.2   347.1  4812.5  348.51  4840.8  348.24  4848.1  347.02
  4862.3  346.67  4890.6  347.38  4911.6  346.63  4947.2  348.33  4975.1  347.65
  4982.4  345.67  4989.3  346.33    4997  345.57  4999.8  345.07    5003  345.57
  5039.1  349.52  5109.9  350.16  5116.7  349.47  5251.6  352.21  5497.1  357.33
#Mann= 6 ,-1 , 0
  4434.8     .16       0    4658      .1       0  4786.2     .16       0
    4997     .07       0    5003     .16       0  5251.6     .05       0
Bank Sta=4997,5003
XS Rating Curve= 0 ,0
Exp/Cntr=0.3,0.1

Type RM Length L Ch R = 1 ,22712   ,888,888,888
BEGIN DESCRIPTION:
UNT0492 IN WICK 9.0
END DESCRIPTION:
XS GIS Cut Line= 3
      3531592.09     10271091.66      3532142.11     10270591.64
      3532392.08     10270291.68
#Sta/Elev= 30
  4263.5  362.66  4266.9  362.66  4277.4  360.12  4284.8  359.25  4305.8  357.71
  4327.4  357.64  4390.9  355.58  4433.5   355.6  4490.2  353.81  4716.6  349.38
  4773.4  349.38  4837.9  347.45  4879.5  346.92    4922   345.2    4943  345.99
  4978.8  346.21    4993  345.38    4997  343.73  4999.8  343.23    5003  343.73
  5003.5  345.03  5010.1  345.03    5014  346.69  5028.3  347.48  5049.1  347.33
  5063.5  348.42  5112.9  347.89  5141.6  348.27  5222.4  351.17  5397.3  355.17
#Mann= 5 ,-1 , 0
  4263.5      .1       0  4837.9     .16       0    4997     .07       0
    5003     .16       0  5222.4     .05       0
Bank Sta=4997,5003
XS Rating Curve= 0 ,0
Exp/Cntr=0.3,0.1

Type RM Length L Ch R = 1 ,21824   ,394,394,394
BEGIN DESCRIPTION:
UNT0492 IN WICK 8.0
END DESCRIPTION:
XS GIS Cut Line= 2
       3532267.2     10271025.59      3533057.13     10270370.22
#Sta/Elev= 30
  4409.2  351.06  4524.7  349.92  4564.6  347.86  4653.4  346.37  4655.8  346.34
  4706.5  344.99  4749.5  345.91  4805.5  344.66  4870.4  344.96  4891.4  343.62
  4948.3  343.84  4969.6  342.51  4976.1  343.17  4983.9  342.32  4990.4  342.54
    4997  340.03  4999.8  339.53    5003  340.03  5004.7  340.03  5012.6  342.96
  5026.3  345.07    5062  346.85  5082.9  348.78  5090.7  350.02  5111.5  355.49
  5167.7  355.19  5366.7  354.08  5381.1  355.37  5403.1  354.03  5435.6  354.13
#Mann= 7 ,-1 , 0
  4409.2      .1       0  4524.7     .16       0  4653.4      .1       0
  4655.8     .16       0    4997     .07       0    5003     .16       0
  5167.7     .05       0
Bank Sta=4997,5003
XS Rating Curve= 0 ,0
Exp/Cntr=0.3,0.1

Type RM Length L Ch R = 1 ,21430   ,653,653,653
BEGIN DESCRIPTION:
UNT0492 IN WICK 7.0
END DESCRIPTION:
XS GIS Cut Line= 3
      3532442.13     10271041.63      3533164.67     10270797.84
      3533326.24     10270643.64
#Sta/Elev= 30
  4387.8  349.98  4419.4  348.14  4466.4  347.27  4472.2  347.63  4503.9  346.51
  4587.1  345.04    4650  344.62  4686.7  345.08  4788.8  344.04  4812.6  343.03
  4844.1  342.63  4875.6  343.47  4901.8  342.55  4938.5  343.44    4970  343.43
  4989.3  342.34    4997  339.25  4999.8  338.75    5003  339.25  5010.5  339.25
  5027.6  343.89  5059.1  346.22  5084.3  346.26  5167.1  348.24  5195.4  349.82
  5258.9  351.81  5294.4  354.15  5329.7  355.08  5360.8  356.74  5373.7   357.1
#Mann= 4 ,-1 , 0
  4387.8     .16       0    4997     .07       0    5003     .16       0
  5360.8     .05       0
Bank Sta=4970,5027.6
XS Rating Curve= 0 ,0
Exp/Cntr=0.3,0.1

Type RM Length L Ch R = 1 ,20777   ,394,394,394
BEGIN DESCRIPTION:
UNT0492 IN WICK 6.0
END DESCRIPTION:
XS GIS Cut Line= 2
      3532980.87       10271958.      3533460.79      10270652.3
#Sta/Elev= 30
    4058  349.17    4066  349.09  4220.7  347.62  4288.5  348.39  4336.7  344.02
    4342  345.09  4361.8  343.31  4367.2  344.51  4387.7  344.26  4392.3  344.24
  4397.9  346.52  4422.8   346.3  4428.1  347.11  4576.2  343.99    4704  343.88
  4858.6  342.24  4938.4  342.57  4969.8  339.63  4975.2  339.98    4997  337.32
  4999.8  336.82    5003  337.32  5023.6  340.58  5036.1  340.67  5061.3  343.22
  5091.7  343.58  5269.3  353.42  5311.3  357.02  5348.1  357.78  5449.1  360.29
#Mann= 8 ,-1 , 0
    4058     .16       0    4066     .05       0  4220.7     .16       0
  4387.7     .12       0  4397.9     .16       0    4997     .07       0
    5003     .16       0  5348.1     .05       0
Bank Sta=4938.4,5061.3
XS Rating Curve= 0 ,0
Exp/Cntr=0.3,0.1

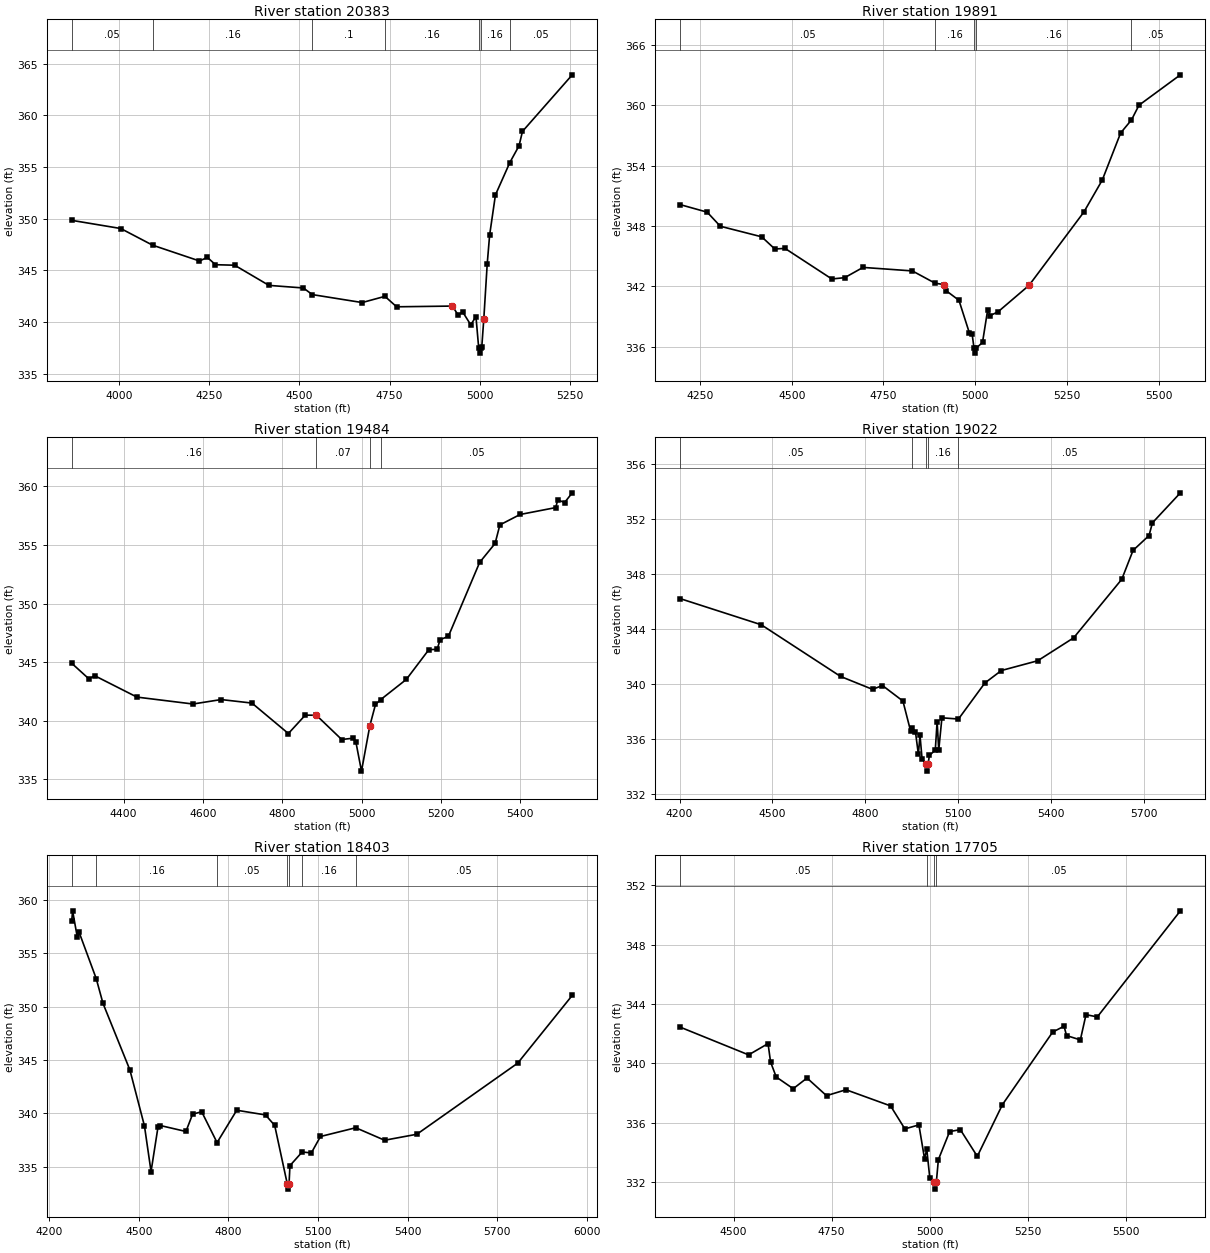
Type RM Length L Ch R = 1 ,20383   ,492,492,492
BEGIN DESCRIPTION:
UNT0492 IN WICK 5.0
END DESCRIPTION:
XS GIS Cut Line= 3
      3533088.48     10271990.72      3533690.82     10270895.37
      3533821.04     10270851.97
#Sta/Elev= 30
    3869  349.84  4004.9  349.05  4093.1  347.44  4223.2  345.91    4245  346.26
  4267.4  345.55  4320.7   345.5  4415.7  343.55  4511.1   343.3  4535.8  342.66
    4674  341.89  4737.1  342.49  4769.5  341.48  4924.1  341.55  4940.2  340.67
  4952.1  341.01  4974.9  339.74  4989.4  340.53    4997   337.5  4999.8     337
    5003   337.5  5005.5  337.58  5011.2  340.34  5020.6  345.63  5027.3  348.42
  5043.4   352.3  5083.3  355.43  5108.8  357.05  5118.3  358.44  5256.3  363.91
#Mann= 7 ,-1 , 0
    3869     .05       0  4093.1     .16       0  4535.8      .1       0
  4737.1     .16       0    4997     .07       0    5003     .16       0
  5083.3     .05       0
Bank Sta=4924.1,5011.2
XS Rating Curve= 0 ,0
Exp/Cntr=0.3,0.1

Type RM Length L Ch R = 1 ,19891   ,407,407,407
BEGIN DESCRIPTION:
UNT0492 IN WICK 4.0
END DESCRIPTION:
XS GIS Cut Line= 3
      3533228.17     10272043.18      3533899.16      10271307.7
      3533912.18      10270938.8
#Sta/Elev= 30
  4194.9  350.14  4269.5  349.38  4305.3  347.98  4418.1  346.93  4453.9  345.72
  4481.6  345.78  4609.3  342.74  4644.4  342.87  4694.4  343.89  4828.9  343.54
  4890.8  342.32    4914  342.19  4920.8  341.58  4955.9  340.62  4984.3  337.38
  4991.7  337.28    4997  335.87  4999.8  335.37    5003  335.87  5020.1  336.43
  5034.3  339.69    5041   339.1  5062.6  339.48  5147.1  342.11  5296.6   349.4
  5346.6  352.57  5396.7  357.25  5426.3  358.55  5446.7  360.01  5559.6  363.03
#Mann= 5 ,-1 , 0
  4194.9     .05       0  4890.8     .16       0    4997     .07       0
    5003     .16       0  5426.3     .05       0
Bank Sta=4914,5147.1
XS Rating Curve= 0 ,0
Exp/Cntr=0.3,0.1

Type RM Length L Ch R = 1 ,19484   ,462,462,462
BEGIN DESCRIPTION:
UNT0492 IN WICK 3.0
END DESCRIPTION:
XS GIS Cut Line= 3
      3533582.31     10272023.85      3534220.34     10271316.38
      3534159.57     10271012.57
#Sta/Elev= 30
  4268.9   344.9  4312.5  343.56  4326.7  343.84  4433.5  342.01  4574.8  341.42
  4645.8   341.8  4723.5   341.5  4815.4   338.9    4858  340.47 4886.01  340.46
  4949.9  338.39  4978.3   338.5  4985.6  338.19  4999.8  335.69  5020.9  339.57
  5035.1  341.38  5048.4   341.8  5112.9  343.52  5169.7  346.06  5190.6  346.09
  5198.1  346.91    5219   347.2  5297.8  353.51  5336.8  355.13  5348.8  356.71
  5399.8   357.6  5489.7  358.19  5494.8  358.85    5512  358.62  5531.4  359.45
#Mann= 4 ,-1 , 0
  4268.9     .16       0 4886.01     .07       0  5020.9     .16       0
  5048.4     .05       0
Bank Sta=4886.01,5020.9
XS Rating Curve= 0 ,0
Exp/Cntr=0.3,0.1

Type RM Length L Ch R = 1 ,19022   ,619,619,619
BEGIN DESCRIPTION:
UNT0492 IN WICK 2.0
END DESCRIPTION:
XS GIS Cut Line= 4
      3533855.02     10272222.56      3534255.06     10272075.93
      3534524.16     10271355.44      3534385.34     10270956.36
#Sta/Elev= 30
  4200.7  346.21  4463.9   344.3  4720.2  340.54  4823.5   339.6  4855.5  339.88
  4921.7  338.75  4946.6  336.56  4950.7  336.78  4962.3  336.49  4971.6  334.88
  4976.9  336.25  4983.6  334.54    4997  334.15  4999.8  333.65    5003  334.15
  5007.2  334.79  5026.3  335.18  5032.2  337.26  5037.5  335.18  5047.7  337.53
  5101.2  337.44  5186.4  340.06  5239.8  340.97  5357.2  341.68  5473.5  343.35
    5629  347.61  5665.4  349.71    5717  350.79  5728.1  351.72  5818.4   353.9
#Mann= 5 ,-1 , 0
  4200.7     .05       0  4950.7     .16       0    4997     .07       0
    5003     .16       0  5101.2     .05       0
Bank Sta=4997,5003
XS Rating Curve= 0 ,0
Exp/Cntr=0.3,0.1

Type RM Length L Ch R = 1 ,18403   ,698,698,698
BEGIN DESCRIPTION:
UNT0492 IN WICK 2.01
END DESCRIPTION:
XS GIS Cut Line= 3
      3535341.42     10272297.27      3534795.62     10271977.77
      3534579.47     10270956.95
#Sta/Elev= 30
  4275.3  358.01  4278.4  358.98  4294.1   356.5  4299.9  356.99  4357.3  352.64
  4380.1  350.31  4470.1  344.08  4518.9  338.83    4541  334.56  4564.2  338.72
  4571.7  338.87  4657.7  338.31  4680.1  339.93  4710.5  340.16    4762  337.27
  4827.9   340.3  4924.2  339.86  4954.9  338.88    4997  333.41  4999.8  332.91
    5003  333.41    5006  335.11  5046.9  336.39  5077.6   336.3  5108.2  337.84
  5226.3  338.66  5322.9  337.49  5430.9  338.05  5768.5  344.71  5951.2  351.06
#Mann= 7 ,-1 , 0
  4275.3     .05       0  4357.3     .16       0    4762     .05       0
    4997    .035       0    5003     .05       0  5046.9     .16       0
  5226.3     .05       0
Bank Sta=4997,5003
XS Rating Curve= 0 ,0
Exp/Cntr=0.3,0.1

Type RM Length L Ch R = 1 ,17705   ,249,249,249
BEGIN DESCRIPTION:
Mapping XS 6e37ed1e
END DESCRIPTION:
XS GIS Cut Line= 2
      3535457.59     10271902.13      3534666.02     10270900.06
#Sta/Elev= 30
  4362.6  342.44  4538.1  340.56  4587.7  341.32  4594.1  340.08  4608.5  339.07
  4651.9  338.28  4687.1     339  4736.8  337.81  4786.5  338.21  4900.3  337.12
  4936.7  335.57  4972.5  335.84  4986.9  333.56  4992.6   334.2  5000.4  332.24
  5011.1  332.01  5013.9  331.51  5017.1  332.01  5022.2   333.5    5051  335.39
  5078.2  335.52  5121.5  333.72  5185.7  337.21  5313.9   342.1  5342.8  342.49
  5349.2  341.86  5384.4  341.57  5398.8  343.27  5427.7  343.12  5639.6  350.27
#Mann= 4 ,-1 , 0
  4362.6     .05       0  4992.6     .16       0  5011.1     .07       0
  5017.1     .05       0
Bank Sta=5011.1,5017.1
XS Rating Curve= 0 ,0
Exp/Cntr=0.3,0.1

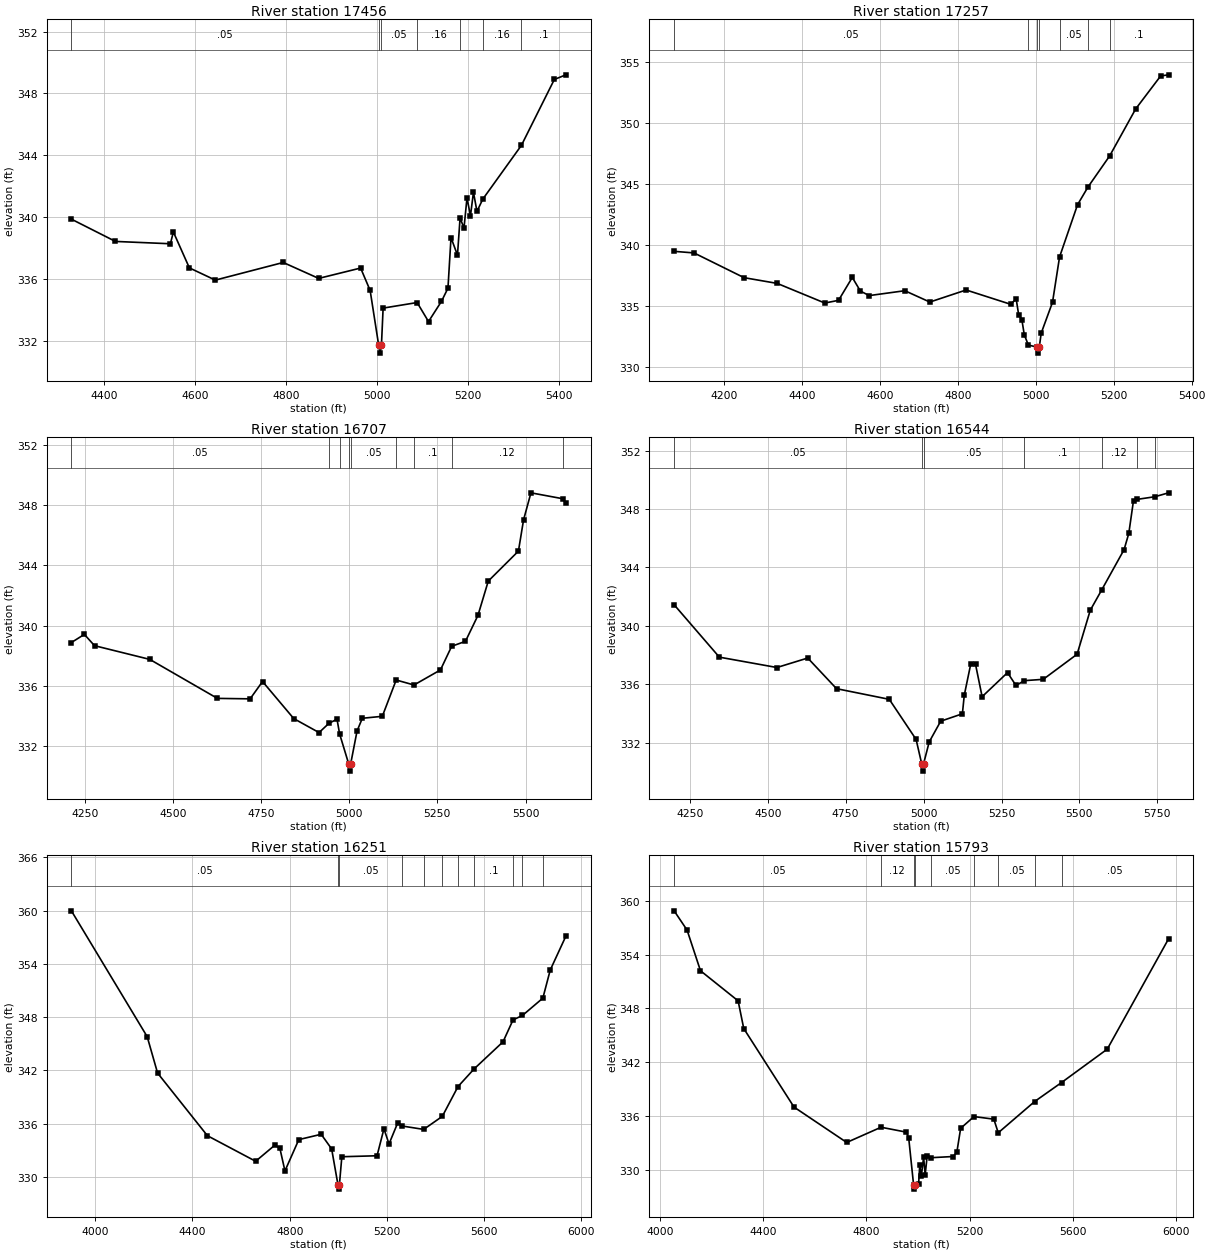
Type RM Length L Ch R = 1 ,17456   ,200,200,200
BEGIN DESCRIPTION:
UNT0491 IN WICK 21.0
END DESCRIPTION:
XS GIS Cut Line= 2
      3535673.13      10271736.7      3534961.45     10270916.53
#Sta/Elev= 30
  4328.7  339.87  4425.5  338.43  4546.1  338.28  4552.7  339.04  4587.8  336.72
  4644.8  335.93  4793.9  337.07  4871.8  336.04  4963.9  336.71  4984.8  335.26
  5003.6  331.71  5006.4  331.21  5009.6  331.71  5013.3  334.12    5088  334.48
    5113  333.25  5141.5  334.56  5155.7  335.41  5162.4  338.68  5176.6  337.54
  5182.3  339.95  5190.9  339.29  5197.5  341.25  5205.1  340.08  5211.7  341.61
  5219.4  340.37  5232.1  341.16    5317  344.64  5389.3   348.9  5414.6   349.2
#Mann= 7 ,-1 , 0
  4328.7     .05       0  5003.6     .03       0  5009.6     .05       0
    5088     .16       0  5182.3      .1       0  5232.1     .16       0
    5317      .1       0
Bank Sta=5003.6,5009.6
XS Rating Curve= 0 ,0
Exp/Cntr=0.3,0.1

Type RM Length L Ch R = 1 ,17257   ,550,550,550
BEGIN DESCRIPTION:
UNT0491 IN WICK 20.0
END DESCRIPTION:
XS GIS Cut Line= 2
      3535837.54     10271778.11      3535056.97      10270777.7
#Sta/Elev= 30
  4071.9  339.46  4122.9  339.33  4251.4   337.3  4336.4  336.83  4458.5  335.22
  4493.8  335.44  4529.1  337.32  4549.9   336.2  4572.5  335.83  4663.9  336.23
  4728.1   335.3  4821.2  336.29  4935.2  335.12  4949.7  335.55    4956  334.27
  4964.2  333.86  4970.5  332.61    4981  331.77    5003  331.61  5005.8  331.11
    5009  331.61  5013.9  332.75  5042.9  335.28    5061     339  5107.1  343.28
  5133.8  344.73  5189.6  347.29  5256.3  351.14  5320.5  353.85  5340.8  353.94
#Mann= 7 ,-1 , 0
  4071.9     .05       0    4981     .12       0    5003     .07       0
    5009     .12       0    5061     .05       0  5133.8     .12       0
  5189.6      .1       0
Bank Sta=5003,5009
XS Rating Curve= 0 ,0
Exp/Cntr=0.3,0.1

Type RM Length L Ch R = 1 ,16707   ,163,163,163
BEGIN DESCRIPTION:
Mapping XS fc0539a7
END DESCRIPTION:
XS GIS Cut Line= 4
       3535929.2     10271786.62      3535565.61     10271337.17
      3535717.26     10271114.27      3535386.83     10270668.84
#Sta/Elev= 30
  4212.1  338.87  4248.9  339.41  4277.7  338.66  4434.4  337.75  4626.2  335.16
    4719  335.13  4754.2  336.28  4842.7  333.82  4914.5  332.89  4942.3   333.5
  4965.4  333.78  4972.8   332.8  4998.3  330.83  5001.1  330.33  5004.3  330.83
  5022.3     333  5037.2  333.84  5093.9  333.97  5133.2  336.38  5183.8  336.05
  5258.8  337.05  5290.6  338.62  5329.7  338.95  5365.1  340.67  5394.4  342.95
  5479.9  344.94  5494.5  347.02  5515.4  348.81  5605.3  348.42  5614.4  348.14
#Mann= 9 ,-1 , 0
  4212.1     .05       0  4942.3     .12       0  4972.8     .05       0
  4998.3     .04       0  5004.3     .05       0  5133.2     .12       0
  5183.8      .1       0  5290.6     .12       0  5605.3      .1       0
Bank Sta=4998.3,5004.3
XS Rating Curve= 0 ,0
Exp/Cntr=0.3,0.1

Type RM Length L Ch R = 1 ,16544   ,293,293,293
BEGIN DESCRIPTION:
Mapping XS 4ea5d18c
END DESCRIPTION:
XS GIS Cut Line= 4
      3536100.94     10271907.21      3535693.51     10271423.04
      3535845.15     10271209.27      3535467.01     10270630.19
#Sta/Elev= 30
  4199.6  341.44  4344.7  337.85  4529.4  337.14  4628.3  337.79  4720.6  335.69
  4889.9  334.96    4976  332.21  4993.9  330.54  4996.6  330.04  4999.9  330.54
    5018  332.04  5054.8  333.46  5124.5  333.97  5130.5  335.24  5151.6  337.41
  5166.7  337.35  5187.8  335.14  5269.3  336.79  5296.4  335.91  5323.3  336.24
  5383.9  336.33  5492.5  338.05  5534.7  341.06  5571.3  342.45  5643.3  345.22
  5658.4  346.33  5673.5  348.58  5684.6  348.66  5741.5  348.84  5786.1  349.11
#Mann= 7 ,-1 , 0
  4199.6     .05       0  4993.9     .03       0  4999.9     .05       0
  5323.3      .1       0  5571.3     .12       0  5684.6     .05       0
  5741.5     .12       0
Bank Sta=4993.9,4999.9
XS Rating Curve= 0 ,0
Exp/Cntr=0.3,0.1

Type RM Length L Ch R = 1 ,16251   ,458,458,458
BEGIN DESCRIPTION:
UNT0491 IN WICK 19.0
END DESCRIPTION:
XS GIS Cut Line= 3
       3536742.1     10272041.64      3536042.11     10271241.64
      3535492.13     10270441.67
#Sta/Elev= 30
    3902  359.99  4213.8  345.81  4256.5  341.71  4461.5  334.65  4659.9  331.77
  4738.6  333.58  4759.5  333.24  4780.4  330.68  4837.4  334.21  4929.4  334.81
  4972.5  333.16  4998.4  329.13  5001.2  328.63  5004.4  329.13  5014.4  332.28
  5159.2  332.39  5187.6  335.43  5208.5  333.72  5244.4  336.11  5262.9  335.74
    5351  335.36  5427.7  336.83  5492.3  340.19  5558.2  342.17  5677.4  345.23
  5718.6   347.7  5757.3   348.2  5841.2  350.15  5871.6  353.32  5935.8  357.13
#Mann= 11 ,-1 , 0
    3902     .05       0  4998.4    .035       0  5004.4     .05       0
  5262.9      .1       0    5351     .05       0  5427.7      .1       0
  5492.3     .05       0  5558.2      .1       0  5718.6     .05       0
  5757.3      .1       0  5841.2     .05       0
Bank Sta=4998.4,5004.4
XS Rating Curve= 0 ,0
Exp/Cntr=0.3,0.1

Type RM Length L Ch R = 1 ,15793   ,467,467,467
BEGIN DESCRIPTION:
UNT0491 IN WICK 18.0
END DESCRIPTION:
XS GIS Cut Line= 3
      3536792.11     10271991.66      3536292.11     10271191.64
      3535742.13     10270391.67
#Sta/Elev= 30
  4055.4  358.89  4105.5  356.74  4157.4   352.2  4303.1  348.84  4324.9  345.75
  4519.5  336.98  4723.5  333.03  4856.5  334.73  4954.6  334.18  4963.4  333.56
  4982.3  328.32    4985  327.82  4988.3  328.32  5001.8  328.36  5006.3  330.53
  5012.3  329.24  5021.2   331.4  5027.2  329.41  5035.2  331.57  5051.4  331.33
  5134.8  331.46  5149.7  331.91  5164.6  334.61  5216.2  335.92  5293.1  335.63
  5310.1  334.11    5451   337.6  5555.2  339.72  5732.2  343.45  5969.6  355.77
#Mann= 9 ,-1 , 0
  4055.4     .05       0  4856.5     .12       0  4982.3     .07       0
  4988.3     .12       0  5051.4     .05       0  5216.2      .1       0
  5310.1     .05       0    5451      .1       0  5555.2     .05       0
Bank Sta=4982.3,4988.3
XS Rating Curve= 0 ,0
Exp/Cntr=0.3,0.1

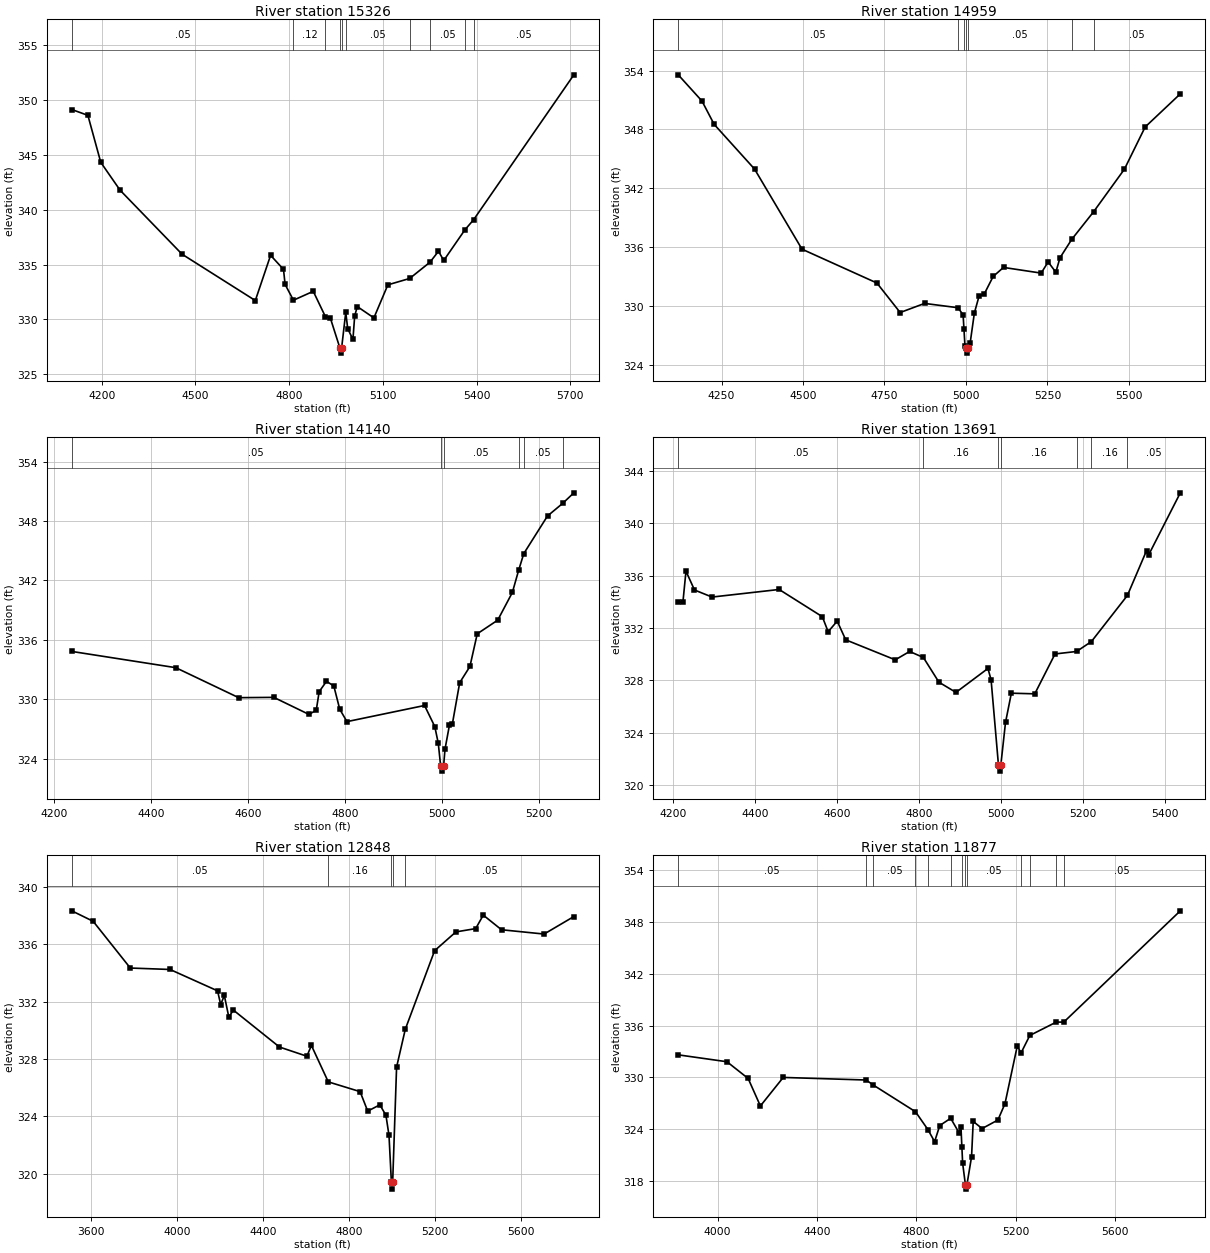
Type RM Length L Ch R = 1 ,15326   ,367,367,367
BEGIN DESCRIPTION:
UNT0491 IN WICK 17.0
END DESCRIPTION:
XS GIS Cut Line= 3
      3536792.11     10271741.68      3536592.11     10270941.64
       3536242.1     10270241.62
#Sta/Elev= 30
    4104  349.12  4155.6  348.59  4196.8  344.31  4258.7  341.77  4457.1  335.94
  4691.6  331.72  4740.5  335.84  4781.8  334.56  4786.9  333.19  4813.6  331.75
  4877.1  332.56  4915.8  330.26  4931.5  330.15    4962  327.43  4964.7  326.93
    4968  327.43  4981.1  330.64  4987.4  329.16  5004.1  328.18  5009.7  330.32
  5018.1  331.17  5071.2  330.14  5115.9  333.15  5185.7  333.73  5250.7  335.21
    5278  336.21  5294.8  335.37  5362.8  338.17  5390.4  339.08  5711.3  352.28
#Mann= 10 ,-1 , 0
    4104     .05       0  4813.6     .12       0  4915.8      .1       0
    4962     .03       0    4968      .1       0  4981.1     .05       0
  5185.7      .1       0  5250.7     .05       0  5362.8      .1       0
  5390.4     .05       0
Bank Sta=4962,4968
XS Rating Curve= 0 ,0
Exp/Cntr=0.3,0.1

Type RM Length L Ch R = 1 ,14959   ,819,819,819
BEGIN DESCRIPTION:
UNT0491 IN WICK 16.0
END DESCRIPTION:
XS GIS Cut Line= 3
      3537542.08     10271091.63      3536577.06     10270542.84
      3536347.88     10270178.24
#Sta/Elev= 30
  4117.1  353.56  4189.9  350.89  4227.3  348.51  4351.3  343.95  4496.9  335.78
  4726.8  332.33  4798.2  329.32  4873.1  330.25  4975.5  329.81  4991.3  329.09
    4994   327.6  4997.1  325.88  4999.9  325.68  5002.6  325.18  5005.9  325.68
    5013  326.22  5025.9  329.27  5040.3     331  5056.2  331.21  5083.6     333
  5115.3  333.92  5230.9  333.34  5252.3  334.48  5275.9  333.43  5288.6   334.9
  5324.9  336.79  5392.1  339.61  5486.4  343.94    5550  348.24  5657.9  351.62
#Mann= 7 ,-1 , 0
  4117.1     .05       0  4975.5     .16       0    4994     .05       0
  4999.9     .03       0  5005.9     .05       0  5324.9      .1       0
  5392.1     .05       0
Bank Sta=4999.9,5005.9
XS Rating Curve= 0 ,0
Exp/Cntr=0.3,0.1

Type RM Length L Ch R = 1 ,14140   ,449,449,449
BEGIN DESCRIPTION:
Mapping XS 2faad888
END DESCRIPTION:
XS GIS Cut Line= 2
      3537474.49     10270485.19      3536608.18     10269919.22
#Sta/Elev= 30
  4236.6  334.83  4450.9  333.19  4580.6  330.16    4653  330.19  4725.4  328.47
  4740.5  328.89  4746.5  330.77  4761.6  331.81  4776.7  331.34  4788.9  328.99
  4803.8  327.74  4963.7  329.37  4984.8  327.24    4992  325.55  4996.9  323.24
  4999.7  322.74  5002.9  323.24  5005.9  324.97    5015  327.39    5021   327.5
  5036.1  331.67  5057.2  333.31  5072.3  336.61  5114.5  337.99  5144.7  340.79
  5157.5  343.01  5168.2  344.71  5217.1  348.51  5248.5  349.79  5271.4  350.85
#Mann= 6 ,-1 , 0
  4236.6     .05       0  4996.9     .03       0  5002.9     .05       0
  5157.5      .1       0  5168.2     .05       0  5248.5      .1       0
Bank Sta=4996.9,5002.9
XS Rating Curve= 0 ,0
Exp/Cntr=0.3,0.1

Type RM Length L Ch R = 1 ,13691   ,843,843,843
BEGIN DESCRIPTION:
UNT0491 IN WICK 14.0
END DESCRIPTION:
XS GIS Cut Line= 3
      3537660.94     10270239.27       3536823.3     10269536.18
      3536693.09     10269562.22
#Sta/Elev= 30
  4211.9  333.96  4223.4  333.99  4230.8  336.34  4251.6   334.9  4294.5  334.36
  4458.4  334.94  4563.8  332.86  4578.1  331.71  4600.2  332.52    4621  331.09
    4742  329.56  4777.1   330.2  4810.7  329.74  4848.7  327.85  4890.3  327.07
  4968.4   328.9  4976.1  328.03    4994  321.55  4996.7  321.05    5000  321.55
  5011.3  324.77  5025.6  327.01  5082.8  326.96  5132.3  330.01    5185   330.2
  5221.2  330.96    5309  334.48  5355.8  337.91  5360.9  337.58  5438.3  342.33
#Mann= 7 ,-1 , 0
  4211.9     .05       0  4810.7     .16       0    4994     .07       0
    5000     .16       0    5185      .1       0  5221.2     .16       0
    5309     .05       0
Bank Sta=4994,5000
XS Rating Curve= 0 ,0
Exp/Cntr=0.3,0.1

Type RM Length L Ch R = 1 ,12848   ,971,971,971
BEGIN DESCRIPTION:
UNT0491 IN WICK 12.0
END DESCRIPTION:
XS GIS Cut Line= 3
      3537991.12     10270306.12      3537704.66     10269425.91
      3536705.86     10268432.31
#Sta/Elev= 30
    3512  338.34  3611.4  337.61  3784.2  334.35  3968.9  334.25  4189.8  332.76
  4204.5   331.8  4221.3  332.44  4242.3  330.92  4263.1  331.42  4477.8  328.84
  4605.1   328.2  4626.3  328.95  4704.7  326.41  4852.6  325.73    4888  324.37
  4944.5  324.81  4972.8  324.08    4987  322.68  4998.1  319.43  5000.9  318.93
  5004.1  319.43  5022.3  327.44  5062.8  330.08  5199.1  335.56  5298.1  336.87
    5390   337.1  5425.4  338.04  5510.2  337.02  5708.2  336.72  5846.5  337.94
#Mann= 5 ,-1 , 0
    3512     .05       0  4704.7     .16       0  4998.1     .07       0
  5004.1     .16       0  5062.8     .05       0
Bank Sta=4998.1,5004.1
XS Rating Curve= 0 ,0
Exp/Cntr=0.3,0.1

Type RM Length L Ch R = 1 ,11877   ,178,178,178
BEGIN DESCRIPTION:
Mapping XS 334d40be
END DESCRIPTION:
XS GIS Cut Line= 2
      3538277.59     10269483.22      3536928.65     10267978.03
#Sta/Elev= 30
  3841.5   332.6  4037.7   331.8  4122.9  329.86  4172.2  326.67  4264.2  329.98
  4597.9  329.68  4627.1  329.09  4796.6     326  4846.6  323.93  4873.5  322.53
  4894.4   324.4  4938.3  325.24  4972.1  323.55  4979.6  324.26  4983.3  321.96
  4986.4  320.03  4997.6  317.52  5000.3  317.02  5003.6  317.52  5022.3  320.77
    5029  324.87  5064.9  324.05  5128.4  325.04  5156.8  326.93  5206.2  333.61
  5221.7  332.83  5256.8  334.85  5363.4   336.4  5393.6   336.4  5862.7  349.31
#Mann= 13 ,-1 , 0
  3841.5     .05       0  4597.9      .1       0  4627.1     .05       0
  4796.6     .16       0  4846.6     .05       0  4938.3     .16       0
  4983.3     .05       0  4997.6     .04       0  5003.6     .05       0
  5221.7      .1       0  5256.8     .05       0  5363.4      .1       0
  5393.6     .05       0
Bank Sta=4997.6,5003.6
XS Rating Curve= 0 ,0
Exp/Cntr=0.3,0.1

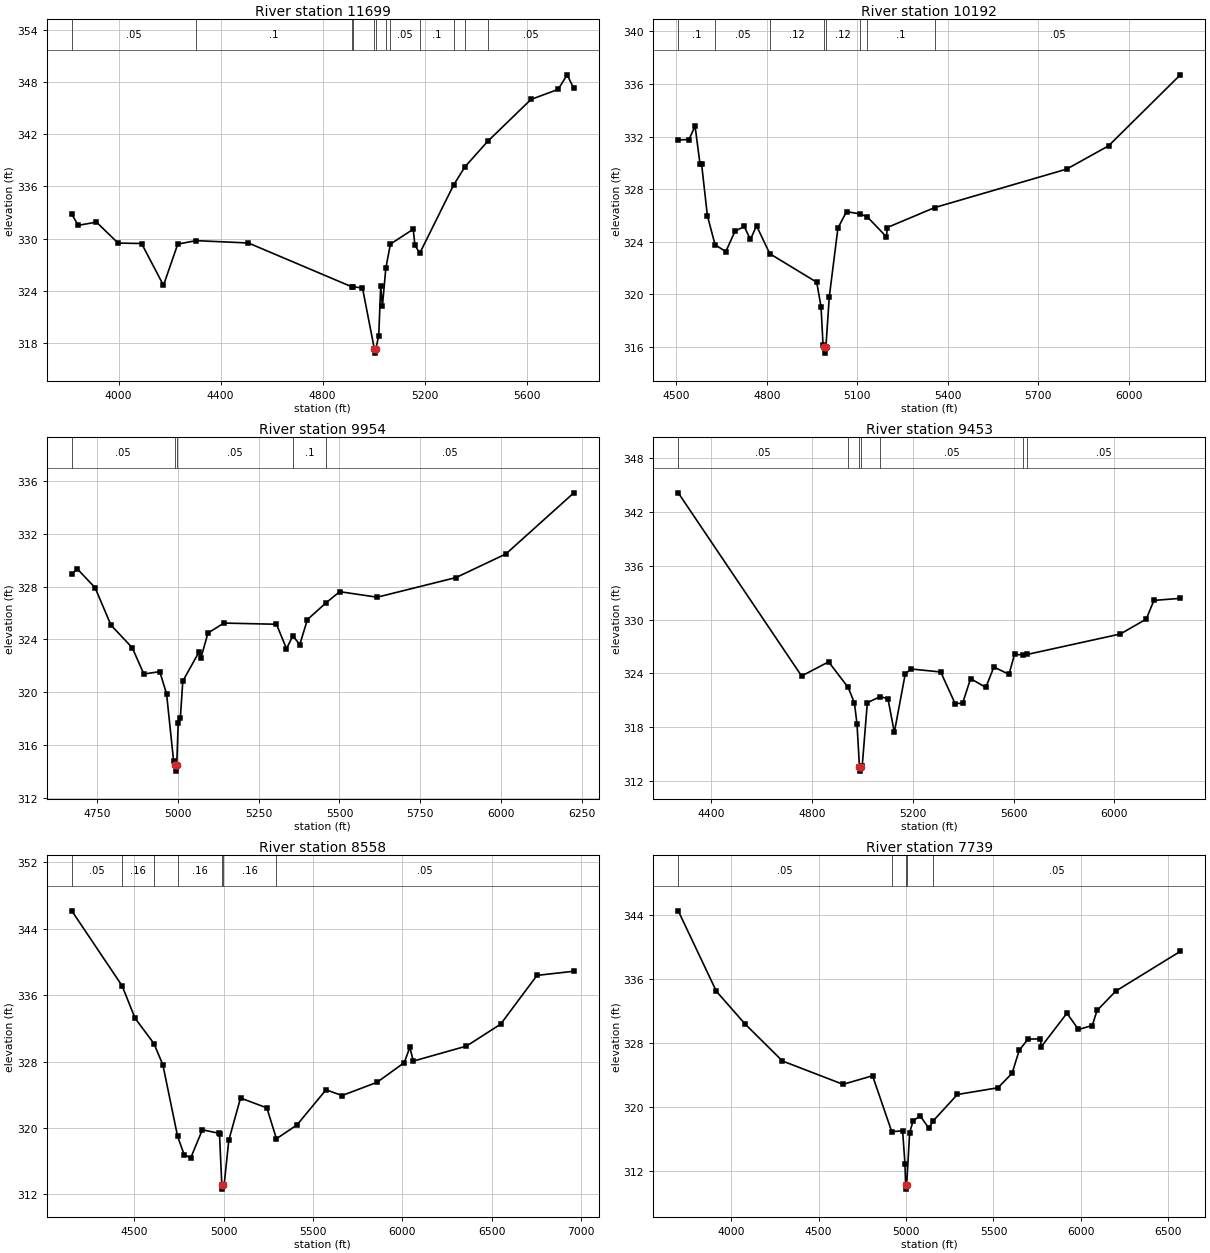
Type RM Length L Ch R = 1 ,11699   ,1507,1507,1507
BEGIN DESCRIPTION:
Mapping XS aa9b298e
END DESCRIPTION:
XS GIS Cut Line= 2
      3538360.92     10269379.04      3537091.27     10267875.24
#Sta/Elev= 30
  3816.5   332.8  3841.9  331.53  3913.3   331.9  3997.9  329.49  4090.2  329.44
    4176  324.63  4231.9  329.37  4303.8  329.77  4508.9   329.5  4914.5  324.46
  4919.3  324.47  4956.1  324.33  5002.5  317.34  5005.3  316.84  5008.5  317.34
  5019.8  318.86  5027.6  324.61  5034.1  322.22  5047.5  326.59  5065.5  329.38
    5155  331.08  5161.6  329.24  5180.5  328.32  5313.5  336.18  5357.9  338.26
  5446.5  341.17  5616.6     346  5723.2  347.16  5758.3  348.83  5784.6  347.27
#Mann= 12 ,-1 , 0
  3816.5     .05       0  4303.8      .1       0  4914.5     .05       0
  4919.3     .16       0  5002.5     .07       0  5008.5     .16       0
  5047.5      .1       0  5065.5     .05       0  5180.5      .1       0
  5313.5     .05       0  5357.9      .1       0  5446.5     .05       0
Bank Sta=5002.5,5008.5
XS Rating Curve= 0 ,0
Exp/Cntr=0.3,0.1

Type RM Length L Ch R = 1 ,10192   ,238,238,238
BEGIN DESCRIPTION:
UNT0491 IN WICK 11.0
END DESCRIPTION:
XS GIS Cut Line= 4
      3538601.18     10269206.38      3538533.09     10268856.61
       3538787.4     10268640.18      3538548.73     10267696.36
#Sta/Elev= 30
  4506.7  331.74  4542.1  331.77  4562.5  332.79    4579  329.88  4584.1  329.91
  4603.2  325.99  4628.7  323.77  4664.3  323.25  4694.9   324.8  4725.5  325.16
  4745.8  324.17  4766.2  325.21    4810  323.09  4965.6  320.92  4979.9  319.06
  4986.5  316.17  4990.1  316.03  4992.8  315.53  4996.1  316.03  5007.3  319.82
  5035.9  325.04  5064.4  326.29  5110.3  326.11  5133.6  325.88  5196.8  324.37
  5199.4  325.08  5356.9   326.6  5793.7  329.52  5932.7  331.29  6170.5  336.69
#Mann= 8 ,-1 , 0
  4506.7      .1       0  4628.7     .05       0    4810     .12       0
  4990.1     .07       0  4996.1     .12       0  5110.3     .05       0
  5133.6      .1       0  5356.9     .05       0
Bank Sta=4990.1,4996.1
XS Rating Curve= 0 ,0
Exp/Cntr=0.3,0.1

Type RM Length L Ch R = 1 ,9954    ,501,501,501
BEGIN DESCRIPTION:
Mapping XS 03d9b9ca
END DESCRIPTION:
XS GIS Cut Line= 4
       3538832.4     10269165.82      3538759.25     10268976.72
      3539003.68     10268703.74      3538775.31     10267747.41
#Sta/Elev= 30
  4672.2  328.98  4689.8  329.33  4744.3  327.92  4793.5  325.08    4859  323.38
  4895.1  321.38  4944.4  321.56  4965.4  319.86  4987.1  314.77  4990.8  314.52
  4993.5  314.02  4996.8  314.52  5001.3  317.66    5008  318.07  5015.5  320.84
  5064.8  323.01  5071.5  322.59  5093.2  324.48  5142.5  325.24  5305.2  325.15
  5336.1   323.3  5355.8  324.27  5377.2  323.61  5400.9  325.51  5457.8  326.76
  5500.6  327.62  5616.5   327.2  5860.4  328.69  6014.6  330.48  6224.6  335.11
#Mann= 5 ,-1 , 0
  4672.2     .05       0  4990.8    .035       0  4996.8     .05       0
  5355.8      .1       0  5457.8     .05       0
Bank Sta=4990.8,4996.8
XS Rating Curve= 0 ,0
Exp/Cntr=0.3,0.1

Type RM Length L Ch R = 1 ,9453    ,895,895,895
BEGIN DESCRIPTION:
UNT0491 IN WICK 10.0
END DESCRIPTION:
XS GIS Cut Line= 2
      3539433.82     10269754.01      3538999.79     10267809.57
#Sta/Elev= 30
  4268.9  344.16  4758.4  323.71  4865.6  325.29  4943.3  322.43  4968.1  320.69
  4978.3  318.34    4988  313.59  4990.7  313.09    4994  313.59  4998.8  313.61
  5019.3  320.73  5071.4  321.42  5101.3  321.14  5126.4  317.42  5169.9  323.97
  5193.5  324.49  5310.4  324.16  5367.7  320.62  5397.3  320.68  5429.1  323.42
  5489.3  322.43  5521.4  324.71  5581.4   323.9  5603.3  326.12  5638.5  326.07
  5654.1  326.12  6023.4   328.4  6125.9  330.06  6156.6  332.15  6261.2  332.38
#Mann= 7 ,-1 , 0
  4268.9     .05       0  4943.3     .16       0    4988     .07       0
    4994     .16       0  5071.4     .05       0  5638.5      .1       0
  5654.1     .05       0
Bank Sta=4988,4994
XS Rating Curve= 0 ,0
Exp/Cntr=0.3,0.1

Type RM Length L Ch R = 1 ,8558    ,819,819,819
BEGIN DESCRIPTION:
UNT0491 IN WICK 8.0
END DESCRIPTION:
XS GIS Cut Line= 2
       3539581.4     10269849.51       3540110.9     10267089.14
#Sta/Elev= 30
  4149.2  346.17  4430.8  337.14  4503.4  333.23    4609  330.18  4659.2  327.61
  4741.7  318.98  4778.3  316.79  4815.2  316.39  4880.2  319.78  4971.2  319.37
  4976.3  319.22  4989.2  313.13  4991.9  312.63  4995.2  313.13  5002.3  313.15
  5028.3  318.53    5094  323.61  5241.4  322.42  5294.9   318.7  5409.6  320.36
  5572.6   324.6  5662.4  323.91  5857.7   325.5  6010.4  327.87  6041.7  329.73
  6061.3  328.06  6358.8  329.87  6550.1  332.51  6753.7  338.39  6959.9  338.89
#Mann= 7 ,-1 , 0
  4149.2     .05       0  4430.8     .16       0    4609     .05       0
  4741.7     .16       0  4989.2     .07       0  4995.2     .16       0
  5294.9     .05       0
Bank Sta=4989.2,4995.2
XS Rating Curve= 0 ,0
Exp/Cntr=0.3,0.1

Type RM Length L Ch R = 1 ,7739    ,1209,1209,1209
BEGIN DESCRIPTION:
UNT0491 IN WICK 7.0
END DESCRIPTION:
XS GIS Cut Line= 4
      3539815.76     10269901.62      3540308.14     10269264.29
      3540510.22     10267844.32      3540336.85     10267237.55
#Sta/Elev= 30
  3697.6  344.53  3915.6  334.47  4079.5  330.39  4293.2  325.76  4639.8  322.84
  4808.7  323.91  4918.6  316.91  4980.4  317.04    4994  312.91  4997.6  310.24
  5000.3  309.74  5003.6  310.24  5020.8   316.8    5041   318.3  5081.4  318.88
  5130.6  317.35  5156.6   318.3  5293.5  321.57  5525.8  322.41  5606.6  324.23
    5647  327.08  5697.4   328.5  5768.2  328.52  5773.3  327.54    5920  331.73
  5985.9   329.7  6064.8  330.19  6092.5  332.08  6199.1  334.49  6568.3  339.46
#Mann= 5 ,-1 , 0
  3697.6     .05       0  4918.6     .16       0  4997.6     .07       0
  5003.6     .16       0  5156.6     .05       0
Bank Sta=4997.6,5003.6
XS Rating Curve= 0 ,0
Exp/Cntr=0.3,0.1