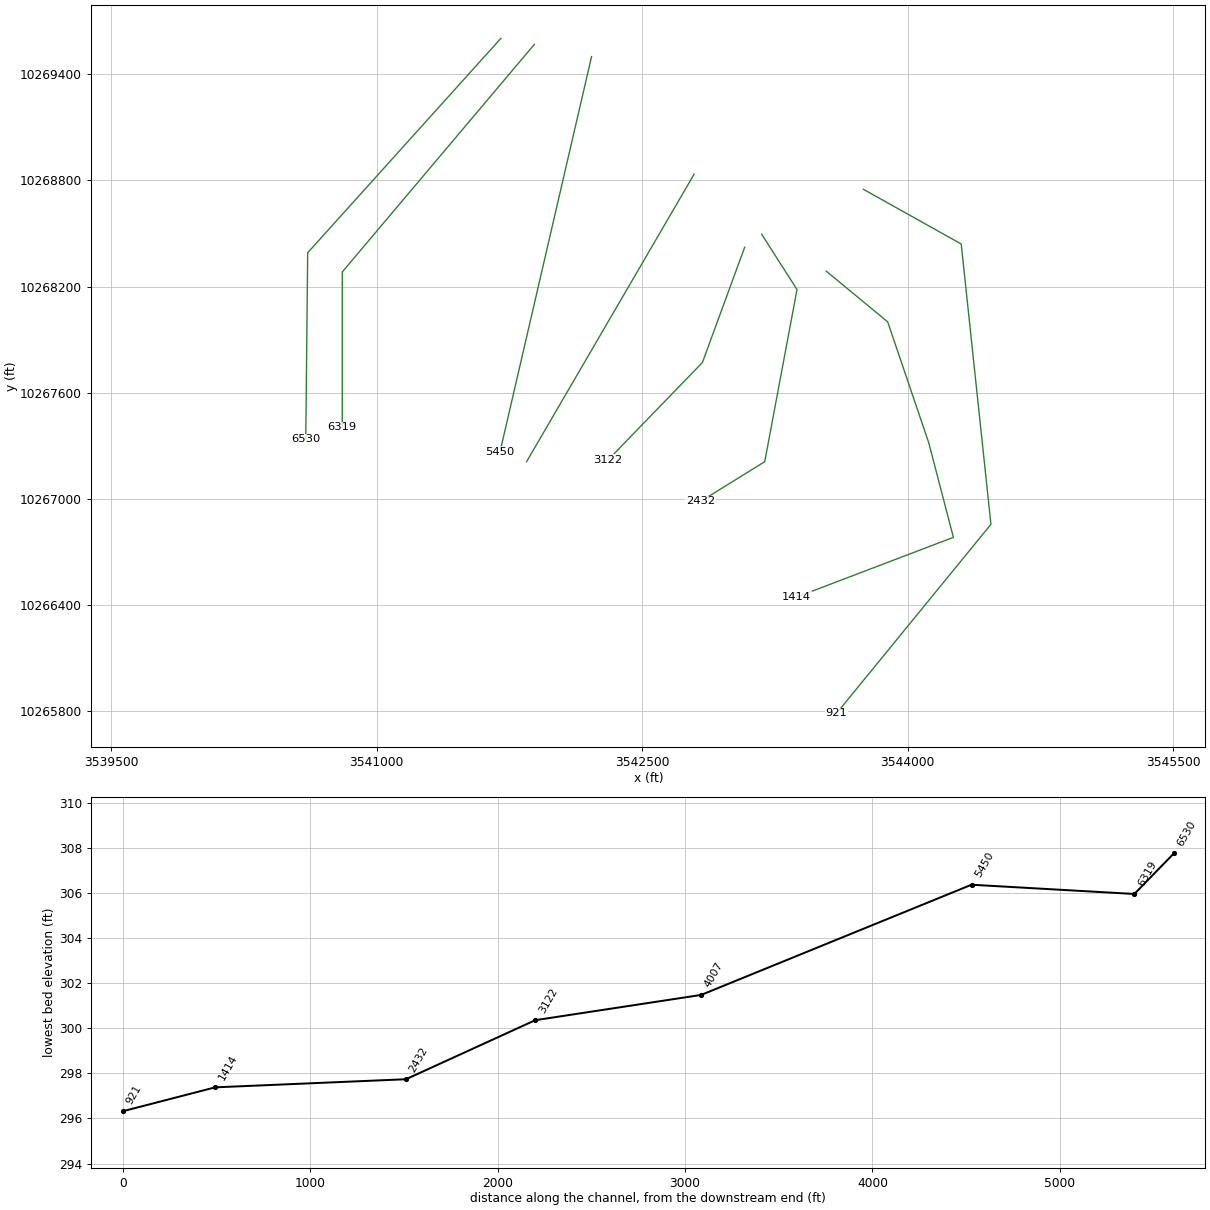
HEC-RAS study WICKSONCREEKTRIB.prj: WICKSON CREEK TRIB 41

--- WICKSONCREEKTRIB.g01 (geometry) --- (continued)

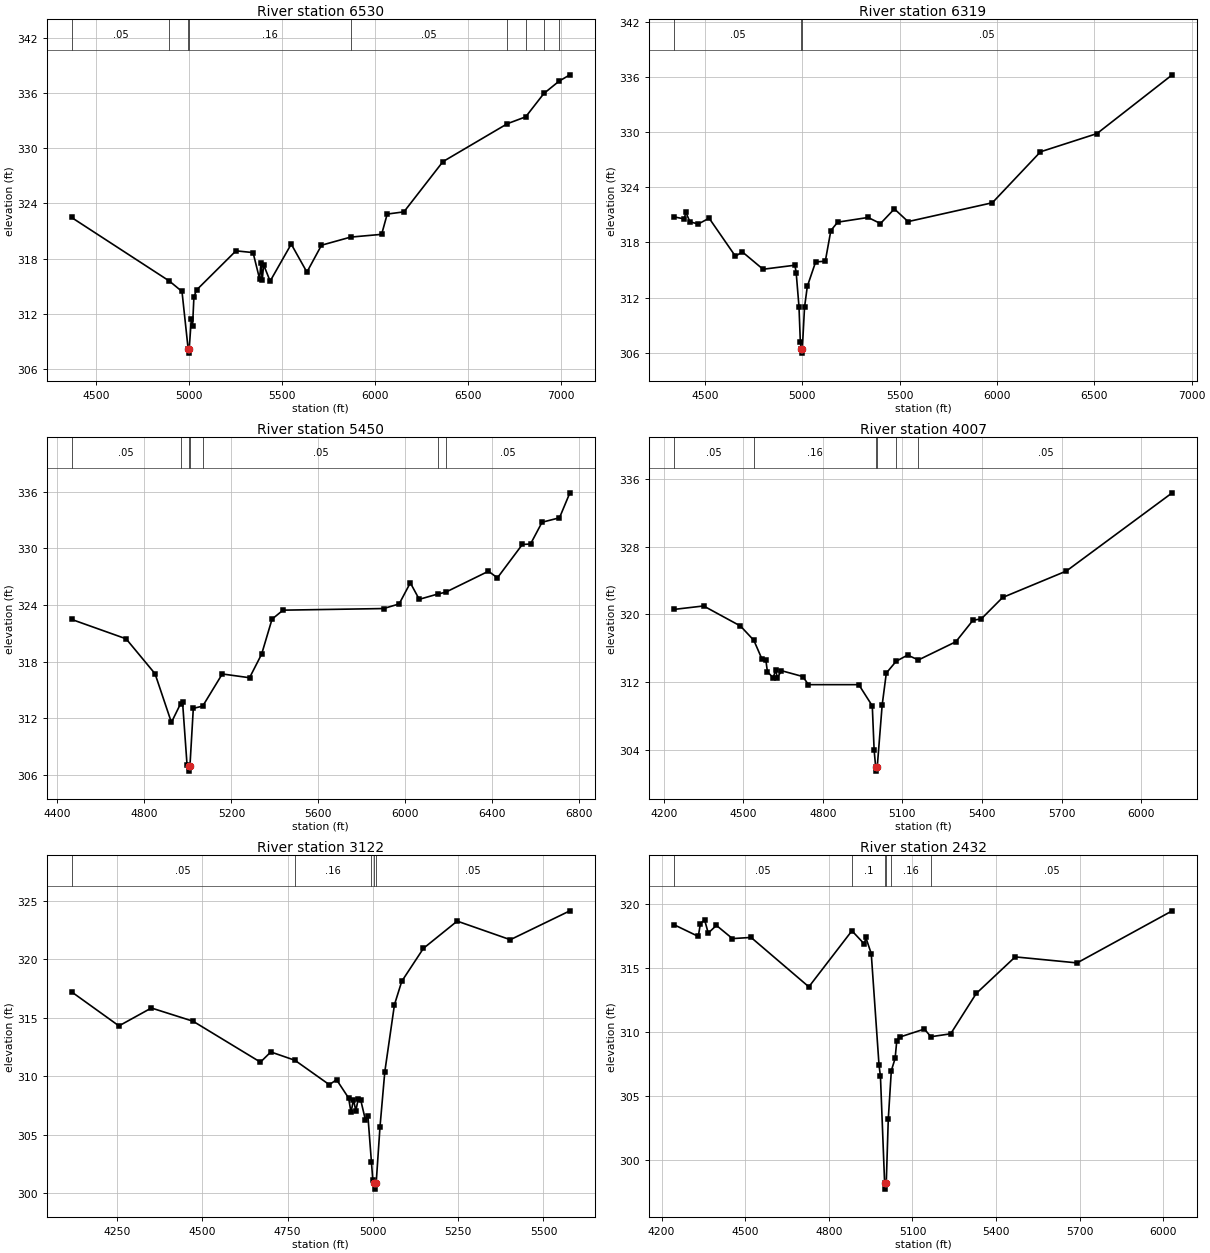
Type RM Length L Ch R = 1 ,6530    ,211,211,211
BEGIN DESCRIPTION:
UNT0491 IN WICK 6.0
END DESCRIPTION:
XS GIS Cut Line= 3
      3541701.93     10269601.79      3540610.31     10268390.61
      3540599.46     10267338.08
#Sta/Elev= 30
  4367.4  322.48  4893.9  315.58  4961.9  314.45  4994.8  308.26  4997.5  307.76
  5000.8  308.26    5012  311.43  5018.7  310.67  5026.2  313.87  5040.4  314.61
  5252.6  318.86  5344.6  318.67  5379.7  315.81  5387.2  317.57  5393.9  315.65
  5401.4  317.35  5436.5  315.57  5550.1  319.59  5634.5  316.55    5713  319.47
    5870  320.35  6036.9  320.65  6066.9  322.85  6156.9  323.09  6366.9  328.54
  6714.2  332.66  6812.5   333.4  6910.7  335.94  6992.7  337.28  7050.5  337.96
#Mann= 9 ,-1 , 0
  4367.4     .05       0  4893.9     .16       0  4994.8     .07       0
  5000.8     .16       0    5870     .05       0  6714.2      .1       0
  6812.5     .05       0  6910.7      .1       0  6992.7     .05       0
Bank Sta=4994.8,5000.8
XS Rating Curve= 0 ,0
Exp/Cntr=0.3,0.1

Type RM Length L Ch R = 1 ,6319    ,869,869,869
BEGIN DESCRIPTION:
Mapping XS 9ce8cc28
END DESCRIPTION:
XS GIS Cut Line= 3
      3541891.25     10269568.09      3540805.63     10268282.11
      3540805.63     10267404.96
#Sta/Elev= 30
    4340  320.78  4393.6  320.55  4400.8   321.3  4422.2  320.24  4465.1     320
    4521  320.63  4656.2  316.49  4691.4  316.97    4798  315.08  4961.7  315.52
  4968.3  314.69  4982.6  311.02  4989.7  307.12  4993.9  306.46  4996.6  305.96
  4999.9  306.46  5011.2  310.96  5025.5  313.22  5068.2  315.88  5117.8  315.95
  5146.4  319.29  5181.5   320.2  5337.5  320.71  5401.3  320.05  5472.7  321.64
    5543  320.26    5976  322.31  6223.4  327.85  6513.4  329.83  6900.1  336.22
#Mann= 3 ,-1 , 0
    4340     .05       0  4993.9     .04       0  4999.9     .05       0
Bank Sta=4993.9,4999.9
XS Rating Curve= 0 ,0
Exp/Cntr=0.3,0.1

Type RM Length L Ch R = 1 ,5450    ,1443,1443,1443
BEGIN DESCRIPTION:
Mapping XS 1889b036
END DESCRIPTION:
XS GIS Cut Line= 2
      3542214.17     10269498.69      3541697.04     10267267.02
#Sta/Elev= 30
  4465.3  322.47  4715.9  320.41  4849.1   316.7  4924.2  311.54  4966.3  313.52
  4975.5  313.69    4996  307.07  5003.3  306.87  5006.1  306.37  5009.3  306.87
  5024.9  313.03  5068.1  313.27  5158.1  316.68  5283.5  316.28  5339.1  318.79
  5386.9   322.5  5437.4  323.45  5899.4  323.62  5971.2  324.11  6022.5  326.35
  6063.6   324.6  6150.2  325.17  6184.5  325.35  6381.8  327.58  6422.9  326.88
  6537.6  330.42  6575.2  330.47  6628.2  332.78  6708.3  333.25  6756.1   335.9
#Mann= 7 ,-1 , 0
  4465.3     .05       0  4966.3      .1       0  5003.3     .07       0
  5009.3      .1       0  5068.1     .05       0  6150.2      .1       0
  6184.5     .05       0
Bank Sta=5003.3,5009.3
XS Rating Curve= 0 ,0
Exp/Cntr=0.3,0.1

Type RM Length L Ch R = 1 ,4007    ,885,885,885
BEGIN DESCRIPTION:
UNT0491 IN WICK 4.0
END DESCRIPTION:
XS GIS Cut Line= 2
      3542793.18     10268833.86      3541847.05     10267210.68
#Sta/Elev= 30
  4238.4  320.59  4350.3     321  4489.3  318.63  4539.8  316.94  4569.5  314.79
  4585.2  314.59    4591  313.21  4612.5  312.53  4622.5  313.43  4628.2  312.51
    4644  313.35  4724.2  312.66  4745.7   311.7  4935.5   311.7  4986.4  309.19
  4993.3  303.99  4999.1  301.98  5001.8  301.48  5005.1  301.98  5023.6  309.28
  5039.3  313.07  5076.6  314.47  5119.5  315.19  5160.4  314.62  5301.5  316.77
    5366  319.31  5397.4  319.47  5477.7     322  5718.3  325.13  6117.2  334.37
#Mann= 6 ,-1 , 0
  4238.4     .05       0  4539.8     .16       0  4999.1     .07       0
  5005.1     .16       0  5076.6      .1       0  5160.4     .05       0
Bank Sta=4999.1,5005.1
XS Rating Curve= 0 ,0
Exp/Cntr=0.3,0.1

Type RM Length L Ch R = 1 ,3122    ,690,690,690
BEGIN DESCRIPTION:
Mapping XS bedc9903
END DESCRIPTION:
XS GIS Cut Line= 3
      3543079.22     10268421.98      3542840.51     10267770.95
      3542306.85     10267219.93
#Sta/Elev= 30
  4116.9  317.23  4255.7  314.32  4350.8  315.85  4472.8  314.72  4670.4  311.22
  4700.9  312.09  4771.4  311.38  4872.4  309.29  4893.5  309.72  4928.9  308.15
  4935.9  306.92  4943.1  308.01  4950.1  307.06  4957.2   308.1  4964.2     308
  4978.3  306.25  4985.5  306.58  4995.8  302.66  4999.7  301.18  5003.6  300.86
  5006.4  300.36  5009.6  300.86  5020.8  305.67  5034.9  310.39  5063.2  316.13
  5084.6  318.13  5148.1  320.95  5247.1  323.28  5402.8  321.69  5577.4  324.16
#Mann= 5 ,-1 , 0
  4116.9     .05       0  4771.4     .16       0  4995.8     .05       0
  5003.6     .03       0  5009.6     .05       0
Bank Sta=5003.6,5009.6
XS Rating Curve= 0 ,0
Exp/Cntr=0.3,0.1

Type RM Length L Ch R = 1 ,2432    ,1018,1018,1018
BEGIN DESCRIPTION:
UNT0491 IN WICK 3.0
END DESCRIPTION:
XS GIS Cut Line= 4
      3543175.14     10268495.37       3543374.8     10268182.86
      3543192.51     10267210.63      3542829.29     10266985.78
#Sta/Elev= 30
  4244.4  318.41  4331.9  317.49  4339.4  318.49  4354.6  318.78  4367.5  317.75
  4396.9  318.35  4454.4  317.32  4521.2  317.41  4728.4  313.55  4882.9  317.93
  4927.6  316.89  4932.6  317.41  4952.2  316.15  4980.1  307.43  4985.2  306.55
  5000.1  298.24  5002.9  297.74  5006.1  298.24  5013.3  303.22  5024.2     307
  5037.8  307.95  5043.8  309.35    5054  309.62  5142.9  310.25    5166  309.65
  5237.1  309.88  5328.7  313.03  5468.5  315.89  5690.5  315.42  6031.6  319.49
#Mann= 6 ,-1 , 0
  4244.4     .05       0  4882.9      .1       0  5000.1     .07       0
  5006.1      .1       0  5024.2     .16       0    5166     .05       0
Bank Sta=5000.1,5006.1
XS Rating Curve= 0 ,0
Exp/Cntr=0.3,0.1

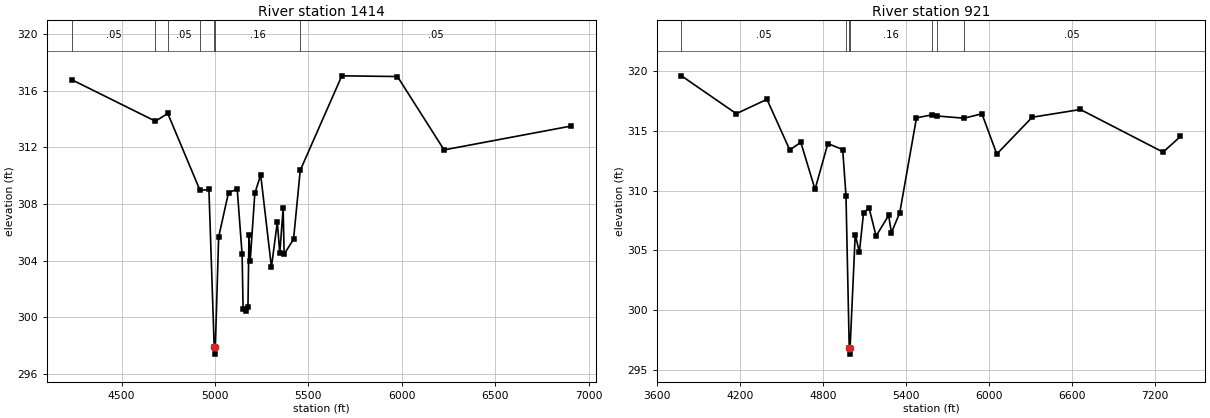
Type RM Length L Ch R = 1 ,1414    ,493,493,493
BEGIN DESCRIPTION:
UNT0491 IN WICK 2.0
END DESCRIPTION:
XS GIS Cut Line= 5
      3543539.72     10268287.03      3543886.95     10268000.57
      3544119.27     10267316.84      3544258.25     10266783.19
      3543372.99     10266446.05
#Sta/Elev= 30
  4232.8   316.8  4681.4  313.86  4747.4  314.41  4920.3  308.96  4967.7  309.03
  4996.1  297.88  4998.8  297.38  5002.1  297.88  5019.8  305.66  5072.6  308.81
  5119.3  309.05  5145.4  304.44  5150.7  300.58  5167.6  300.42  5176.8  300.74
  5182.1  305.79  5188.8  303.98  5213.5  308.76  5244.9  310.06  5302.4  303.53
  5333.8  306.72  5347.2  304.52  5365.1  307.71  5370.4  304.45  5420.8  305.51
  5456.5  310.38  5679.2  317.07    5977  317.02  6226.5  311.83  6903.8  313.51
#Mann= 7 ,-1 , 0
  4232.8     .05       0  4681.4     .16       0  4747.4     .05       0
  4920.3     .16       0  4996.1     .07       0  5002.1     .16       0
  5456.5     .05       0
Bank Sta=4996.1,5002.1
XS Rating Curve= 0 ,0
Exp/Cntr=0.3,0.1

Type RM Length L Ch R = 1 ,921     ,0,0,0
BEGIN DESCRIPTION:
UNT0491 IN WICK 1.0
END DESCRIPTION:
XS GIS Cut Line= 4
      3543749.98       10268749.      3544302.52     10268440.18
      3544470.44     10266856.65      3543598.04     10265788.93
#Sta/Elev= 30
  3777.4  319.63  4173.4  316.46  4394.9  317.66  4559.7  313.42  4639.3  314.06
  4742.1  310.12  4834.7  313.96  4941.9  313.45  4965.6   309.6  4989.2  296.82
  4991.9  296.32  4995.2  296.82  5032.4  306.32  5062.6  304.87  5092.7  308.18
  5132.9  308.54  5183.2  306.21  5273.7  307.94  5293.8  306.49  5354.2  308.17
  5474.9  316.11  5589.9  316.37  5621.1  316.27  5817.8  316.08  5947.5  316.45
    6055  313.08  6310.5  316.16  6658.7  316.81    7256  313.24  7381.6  314.55
#Mann= 7 ,-1 , 0
  3777.4     .05       0  4965.6     .16       0  4989.2     .07       0
  4995.2     .16       0  5589.9     .05       0  5621.1     .16       0
  5817.8     .05       0
Bank Sta=4989.2,4995.2
XS Rating Curve= 0 ,0
Exp/Cntr=0.3,0.1

Chan Stop Cuts=-1
Use User Specified Reach Order=0
Composite Channel Slope=5