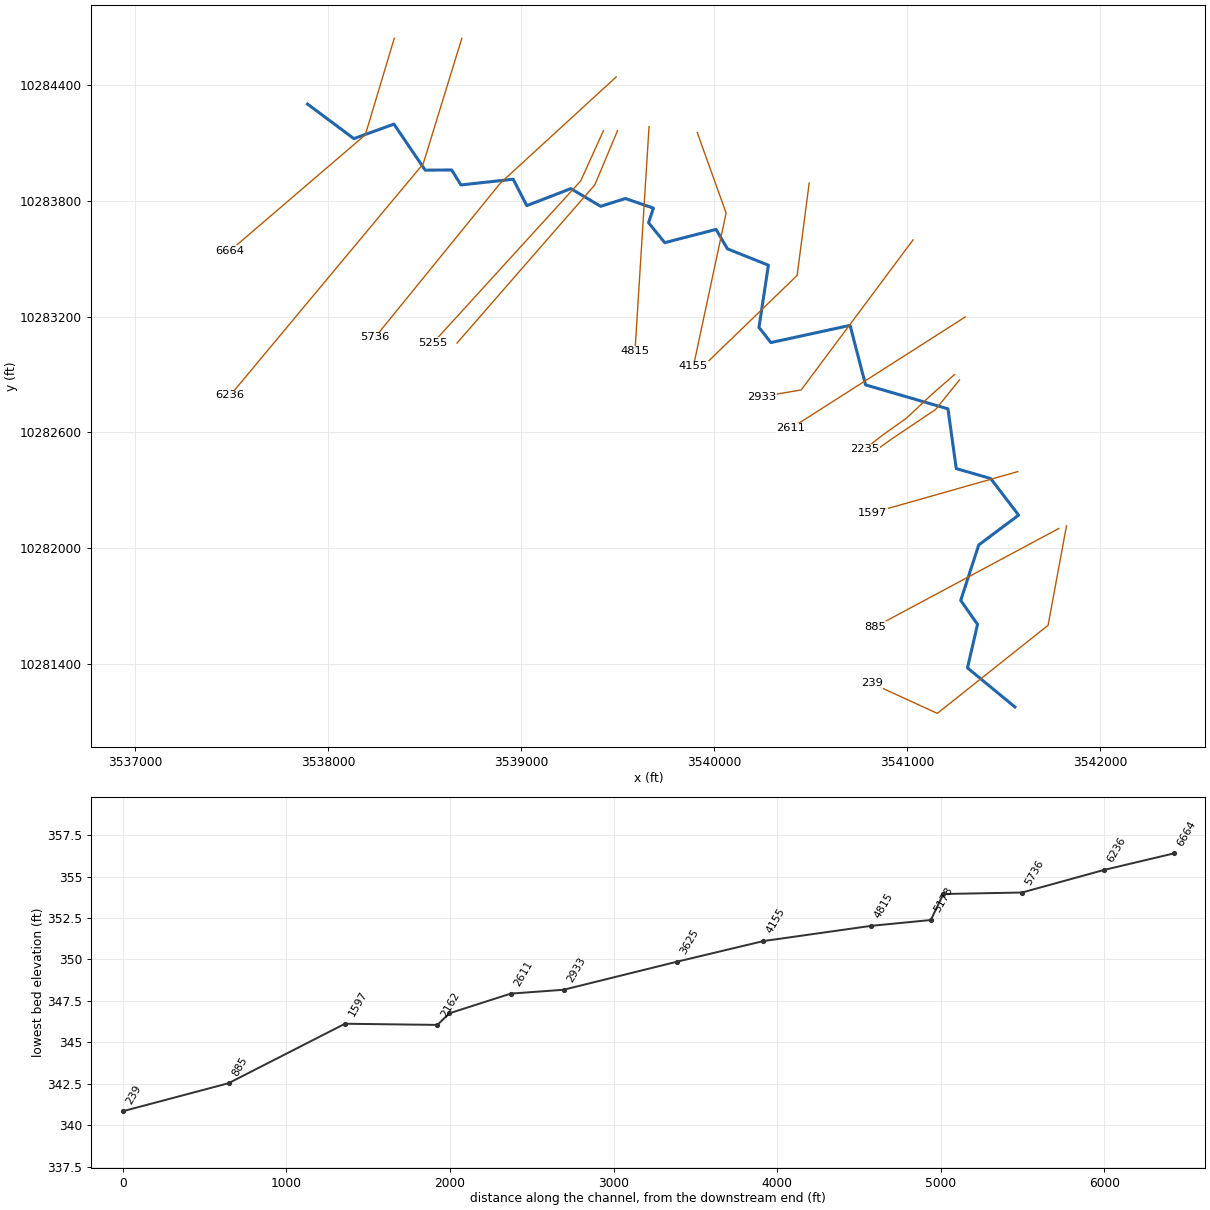
--- WICKSONCREEKTRIB.prj (project) ---

Proj Title=WICKSON CREEK TRIB 45
Current Plan=p01
Default Exp/Contr=0.3,0.1
English Units
Geom File=g01
Flow File=f01
Plan File=p01
Y Axis Title=Elevation
X Axis Title(PF)=Main Channel Distance
X Axis Title(XS)=Station
BEGIN DESCRIPTION:
UNT0488 IN WICK
END DESCRIPTION:
DSS Export Rating Curves= 0
DSS Export Rating Curve Sorted= 0
DSS Export Volume Flow Curves= 0
DXF Filename=UNT0488 IN WICK.
DXF OffsetX= 0
DXF OffsetY= 0
DXF ScaleX= 1
DXF ScaleY= 10

--- WICKSONCREEKTRIB.p01 (plan) ---

Plan Title=Multiple Run
Short Identifier=Multiple
Geom File=g01
Flow File=f01
Subcritical Flow
K Sum by GR= 0
Std Step Tol= 0.01
Critical Tol= 0.01
Num of Std Step Trials= 20
Max Error Tol= 0.3
Flow Tol Ratio= 0.001
Split Flow NTrial= 30
Split Flow Tol= 0.02
Split Flow Ratio= 0.02
Log Output Level= 0
Friction Slope Method= 1
Unsteady Friction Slope Method= 2
Unsteady Bridges Friction Slope Method= 1
Parabolic Critical Depth
Global Vel Dist=  1 , 1 , 1
Global Log Level= 0
CheckData=True
Encroach Param= -1, 0, 0, 0
BEGIN DESCRIPTION:
Multiple Run
END DESCRIPTION:

--- WICKSONCREEKTRIB.f01 (steady flow) ---

Flow Title=Multiple
Program Version=4.10
Number of Profiles= 7
Profile Names=10-year,25-year,50-year,1pct_min,100-year,1pct_plu,500-year
River Rch & RM=UNT0488 IN WICK,Reach-1         ,6664
     670     911    1108     987    1335    1805    1942
River Rch & RM=WICKSONCRTRB45,Reach-1         ,6664
     670     911    1108     987    1335    1805    1942
Boundary for River Rch & Prof#=WICKSONCRTRB45,Reach-1         , 1
Up Type= 0
Dn Type= 3
Dn Slope=0.005
Boundary for River Rch & Prof#=WICKSONCRTRB45,Reach-1         , 2
Up Type= 0
Dn Type= 3
Dn Slope=0.005
Boundary for River Rch & Prof#=WICKSONCRTRB45,Reach-1         , 3
Up Type= 0
Dn Type= 3
Dn Slope=0.005
Boundary for River Rch & Prof#=WICKSONCRTRB45,Reach-1         , 4
Up Type= 0
Dn Type= 3
Dn Slope=0.005
Boundary for River Rch & Prof#=WICKSONCRTRB45,Reach-1         , 5
Up Type= 0
Dn Type= 3
Dn Slope=0.005
Boundary for River Rch & Prof#=WICKSONCRTRB45,Reach-1         , 6
Up Type= 0
Dn Type= 3
Dn Slope=0.005
Boundary for River Rch & Prof#=WICKSONCRTRB45,Reach-1         , 7
Up Type= 0
Dn Type= 3
Dn Slope=0.005
DSS Import GetInterval= 0
DSS Import GetPeak= 0
DSS Import FillOption= 0

--- WICKSONCREEKTRIB.g01 (geometry) ---

Geom Title=Existing Conditions
Program Version=4.10

River Reach=WICKSONCRTRB45  ,Reach-1
Reach XY= 30
      3537892.49     10284301.18      3538132.89     10284121.99
      3538340.36     10284197.08      3538502.25      10283958.8
      3538639.84     10283959.23      3538687.58     10283881.97
      3538958.41     10283911.49      3539028.73     10283774.77
      3539257.02     10283862.88      3539411.54      10283771.3
      3539540.01     10283811.66      3539684.98     10283761.75
       3539659.8     10283686.23      3539743.57     10283582.93
      3540009.63     10283651.51       3540068.6      10283550.8
      3540280.73     10283466.14      3540232.01     10283143.94
      3540293.54     10283065.18      3540703.99     10283154.33
       3540784.2     10282845.99      3541211.28     10282721.69
       3541254.1     10282412.21      3541432.54     10282360.71
      3541577.35     10282171.04      3541370.65     10282016.48
      3541277.34     10281729.25       3541364.4     10281605.02
      3541312.32      10281379.5      3541558.15      10281176.9

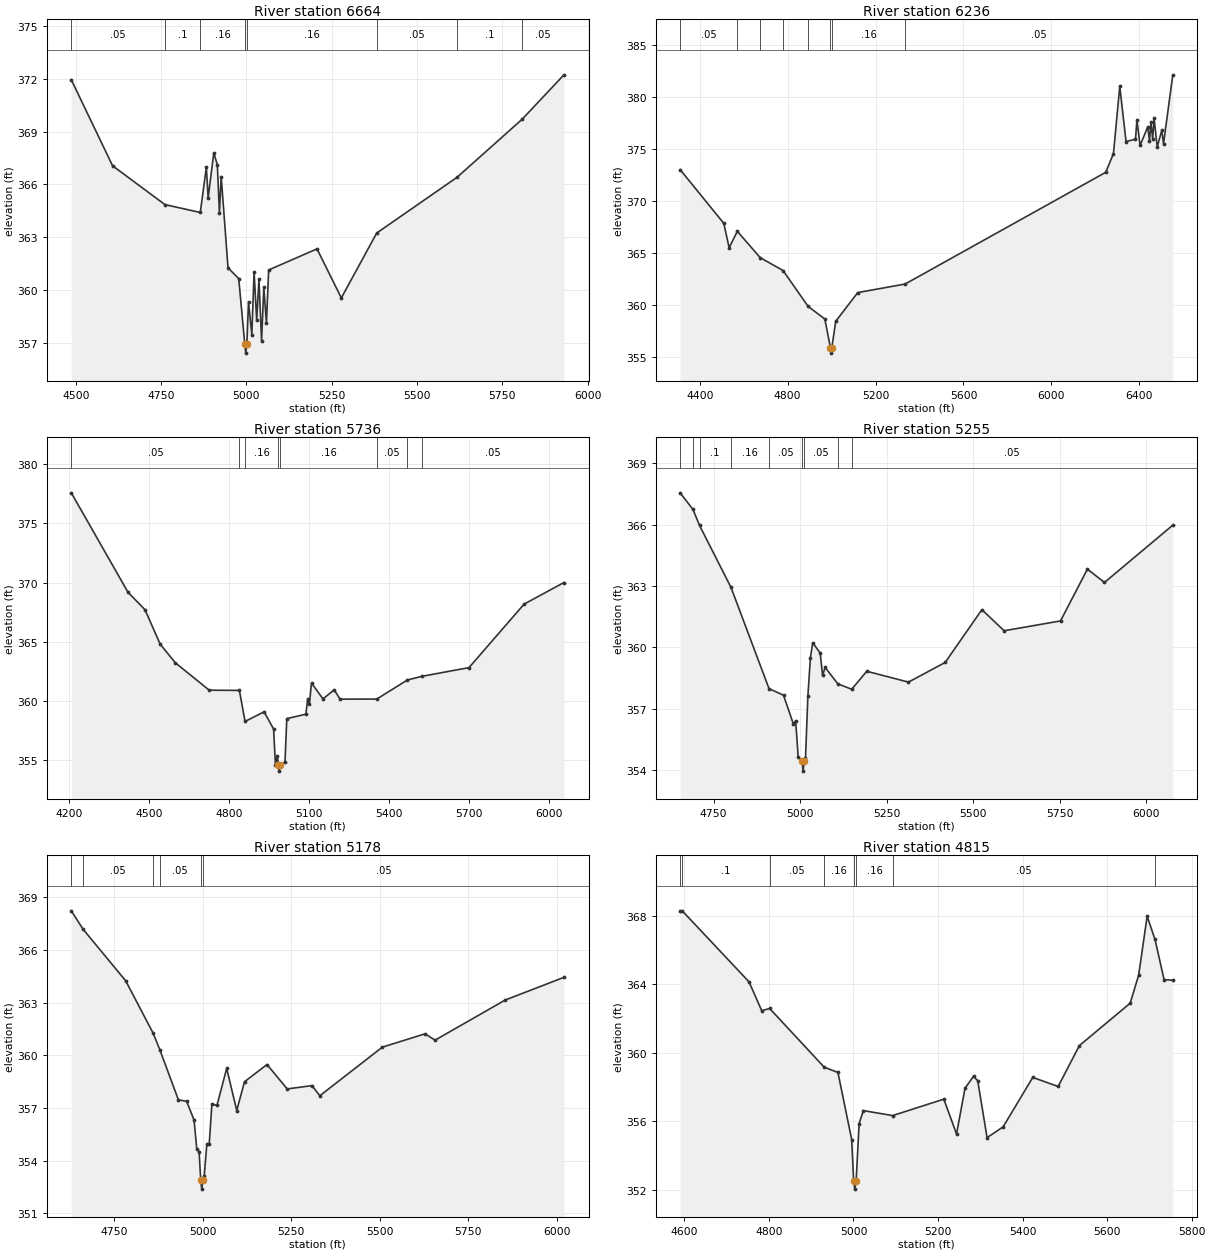
Type RM Length L Ch R = 1 ,6664    ,428,428,428
BEGIN DESCRIPTION:
UNT0488 IN WICK 10.0
END DESCRIPTION:
XS GIS Cut Line= 3
       3538342.1     10284641.61      3538192.11     10284141.64
      3537492.13     10283541.67
#Sta/Elev= 30
  4486.9  371.95  4607.8  367.06  4761.1  364.85  4864.9   364.4  4882.7  366.97
    4888  365.24  4904.5  367.79  4914.9  367.11    4921  364.38  4926.2  366.44
  4946.2  361.25  4977.6  360.64  4995.4   356.9  4998.2   356.4  5001.4   356.9
  5006.3  359.31    5016  357.44  5022.6  361.01  5030.3  358.26  5036.9  360.59
  5044.6  357.09  5051.1  360.16  5058.8  358.11  5065.4  361.13    5207  362.33
  5278.3  359.54    5382  363.23  5617.4   366.4  5808.1   369.7  5930.8  372.23
#Mann= 8 ,-1 , 0
  4486.9     .05       0  4761.1      .1       0  4864.9     .16       0
  4995.4     .07       0  5001.4     .16       0    5382     .05       0
  5617.4      .1       0  5808.1     .05       0
Bank Sta=4995.4,5001.4
XS Rating Curve= 0 ,0
Exp/Cntr=0.3,0.1

Type RM Length L Ch R = 1 ,6236    ,500,500,500
BEGIN DESCRIPTION:
UNT0488 IN WICK 9.0
END DESCRIPTION:
XS GIS Cut Line= 3
      3538692.11     10284641.65      3538492.11     10283991.64
      3537492.12     10282791.66
#Sta/Elev= 30
  4310.7  373.04  4509.5  367.87  4533.7  365.53  4570.9  367.11    4675  364.58
    4779  363.34  4893.2  359.89  4969.2  358.68  4994.9   355.9  4997.7   355.4
  5000.9   355.9  5018.8  358.46    5119  361.22  5334.5  362.04  6247.6  372.78
  6282.7  374.58  6311.4  381.04    6340  375.74    6383  375.96  6389.5  377.81
  6403.8  375.36  6438.9  377.15  6446.7   375.8  6453.2  377.58  6461.1     376
  6467.6  377.98  6481.9  375.22  6502.7  376.82  6510.5  375.51  6552.8  382.15
#Mann= 8 ,-1 , 0
  4310.7     .05       0  4570.9      .1       0    4675     .16       0
    4779      .1       0  4893.2     .16       0  4994.9     .07       0
  5000.9     .16       0  5334.5     .05       0
Bank Sta=4994.9,5000.9
XS Rating Curve= 0 ,0
Exp/Cntr=0.3,0.1

Type RM Length L Ch R = 1 ,5736    ,481,481,481
BEGIN DESCRIPTION:
UNT0488 IN WICK 8.0
END DESCRIPTION:
XS GIS Cut Line= 3
      3539492.11     10284441.64      3538892.11     10283891.64
      3538242.12     10283091.66
#Sta/Elev= 30
    4210  377.59  4422.4  369.17  4485.9   367.7  4542.7  364.79  4599.4  363.21
  4726.4  360.89  4839.4  360.87  4860.6  358.24  4931.8  359.06  4967.5   357.6
  4974.3   354.6  4981.7  355.33  4985.5  354.54  4988.2  354.04  4991.5  354.54
  5010.1  354.79  5016.9  358.48  5088.4  358.86  5095.1  360.17  5101.5  359.71
  5109.4  361.49  5152.5  360.15  5194.2  360.92  5216.5  360.13  5353.9  360.14
  5468.3  361.75  5522.2  362.06  5699.2   362.8  5905.3  368.17  6054.7     370
#Mann= 8 ,-1 , 0
    4210     .05       0  4839.4      .1       0  4860.6     .16       0
  4985.5     .07       0  4991.5     .16       0  5353.9     .05       0
  5468.3     .16       0  5522.2     .05       0
Bank Sta=4985.5,4991.5
XS Rating Curve= 0 ,0
Exp/Cntr=0.3,0.1

Type RM Length L Ch R = 1 ,5255    ,77,77,77
BEGIN DESCRIPTION:
Mapping XS 4541aec3
END DESCRIPTION:
XS GIS Cut Line= 3
      3539426.25     10284163.41      3539308.18     10283902.96
       3538542.4     10283062.87
#Sta/Elev= 30
  4653.5  367.55  4690.5  366.74  4709.4  365.96  4800.3  362.93  4910.2  357.98
    4952  357.66  4980.3  356.26  4987.1  356.41  4994.5  354.62  5005.7  354.45
  5008.5  353.95  5011.7  354.45  5015.5  354.57  5022.4  357.62  5029.7   359.5
  5036.4  360.22    5058  359.72  5064.8  358.63  5072.2  359.02  5108.6  358.22
  5148.8  357.95  5192.5  358.83  5312.8   358.3  5418.8  359.26  5524.9  361.84
  5589.1  360.81  5751.9  361.29  5829.6  363.82  5878.9  363.17  6076.2  365.97
#Mann= 9 ,-1 , 0
  4653.5      .1       0  4690.5     .05       0  4709.4      .1       0
  4800.3     .16       0  4910.2     .05       0  5005.7     .04       0
  5011.7     .05       0  5108.6     .16       0  5148.8     .05       0
Bank Sta=5005.7,5011.7
XS Rating Curve= 0 ,0
Exp/Cntr=0.3,0.1

Type RM Length L Ch R = 1 ,5178    ,363,363,363
BEGIN DESCRIPTION:
UNT0488 IN WICK 7.0
END DESCRIPTION:
XS GIS Cut Line= 3
      3539499.13     10284163.34       3539381.1     10283882.13
      3538667.41     10283062.87
#Sta/Elev= 30
  4628.7  368.24    4662  367.19  4782.4  364.25    4860  361.26  4878.6  360.33
  4931.2  357.47  4954.6  357.38  4975.5  356.31  4983.1  354.67  4989.7  354.52
  4994.3  352.88  4997.1  352.38  5000.3  352.88    5004   353.1  5011.6  354.96
  5018.2  354.94  5025.8  357.23  5040.1  357.15  5067.6  359.26    5096  356.86
  5117.9   358.5  5181.5  359.48  5238.5  358.09  5308.7  358.28  5330.6   357.7
  5507.1  360.47  5627.7  361.23  5656.2  360.87  5854.6  363.16  6020.2  364.45
#Mann= 6 ,-1 , 0
  4628.7      .1       0    4662     .05       0    4860     .16       0
  4878.6     .05       0  4994.3     .04       0  5000.3     .05       0
Bank Sta=4994.3,5000.3
XS Rating Curve= 0 ,0
Exp/Cntr=0.3,0.1

Type RM Length L Ch R = 1 ,4815    ,660,660,660
BEGIN DESCRIPTION:
UNT0488 IN WICK 6.0
END DESCRIPTION:
XS GIS Cut Line= 2
      3539662.35     10284184.23      3539589.43     10283021.02
#Sta/Elev= 30
  4589.9   368.3  4594.8   368.3  4752.8  364.15  4782.9  362.46  4801.7  362.59
  4930.7  359.16  4963.2  358.85  4995.8  354.92  5000.3  352.53  5003.1  352.03
  5006.3  352.53  5013.3  355.86  5023.3  356.62  5092.7  356.33  5213.7  357.29
  5243.8  355.25  5263.8  357.93  5283.9  358.62  5293.9  358.37    5316  355.04
    5354  355.67  5424.1  358.56  5484.2  358.03  5534.3  360.42  5654.6   362.9
  5674.6  364.54  5694.7  367.98  5713.3  366.63  5734.7  364.28  5755.4  364.24
#Mann= 8 ,-1 , 0
  4589.9     .05       0  4594.8      .1       0  4801.7     .05       0
  4930.7     .16       0  5000.3     .07       0  5006.3     .16       0
  5092.7     .05       0  5713.3      .1       0
Bank Sta=5000.3,5006.3
XS Rating Curve= 0 ,0
Exp/Cntr=0.3,0.1

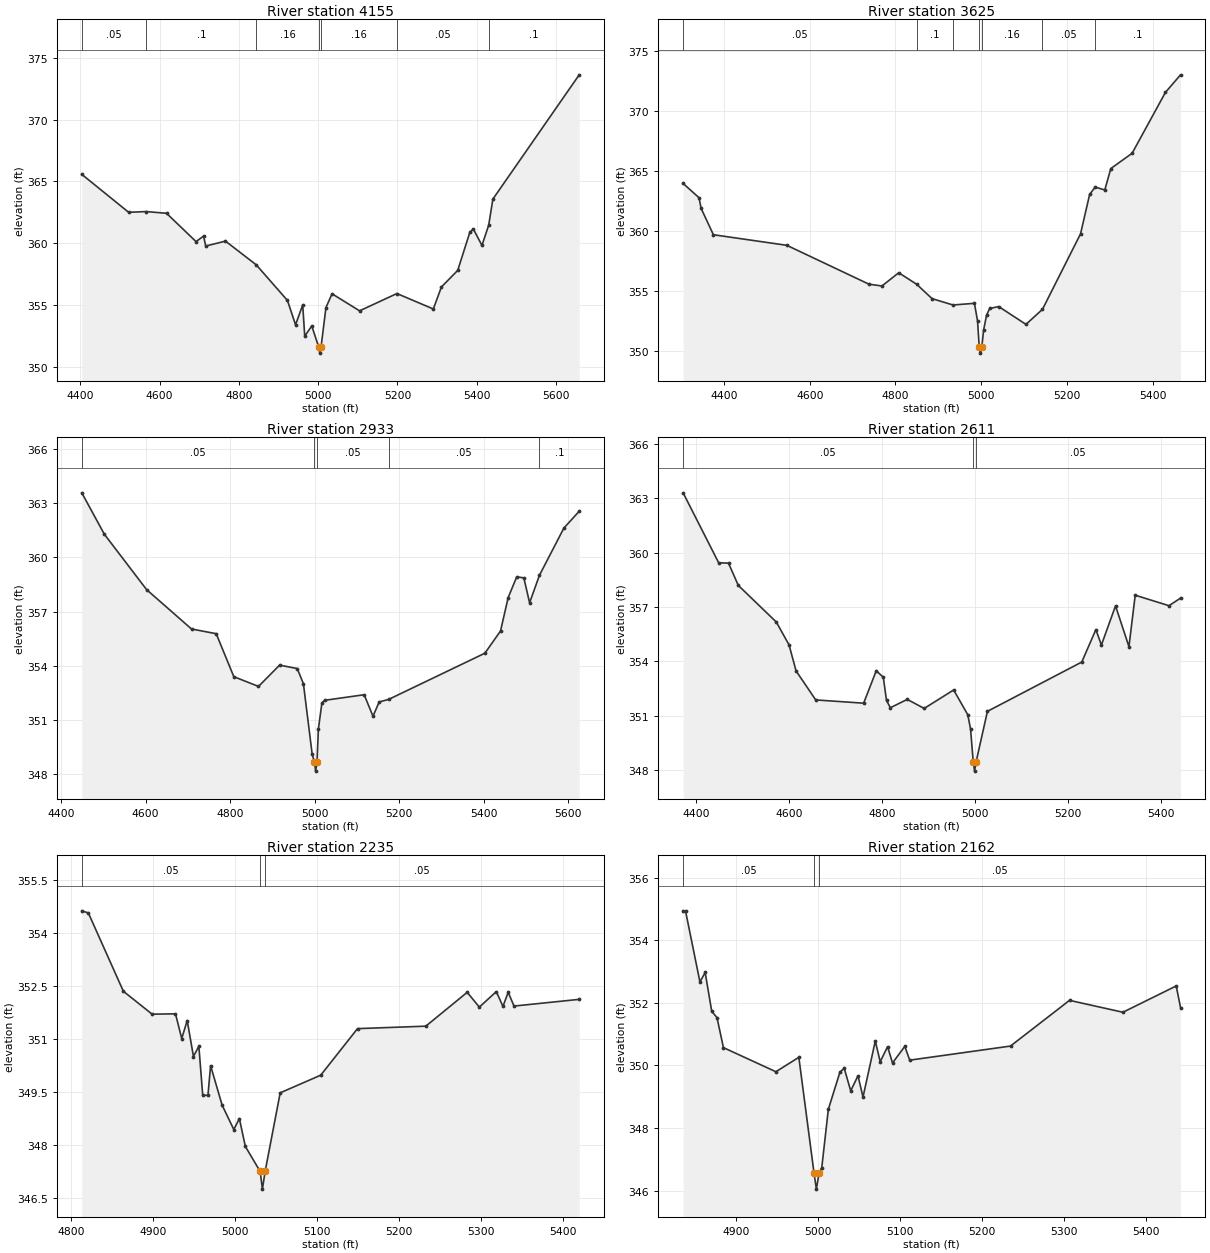
Type RM Length L Ch R = 1 ,4155    ,530,530,530
BEGIN DESCRIPTION:
UNT0488 IN WICK 5.0
END DESCRIPTION:
XS GIS Cut Line= 3
      3539912.33     10284153.01      3540061.65      10283736.3
      3539892.11     10282941.64
#Sta/Elev= 30
  4403.6  365.57  4521.9   362.5  4566.3  362.56  4617.5  362.42  4691.9  360.13
    4711  360.58  4716.3  359.77  4766.2  360.17  4843.9  358.25  4922.6  355.37
    4943   353.4  4961.1  355.01  4966.2  352.48  4983.9  353.31  5001.4  351.61
  5004.1  351.11  5007.4  351.61  5019.7  354.79  5035.1  355.91  5104.6  354.53
  5198.8  355.93  5290.7  354.68  5311.1  356.46  5352.2   357.8  5382.7  360.87
  5391.5  361.16  5413.4  359.82  5430.4  361.46    5441  363.57  5658.8  373.62
#Mann= 7 ,-1 , 0
  4403.6     .05       0  4566.3      .1       0  4843.9     .16       0
  5001.4     .07       0  5007.4     .16       0  5198.8     .05       0
  5430.4      .1       0
Bank Sta=5001.4,5007.4
XS Rating Curve= 0 ,0
Exp/Cntr=0.3,0.1

Type RM Length L Ch R = 1 ,3625    ,692,692,692
BEGIN DESCRIPTION:
UNT0488 IN WICK 4.0
END DESCRIPTION:
XS GIS Cut Line= 3
       3540492.1     10283891.62      3540429.71     10283413.38
      3539942.14     10282941.67
#Sta/Elev= 30
  4304.5  363.96  4341.5  362.78  4346.5  361.89  4375.1   359.7  4546.5  358.82
  4738.1  355.59  4768.4  355.44  4807.6  356.54  4849.6  355.58  4885.3  354.39
  4934.3  353.86  4984.3     354  4991.5  352.53  4995.5  350.36  4998.2  349.86
  5001.5  350.36  5005.7  351.79  5012.6  353.02  5019.8  353.57  5040.9  353.73
  5104.5  352.25    5143   353.5  5231.8  359.77  5253.1  363.05    5266  363.66
  5288.4  363.42  5302.5   365.2  5352.2  366.47  5429.9  371.53  5465.2  372.99
#Mann= 7 ,-1 , 0
  4304.5     .05       0  4849.6      .1       0  4934.3     .16       0
  4995.5     .07       0  5001.5     .16       0    5143     .05       0
    5266      .1       0
Bank Sta=4995.5,5001.5
XS Rating Curve= 0 ,0
Exp/Cntr=0.3,0.1

Type RM Length L Ch R = 1 ,2933    ,322,322,322
BEGIN DESCRIPTION:
UNT0488 IN WICK 3.0
END DESCRIPTION:
XS GIS Cut Line= 3
       3541030.4     10283597.41      3540450.54     10282819.63
      3540246.39     10282785.03
#Sta/Elev= 30
  4448.8  363.58  4502.1  361.29  4602.2  358.22  4708.5  356.04  4766.9  355.78
  4808.6   353.4    4867  352.86    4917  354.04  4958.7  353.85  4973.3  353.01
  4994.1   349.1  4999.5  348.67  5002.2  348.17  5005.5  348.67  5008.7   350.5
  5017.1  351.95  5023.3  352.09  5117.1   352.4    5138  351.21  5152.6     352
  5174.9  352.14  5402.8   354.7  5439.8  355.93  5457.9  357.78  5478.2  358.93
    5495  358.87  5508.6  357.49    5532  359.02  5589.8  361.63    5626  362.56
#Mann= 5 ,-1 , 0
  4448.8     .05       0  4999.5     .03       0  5005.5     .05       0
  5174.9     .05       0    5532      .1       0
Bank Sta=4999.5,5005.5
XS Rating Curve= 0 ,0
Exp/Cntr=0.3,0.1

Type RM Length L Ch R = 1 ,2611    ,376,376,376
BEGIN DESCRIPTION:
UNT0488 IN WICK 2.0
END DESCRIPTION:
XS GIS Cut Line= 2
       3541301.2     10283198.08       3540398.5     10282621.74
#Sta/Elev= 30
  4372.1   363.3  4448.6  359.44  4469.8  359.42  4490.9  358.19  4572.7  356.17
  4600.1  354.91  4615.3  353.47  4657.6  351.87  4760.8  351.69  4787.9  353.48
  4803.1  353.12    4810  351.84  4818.3  351.44  4854.7   351.9  4891.1   351.4
  4954.6  352.42    4985  351.05    4991  350.26  4996.8  348.44  4999.6  347.94
  5002.8  348.44  5027.3  351.24  5230.4  353.96  5260.8  355.75  5272.7   354.9
  5303.1  357.06    5332  354.81  5345.5  357.65  5418.2  357.07  5443.1  357.49
#Mann= 3 ,-1 , 0
  4372.1     .05       0  4996.8     .03       0  5002.8     .05       0
Bank Sta=4996.8,5002.8
XS Rating Curve= 0 ,0
Exp/Cntr=0.3,0.1

Type RM Length L Ch R = 1 ,2235    ,73,73,73
BEGIN DESCRIPTION:
Mapping XS 1cec5c6f
END DESCRIPTION:
XS GIS Cut Line= 5
       3541245.7     10282899.64      3541131.75     10282800.52
      3540995.91     10282673.27      3540872.57     10282585.83
       3540779.7     10282512.48
#Sta/Elev= 30
  4812.9  354.64  4820.9  354.58  4863.6  352.36  4898.7  351.71  4927.2  351.72
  4934.8  351.02  4941.5  351.53  4949.1  350.51  4955.7   350.8  4960.4  349.41
  4966.8  349.41    4970  350.25  4984.1  349.13  4998.3  348.44  5005.1  348.75
  5012.4  347.96  5030.5  347.25  5033.2  346.75  5036.5  347.25  5054.9  349.48
  5104.3  349.98  5149.2   351.3  5232.5  351.37    5283  352.33  5297.8  351.91
  5318.5  352.35  5326.6  351.93    5333  352.33  5340.1  351.94  5419.6  352.13
#Mann= 3 ,-1 , 0
  4812.9     .05       0  5030.5     .03       0  5036.5     .05       0
Bank Sta=5030.5,5036.5
XS Rating Curve= 0 ,0
Exp/Cntr=0.3,0.1

Type RM Length L Ch R = 1 ,2162    ,565,565,565
BEGIN DESCRIPTION:
Mapping XS b3cf4b6a
END DESCRIPTION:
XS GIS Cut Line= 4
      3541270.74      10282871.6      3541147.36     10282718.55
      3540917.07     10282563.97      3540809.06     10282486.27
#Sta/Elev= 30
  4835.3  354.94  4838.2  354.94  4855.8  352.67  4862.2  352.97  4870.2  351.73
  4876.6  351.53  4884.5  350.57  4948.5   349.8  4976.5  350.26  4995.1  346.55
  4997.9  346.05  5001.1  346.55  5004.5  346.74  5012.5   348.6  5026.7  349.79
  5031.9  349.91  5039.8  349.19  5048.7  349.67  5054.8  348.99  5069.8  350.78
  5075.8  350.12  5084.8   350.6  5090.8  350.08  5105.8  350.61  5111.8  350.17
  5234.8  350.62  5306.8  352.08    5372   351.7    5437  352.54  5442.3  351.85
#Mann= 3 ,-1 , 0
  4835.3     .05       0  4995.1     .03       0  5001.1     .05       0
Bank Sta=4995.1,5001.1
XS Rating Curve= 0 ,0
Exp/Cntr=0.3,0.1

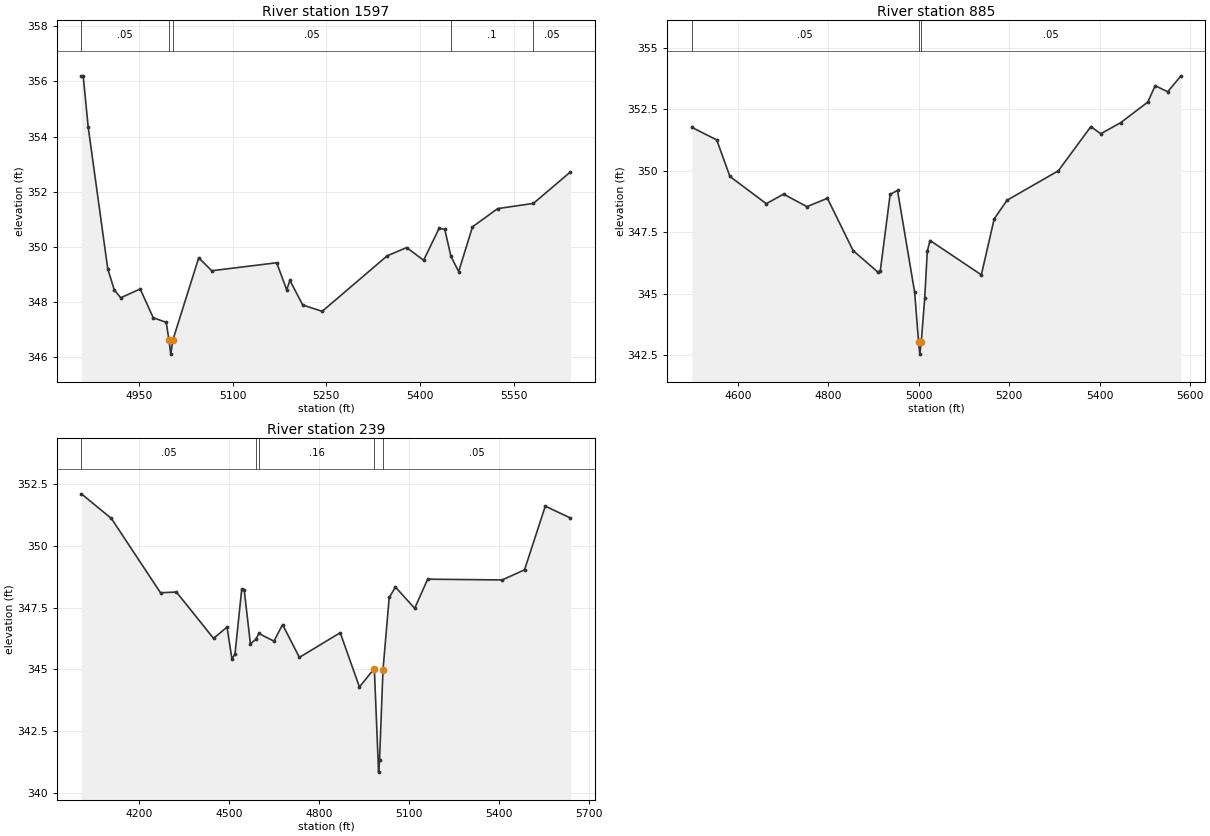
Type RM Length L Ch R = 1 ,1597    ,712,712,712
BEGIN DESCRIPTION:
Mapping XS b4ebb835
END DESCRIPTION:
XS GIS Cut Line= 2
      3541572.66     10282396.37      3540820.07     10282182.84
#Sta/Elev= 30
  4858.2   356.2  4861.1   356.2  4869.2  354.33  4900.4  349.21  4910.8  348.45
  4921.1  348.16  4952.3  348.48  4973.1  347.44  4993.9  347.27  4998.4  346.62
  5001.2  346.12  5004.4  346.62  5045.9  349.61  5066.7  349.14  5170.6  349.43
  5186.6  348.45  5191.8  348.79  5212.2   347.9  5243.4  347.67  5347.3  349.68
  5378.5  349.98  5405.6  349.52  5430.5  350.68  5439.5  350.64  5449.2  349.67
  5461.7  349.11  5483.8  350.73    5524  351.39  5581.3  351.58  5640.5  352.72
#Mann= 5 ,-1 , 0
  4858.2     .05       0  4998.4     .03       0  5004.4     .05       0
  5449.2      .1       0  5581.3     .05       0
Bank Sta=4998.4,5004.4
XS Rating Curve= 0 ,0
Exp/Cntr=0.3,0.1

Type RM Length L Ch R = 1 ,885     ,646,646,646
BEGIN DESCRIPTION:
Mapping XS 4e0caa5b
END DESCRIPTION:
XS GIS Cut Line= 2
      3541786.25     10282102.12      3540833.12      10281591.7
#Sta/Elev= 30
  4498.6  351.77  4553.5  351.26  4582.7  349.77  4663.1  348.66  4701.3  349.05
  4752.9  348.54  4798.2  348.88    4855  346.75  4909.3  345.88    4915  345.91
  4936.9  349.04  4953.2   349.2  4991.1  345.05  4999.7  343.03  5002.5  342.53
  5005.7  343.03  5013.3   344.8    5019  346.72  5025.1  347.16  5138.5  345.76
  5166.9  348.04  5195.3   348.8  5308.7     350  5380.6   351.8  5402.5  351.51
  5446.4  351.96  5506.5   352.8  5522.8  353.47  5550.4  353.22  5579.8  353.87
#Mann= 3 ,-1 , 0
  4498.6     .05       0  4999.7    .035       0  5005.7     .05       0
Bank Sta=4999.7,5005.7
XS Rating Curve= 0 ,0
Exp/Cntr=0.3,0.1

Type RM Length L Ch R = 1 ,239     ,0,0,0
BEGIN DESCRIPTION:
UNT0488 IN WICK 1.0
END DESCRIPTION:
XS GIS Cut Line= 4
      3541825.32     10282115.18      3541730.04     10281600.27
      3541156.04     10281143.78      3540816.04      10281299.5
#Sta/Elev= 30
  4006.4  352.12  4106.6  351.12  4270.3  348.11  4323.3  348.14  4447.3  346.26
  4492.1  346.72  4508.3  345.44  4518.5  345.61  4541.2  348.26  4549.3  348.24
  4570.1  346.04  4588.8  346.23  4597.9  346.46  4648.6  346.15  4677.4  346.82
  4733.5  345.49  4869.6  346.49  4933.7  344.29  4983.4  345.04  4997.5  340.84
  5000.8  341.34  5012.2  344.98    5033  347.92  5053.8  348.34  5117.9  347.48
  5161.2  348.66  5409.8  348.63  5484.3  349.04  5553.4  351.62  5637.4  351.14
#Mann= 5 ,-1 , 0
  4006.4     .05       0  4588.8     .12       0  4597.9     .16       0
  4983.4     .07       0  5012.2     .05       0
Bank Sta=4983.4,5012.2
XS Rating Curve= 0 ,0
Exp/Cntr=0.3,0.1

Chan Stop Cuts=-1
Use User Specified Reach Order=0
Composite Channel Slope=5