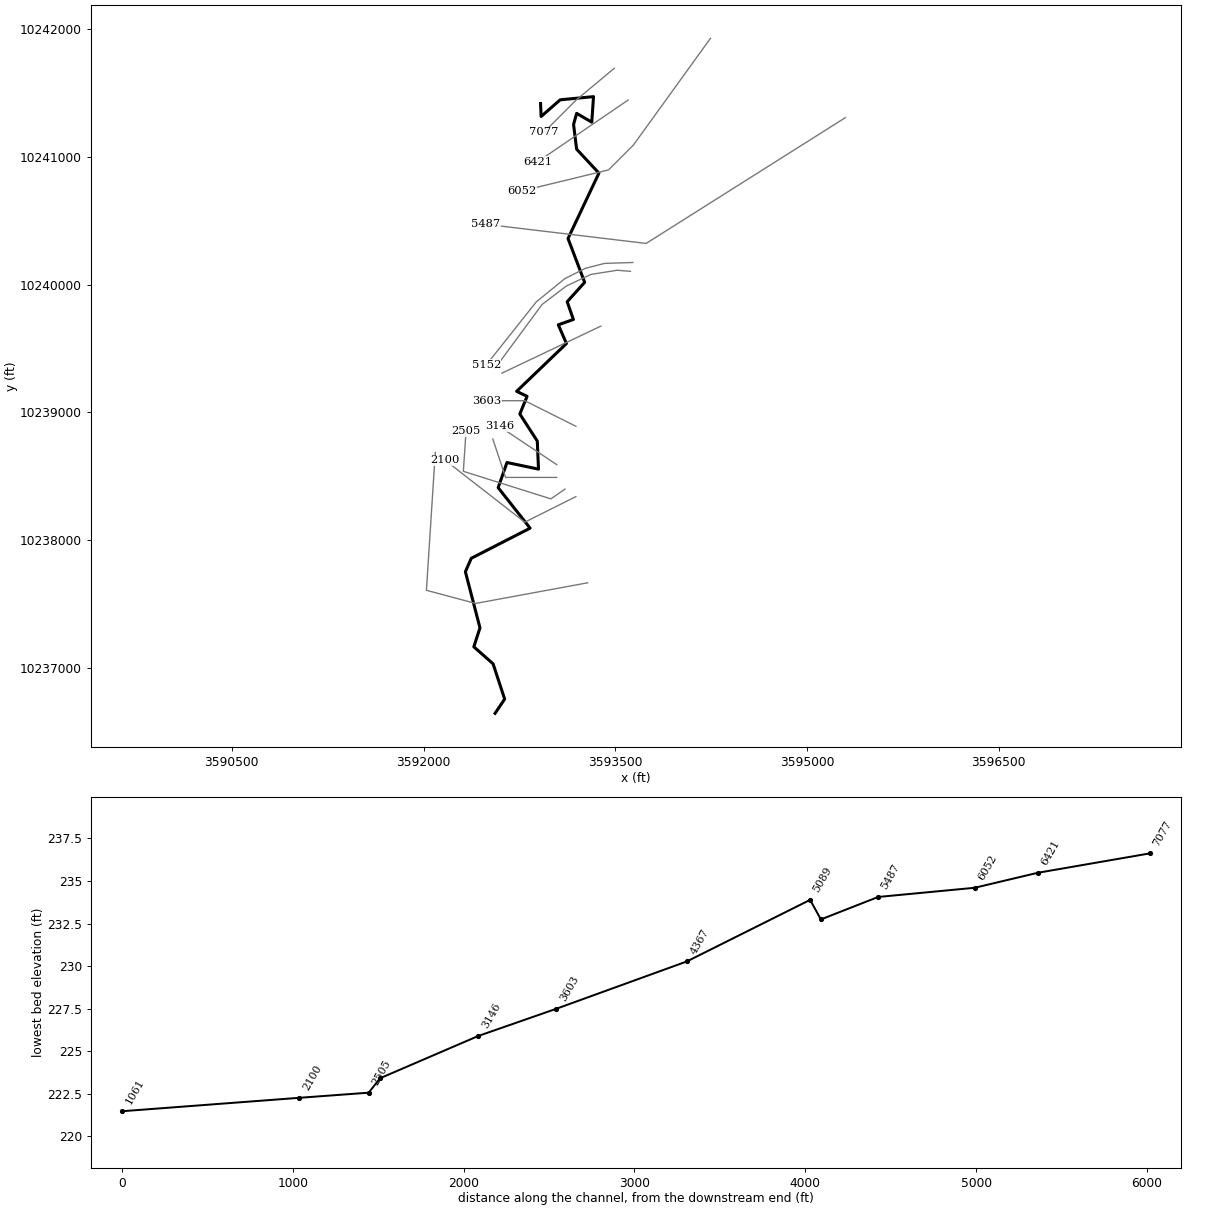
--- WICKSONCREEKTRIB.prj (project) ---

Proj Title=WICKSON CREEK TRIB 7
Current Plan=p01
Default Exp/Contr=0.3,0.1
English Units
Geom File=g01
Flow File=f01
Plan File=p01
Y Axis Title=Elevation
X Axis Title(PF)=Main Channel Distance
X Axis Title(XS)=Station
BEGIN DESCRIPTION:
UNT0506 IN WICK
END DESCRIPTION:
DSS Export Rating Curves= 0
DSS Export Rating Curve Sorted= 0
DSS Export Volume Flow Curves= 0
DXF Filename=UNT0506 IN WICK.
DXF OffsetX= 0
DXF OffsetY= 0
DXF ScaleX= 1
DXF ScaleY= 10

--- WICKSONCREEKTRIB.p01 (plan) ---

Plan Title=Multiple Run
Short Identifier=Multiple
Geom File=g01
Flow File=f01
Subcritical Flow
K Sum by GR= 0
Std Step Tol= 0.01
Critical Tol= 0.01
Num of Std Step Trials= 20
Max Error Tol= 0.3
Flow Tol Ratio= 0.001
Split Flow NTrial= 30
Split Flow Tol= 0.02
Split Flow Ratio= 0.02
Log Output Level= 0
Friction Slope Method= 1
Unsteady Friction Slope Method= 2
Unsteady Bridges Friction Slope Method= 1
Parabolic Critical Depth
Global Vel Dist=  1 , 1 , 1
Global Log Level= 0
CheckData=True
Encroach Param= -1, 0, 0, 0
BEGIN DESCRIPTION:
Multiple Run
END DESCRIPTION:

--- WICKSONCREEKTRIB.f01 (steady flow) ---

Flow Title=Multiple
Program Version=4.10
Number of Profiles= 7
Profile Names=10-year,25-year,50-year,1pct_min,100-year,1pct_plu,500-year
River Rch & RM=UNT0506 IN WICK,Reach-1         ,7077
     500     659     784     683     924    1250    1287
River Rch & RM=UNT0506 IN WICK,Reach-1         ,5089
     669     897    1081     953    1289    1743    1837
River Rch & RM=WICKSONCRTR7,Reach-1         ,7077
     500     659     784     683     924    1250    1287
River Rch & RM=WICKSONCRTR7,Reach-1         ,5089
     669     897    1081     953    1289    1743    1837
Boundary for River Rch & Prof#=WICKSONCRTR7,Reach-1         , 1
Up Type= 0
Dn Type= 3
Dn Slope=0.005
Boundary for River Rch & Prof#=WICKSONCRTR7,Reach-1         , 2
Up Type= 0
Dn Type= 3
Dn Slope=0.005
Boundary for River Rch & Prof#=WICKSONCRTR7,Reach-1         , 3
Up Type= 0
Dn Type= 3
Dn Slope=0.005
Boundary for River Rch & Prof#=WICKSONCRTR7,Reach-1         , 4
Up Type= 0
Dn Type= 3
Dn Slope=0.005
Boundary for River Rch & Prof#=WICKSONCRTR7,Reach-1         , 5
Up Type= 0
Dn Type= 3
Dn Slope=0.005
Boundary for River Rch & Prof#=WICKSONCRTR7,Reach-1         , 6
Up Type= 0
Dn Type= 3
Dn Slope=0.005
Boundary for River Rch & Prof#=WICKSONCRTR7,Reach-1         , 7
Up Type= 0
Dn Type= 3
Dn Slope=0.005
DSS Import GetInterval= 0
DSS Import GetPeak= 0
DSS Import FillOption= 0

--- WICKSONCREEKTRIB.g01 (geometry) ---

Geom Title=Existing Conditions
Program Version=4.10

River Reach=WICKSONCRTR7    ,Reach-1
Reach XY= 30
       3592915.6     10241416.41      3592920.07     10241314.55
      3593069.03     10241445.19      3593329.84     10241469.99
      3593316.13     10241270.36      3593197.89     10241339.11
      3593173.68     10241252.18      3593197.66     10241059.14
      3593372.03     10240871.84      3593130.49     10240360.34
      3593260.48     10240017.65      3593123.91     10239865.72
      3593172.36     10239726.92      3593054.24     10239685.46
      3593118.08     10239539.01      3592728.55     10239164.96
      3592810.17     10239125.84       3592753.4     10238987.55
        3592890.     10238775.96      3592899.47      10238556.5
      3592652.88     10238608.27      3592583.98     10238411.56
      3592833.72     10238094.71      3592373.56     10237859.04
      3592327.55       10237754.       3592441.7      10237315.2
      3592393.53     10237166.76      3592544.13     10237033.95
      3592634.85     10236757.91      3592559.59     10236646.06

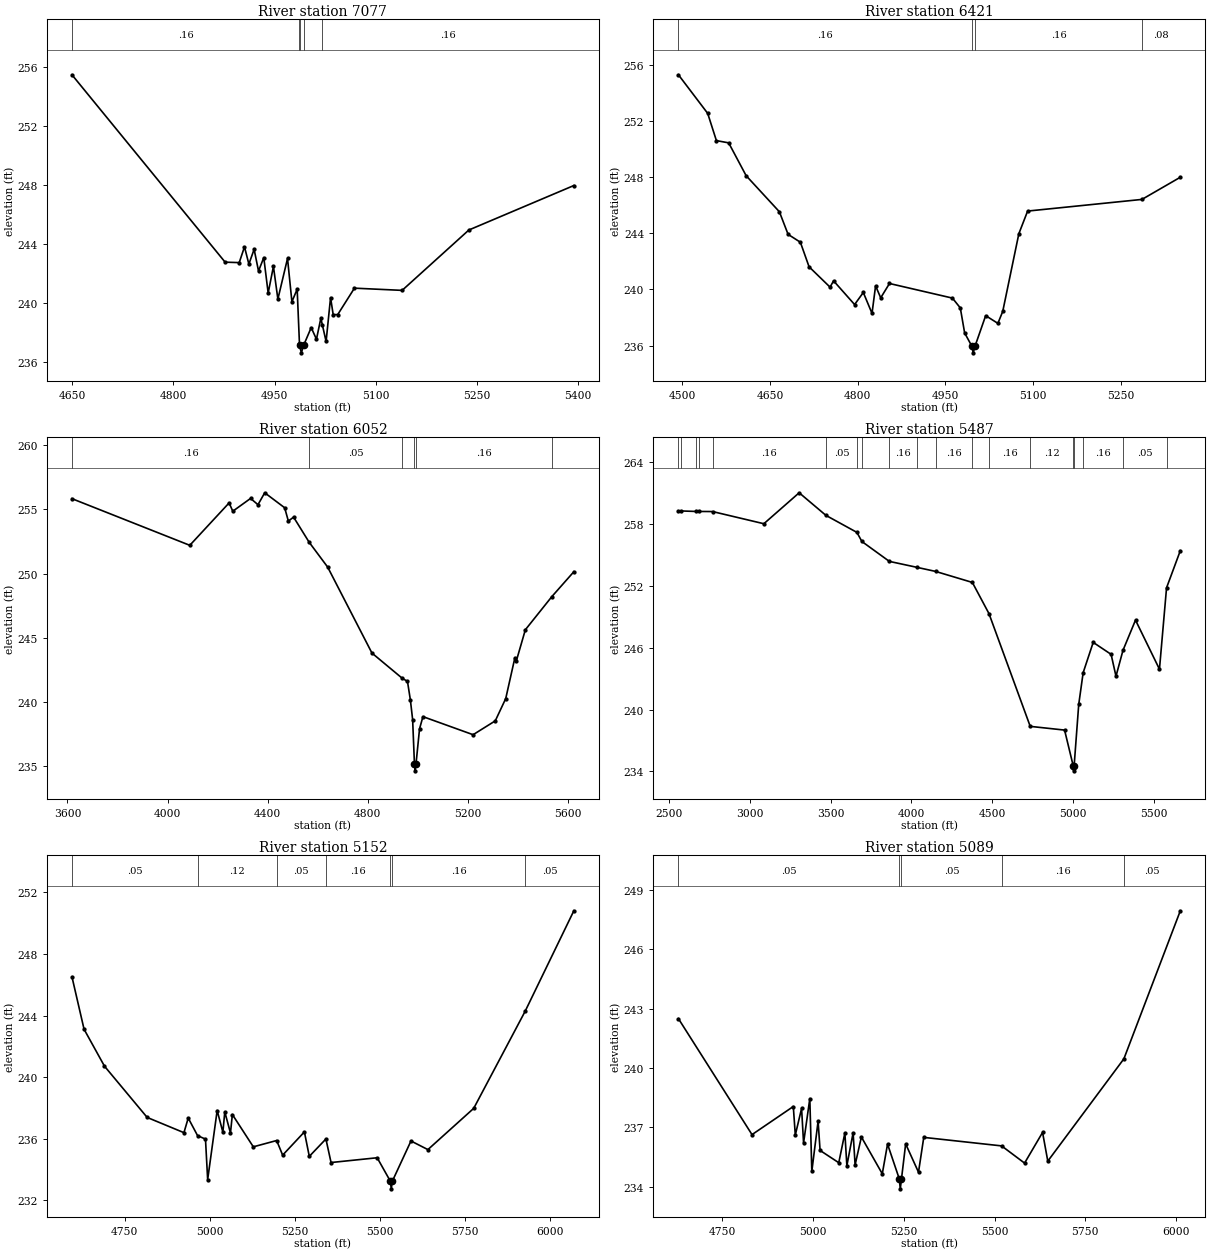
Type RM Length L Ch R = 1 ,7077    ,656,656,656
BEGIN DESCRIPTION:
UNT0506 IN WICK 12.0
END DESCRIPTION:
XS GIS Cut Line= 3
      3593492.11     10241691.64      3593192.11     10241441.64
      3592942.08     10241191.62
#Sta/Elev= 30
  4649.7  255.45  4876.8  242.76  4897.7  242.73  4905.5   243.8    4912  242.63
  4919.8  243.63  4926.3  242.16  4934.1  243.07  4940.6  240.67  4948.4  242.47
    4955  240.26  4969.3  243.01  4975.8  240.08  4983.6  240.93    4987  237.23
  4987.1  237.12  4989.8  236.62  4993.1  237.12  5004.4  238.33  5012.2  237.54
  5018.7  238.96    5021   238.5  5026.5  237.39  5033.1  240.36    5037  239.21
  5043.7  239.21  5068.5     241  5139.2  240.85  5238.2  244.94  5393.8  247.95
#Mann= 5 ,-1 , 0
  4649.7     .16       0    4987     .05       0  4987.1    .035       0
  4993.1     .05       0    5021     .16       0
Bank Sta=4987.1,4993.1
XS Rating Curve= 0 ,0
Exp/Cntr=0.3,0.1

Type RM Length L Ch R = 1 ,6421    ,369,369,369
BEGIN DESCRIPTION:
UNT0506 IN WICK 11.0
END DESCRIPTION:
XS GIS Cut Line= 2
      3593600.61     10241443.44      3592891.01     10240959.53
#Sta/Elev= 30
  4493.4  255.29  4543.5  252.54  4558.4   250.6  4579.4  250.44  4609.3   248.1
  4666.2  245.53  4681.1  243.92  4702.1  243.36    4717  241.61  4752.9  240.16
  4758.9  240.61  4794.9  238.92  4809.8  239.78  4824.7  238.29  4830.8  240.25
  4839.6   239.4  4854.6  240.42  4962.3  239.38  4975.8  238.68  4983.2   236.9
  4995.2  235.98  4997.9  235.48  5001.2  235.98  5019.2  238.13  5040.1  237.58
  5048.4  238.43    5076  243.97    5091  245.58  5286.6  246.41  5352.3  247.99
#Mann= 4 ,-1 , 0
  4493.4     .16       0  4995.2     .07       0  5001.2     .16       0
  5286.6     .08       0
Bank Sta=4995.2,5001.2
XS Rating Curve= 0 ,0
Exp/Cntr=0.3,0.1

Type RM Length L Ch R = 1 ,6052    ,565,565,565
BEGIN DESCRIPTION:
UNT0506 IN WICK 10.0
END DESCRIPTION:
XS GIS Cut Line= 4
      3594244.49     10241926.04      3593642.11     10241091.64
      3593447.53     10240897.06      3592766.14     10240731.52
#Sta/Elev= 30
  3618.2  255.84  4089.1   252.2  4246.2  255.51  4260.9  254.86    4332  255.86
  4361.5  255.37  4388.5   256.3  4468.2  255.13  4482.9  254.09  4503.8   254.4
    4566  252.44    4640   250.5    4817  243.79  4937.6  241.83  4958.9  241.58
  4970.5  240.13  4979.5   238.6  4986.8   235.1  4989.6   234.6  4992.8   235.1
  5007.1  237.88  5020.7  238.83  5221.1  237.42  5309.7   238.5  5351.5  240.24
  5388.1  243.43  5393.3  243.14  5429.9  245.61  5535.9   248.2  5623.7  250.14
#Mann= 6 ,-1 , 0
  3618.2     .16       0    4566     .05       0  4937.6     .16       0
  4986.8     .07       0  4992.8     .16       0  5535.9     .05       0
Bank Sta=4986.8,4992.8
XS Rating Curve= 0 ,0
Exp/Cntr=0.3,0.1

Type RM Length L Ch R = 1 ,5487    ,335,335,335
BEGIN DESCRIPTION:
UNT0506 IN WICK 9.0
END DESCRIPTION:
XS GIS Cut Line= 3
      3595299.16     10241305.38       3593741.3      10240321.8
       3592486.8     10240471.72
#Sta/Elev= 30
  2558.5  259.24  2572.7  259.25  2668.3   259.2  2686.3   259.2  2769.8  259.19
  3087.2  258.01  3305.7  261.01  3471.3  258.82  3663.2  257.17  3693.7  256.29
  3863.8  254.36  4035.6  253.78  4149.5  253.39  4377.4  252.32  4480.2   249.3
  4735.5  238.37  4948.1  238.01  5001.3  234.56  5004.1  234.06  5007.3  234.56
  5035.6  240.49    5063  243.57  5125.2  246.51    5236  245.35  5266.2  243.23
  5309.5  245.74    5387  248.67  5535.2  243.91  5579.1   251.8  5664.3   255.4
#Mann= 19 ,-1 , 0
  2558.5     .16       0  2572.7      .1       0  2668.3     .16       0
  2686.3      .1       0  2769.8     .16       0  3471.3     .05       0
  3663.2     .16       0  3693.7     .05       0  3863.8     .16       0
  4035.6     .05       0  4149.5     .16       0  4377.4     .05       0
  4480.2     .16       0  4735.5     .12       0  5001.3     .07       0
  5007.3     .12       0    5063     .16       0  5309.5     .05       0
  5579.1     .16       0
Bank Sta=5001.3,5007.3
XS Rating Curve= 0 ,0
Exp/Cntr=0.3,0.1

Type RM Length L Ch R = 1 ,5152    ,63,63,63
BEGIN DESCRIPTION:
UNT0506 IN WICK 8.0
END DESCRIPTION:
XS GIS Cut Line= 6
      3593637.64     10240172.64      3593416.45     10240165.73
      3593267.87     10240127.72      3593105.46     10240046.51
      3592882.58      10239865.1      3592490.38     10239370.95
#Sta/Elev= 30
  4595.6  246.52  4631.2  243.11  4691.2  240.71  4816.6  237.38  4924.6  236.39
  4937.2  237.34  4964.6   236.2  4987.9  235.97  4994.3  233.34  5022.2  237.83
    5039  236.42  5044.6  237.74  5061.3  236.37  5066.9  237.57  5128.4  235.47
    5197  235.88  5214.6  234.93  5278.5  236.44  5292.9  234.85  5341.7  235.98
  5356.8  234.45  5492.3  234.76  5530.9  233.24  5533.7  232.74  5536.9  233.24
  5591.6  235.85  5641.3  235.29  5775.9  237.97    5927  244.28  6070.1  250.81
#Mann= 7 ,-1 , 0
  4595.6     .05       0  4964.6     .12       0    5197     .05       0
  5341.7     .16       0  5530.9     .07       0  5536.9     .16       0
    5927     .05       0
Bank Sta=5530.9,5536.9
XS Rating Curve= 0 ,0
Exp/Cntr=0.3,0.1

Type RM Length L Ch R = 1 ,5089    ,722,722,722
BEGIN DESCRIPTION:
UNT0506 IN WICK 7.0
END DESCRIPTION:
XS GIS Cut Line= 6
      3593618.59     10240103.53      3593514.93     10240112.17
      3593309.33     10240079.34      3593115.83     10239987.77
       3592927.5     10239844.37      3592560.01     10239345.84
#Sta/Elev= 30
  4628.6  242.49  4831.4  236.63  4945.2  238.05  4950.7  236.61    4968  237.95
  4973.5  236.21  4990.7  238.45  4996.2  234.77  5013.5  237.31    5019  235.83
  5070.5  235.21  5087.3  236.71  5092.8  235.06    5110  236.72  5115.5   235.1
  5132.8  236.51  5190.4  234.65  5204.9  236.15  5237.3  234.39    5240  233.89
  5243.3  234.39  5254.8  236.16  5290.2  234.73  5304.7  236.49  5519.2  236.06
  5582.5  235.19  5632.1  236.74  5646.5  235.29  5856.2  240.46  6011.7  247.94
#Mann= 5 ,-1 , 0
  4628.6     .05       0  5237.3     .04       0  5243.3     .05       0
  5519.2     .16       0  5856.2     .05       0
Bank Sta=5237.3,5243.3
XS Rating Curve= 0 ,0
Exp/Cntr=0.3,0.1

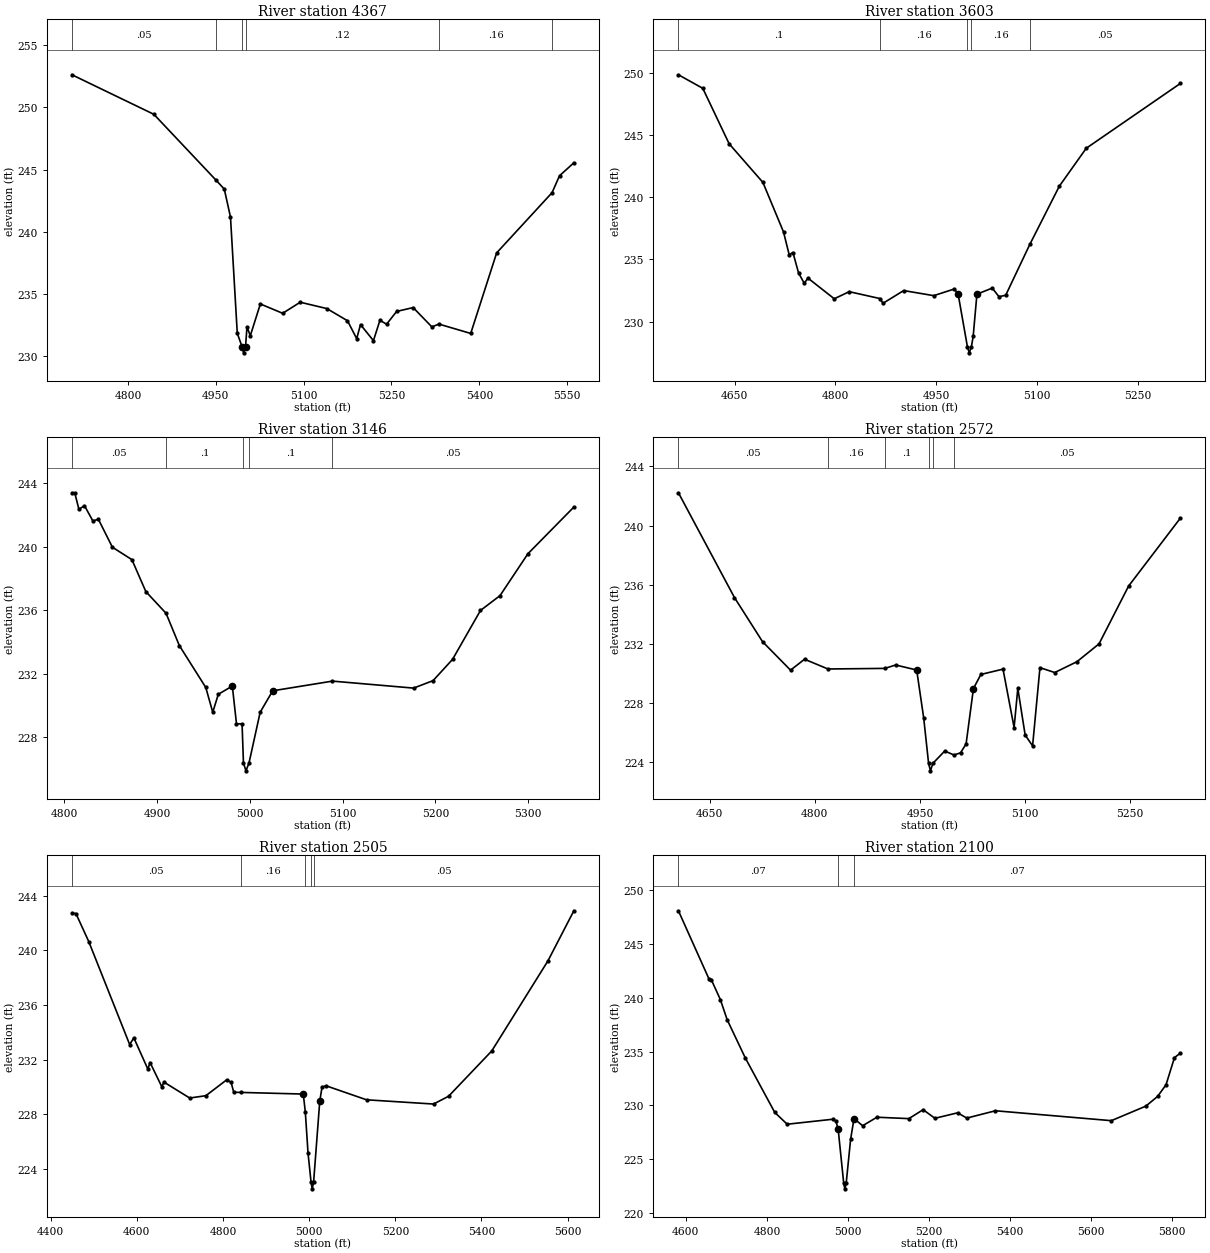
Type RM Length L Ch R = 1 ,4367    ,764,764,764
BEGIN DESCRIPTION:
UNT0506 IN WICK 6.0
END DESCRIPTION:
XS GIS Cut Line= 2
      3593387.04     10239675.03      3592613.07     10239307.04
#Sta/Elev= 30
  4704.4  252.63  4844.3  249.45  4950.1  244.17  4964.5  243.44  4975.1  241.19
  4986.7  231.84  4994.8  230.77  4997.5  230.27  5000.8  230.77  5003.3  232.37
  5008.9  231.64  5026.1   234.2  5064.2  233.45  5094.2  234.34  5139.6  233.83
  5174.9  232.85  5190.6  231.41  5197.1  232.54  5219.2  231.25  5230.3  232.89
  5241.6  232.57  5258.8   233.6    5287  233.91  5318.9  232.36  5331.1  232.58
  5385.3  231.83  5429.6  238.31  5524.2  243.15  5536.9  244.51  5561.4  245.55
#Mann= 6 ,-1 , 0
  4704.4     .05       0  4950.1     .12       0  4994.8     .07       0
  5000.8     .12       0  5331.1     .16       0  5524.2     .05       0
Bank Sta=4994.8,5000.8
XS Rating Curve= 0 ,0
Exp/Cntr=0.3,0.1

Type RM Length L Ch R = 1 ,3603    ,457,457,457
BEGIN DESCRIPTION:
UNT0506 IN WICK 5.0
END DESCRIPTION:
XS GIS Cut Line= 3
       3593192.1     10238891.65      3592792.11     10239091.64
      3592492.11     10239091.64
#Sta/Elev= 30
  4566.3  249.86  4602.6  248.77  4641.8  244.31  4692.1   241.2  4722.8  237.21
  4731.2  235.38  4736.8  235.56  4745.2  233.91  4753.6  233.09  4759.2   233.5
  4798.3  231.84  4820.6  232.41    4866  231.86    4871  231.48  4901.7   232.5
  4946.4  232.09  4977.2  232.63  4982.8  232.19  4996.5  227.99  4999.3  227.49
  5002.5  227.99  5005.1  228.81  5010.7  232.21  5033.5   232.7  5043.5  232.01
  5053.5  232.12  5089.5  236.22  5133.5  240.91  5173.5  243.95  5313.5  249.16
#Mann= 5 ,-1 , 0
  4566.3      .1       0    4866     .16       0  4996.5     .07       0
  5002.5     .16       0  5089.5     .05       0
Bank Sta=4982.8,5010.7
XS Rating Curve= 0 ,0
Exp/Cntr=0.3,0.1

Type RM Length L Ch R = 1 ,3146    ,574,574,574
BEGIN DESCRIPTION:
UNT0506 IN WICK 4.0
END DESCRIPTION:
XS GIS Cut Line= 3
       3593042.1     10238591.64      3592892.11     10238691.64
      3592592.13     10238891.62
#Sta/Elev= 30
  4808.3   243.4  4811.3   243.4  4815.8  242.36  4821.8  242.59  4830.8  241.63
  4836.8  241.73  4851.9  239.97  4872.9  239.19  4887.9  237.18  4909.7  235.81
    4924  233.78  4952.5  231.14    4960  229.58    4966  230.71  4981.1  231.23
  4985.6  228.85  4991.6  228.85  4993.1  226.39  4995.8  225.89  4999.1  226.39
  5011.1  229.58  5024.6  230.93    5089  231.54  5176.4   231.1  5197.4  231.57
  5218.4  232.91  5248.5  235.99  5269.5  236.92  5299.6  239.56  5349.1   242.5
#Mann= 5 ,-1 , 0
  4808.3     .05       0  4909.7      .1       0  4993.1     .07       0
  4999.1      .1       0    5089     .05       0
Bank Sta=4981.1,5024.6
XS Rating Curve= 0 ,0
Exp/Cntr=0.3,0.1

Type RM Length L Ch R = 1 ,2572    ,67,67,67
BEGIN DESCRIPTION:
UNT0506 IN WICK 3.0
END DESCRIPTION:
XS GIS Cut Line= 3
      3593042.06     10238491.64      3592642.11     10238491.64
       3592542.1     10238791.66
#Sta/Elev= 30
  4605.3  242.22  4685.3  235.13  4725.3  232.15  4765.3  230.22  4785.3  230.96
  4818.7   230.3  4899.8  230.34  4915.3  230.57  4945.3  230.23  4955.3  226.99
  4962.3  223.91    4965  223.41  4968.3  223.91  4985.3  224.75  4998.6  224.48
  5007.9  224.63  5015.8  225.23  5026.3  228.98  5036.9  229.93  5068.5  230.29
  5084.3  226.34  5089.6  228.99  5100.1  225.83  5110.7   225.1  5121.2  230.39
  5142.3  230.06  5173.9  230.79  5205.5     232  5247.7  235.91  5321.5   240.5
#Mann= 6 ,-1 , 0
  4605.3     .05       0  4818.7     .16       0  4899.8      .1       0
  4962.3     .03       0  4968.3      .1       0  4998.6     .05       0
Bank Sta=4945.3,5026.3
XS Rating Curve= 0 ,0
Exp/Cntr=0.3,0.1

Type RM Length L Ch R = 1 ,2505    ,405,405,405
BEGIN DESCRIPTION:
Mapping XS b0f88224
END DESCRIPTION:
XS GIS Cut Line= 4
      3593106.82     10238400.37      3592995.74       10238324.
      3592311.71     10238539.28      3592332.54     10238851.77
#Sta/Elev= 30
  4449.3  242.71  4458.5  242.69  4488.3  240.64  4583.3  233.11    4593   233.6
  4625.4  231.32  4630.7  231.79  4657.8  230.03    4663  230.36  4722.6   229.2
  4760.2  229.37  4808.1  230.52  4818.6  230.36  4824.9  229.62  4840.6  229.61
  4986.3  229.49    4991  228.19  4997.3  225.19  5004.3  223.06    5007  222.56
  5010.3  223.06  5024.5  228.95  5029.7  229.98  5038.7   230.1  5133.1  229.07
  5288.7  228.76  5323.6  229.33  5423.8  232.64  5554.1  239.22  5614.4  242.89
#Mann= 5 ,-1 , 0
  4449.3     .05       0  4840.6     .16       0    4991     .05       0
  5004.3     .03       0  5010.3     .05       0
Bank Sta=4986.3,5024.5
XS Rating Curve= 0 ,0
Exp/Cntr=0.3,0.1

Type RM Length L Ch R = 1 ,2100    ,1039,1039,1039
BEGIN DESCRIPTION:
UNT0506 IN WICK 2.0
END DESCRIPTION:
XS GIS Cut Line= 3
      3593192.08     10238341.63      3592792.11     10238141.64
3592167.7929076910238627.2184191
#Sta/Elev= 30
  4581.7  248.08  4657.1  241.75  4662.7  241.69  4685.1  239.84  4701.9  237.97
  4746.6  234.42  4819.3  229.36    4850  228.26  4961.8  228.72  4970.2  228.56
  4975.8  227.79  4989.5  222.76  4992.3  222.26  4995.5  222.76  5006.5  226.87
  5014.9  228.78  5036.1  228.12  5071.4  228.91  5150.1  228.78  5185.4  229.61
  5214.4  228.81  5270.5  229.32  5293.1  228.83  5363.7  229.51  5649.6  228.59
  5734.7  229.94  5763.7  230.84  5784.5  231.92  5805.3  234.44  5819.8  234.86
#Mann= 3 , 0 , 0
  4581.7     .07       0  4975.8     .05       0  5014.9     .07       0
#XS Ineff= 2 , 0
                         5820.37          234.76
Permanent Ineff=
       F       F
Bank Sta=4975.8,5014.9
XS Rating Curve= 0 ,0
Exp/Cntr=0.3,0.1

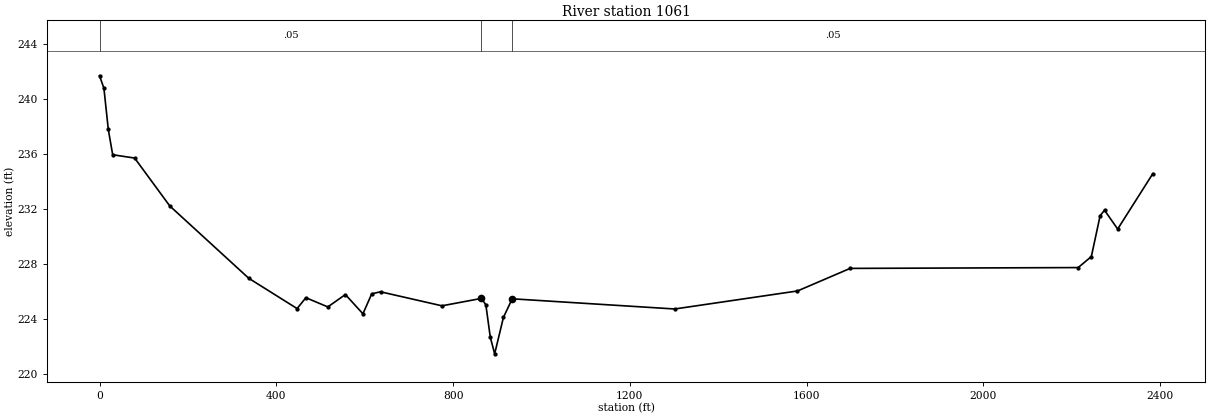
Type RM Length L Ch R = 1 ,1061    ,0,0,0
BEGIN DESCRIPTION:
UNT0506 IN WICK 1.0
END DESCRIPTION:
XS GIS Cut Line= 4
      3593283.68    10237667.284     3592407.378     10237505.96
     3592022.829     10237608.69     3592092.272    10238687.249
#Sta/Elev= 30
       0  241.68    9.93  240.78   19.87  237.78    29.8  235.94   79.47   235.7
  158.95  232.22  337.76  226.96  447.04  224.76  466.91  225.55  516.58  224.88
  556.31  225.78  596.05  224.38  615.92  225.83  635.79  225.98  774.87  224.96
  864.27   225.5  874.21  225.03  884.14  222.69  894.08  221.47  913.95  224.12
  933.82  225.47 1301.46  224.73 1579.33  226.04 1698.42  227.68 2214.46  227.74
 2244.23  228.54 2264.08  231.51 2274.01  231.91 2303.78  230.54 2383.17  234.56
#Mann= 3 , 0 , 0
       0     .05       0  864.27     .03       0  933.82     .05       0
Bank Sta=864.27,933.82
XS Rating Curve= 0 ,0
Exp/Cntr=0.3,0.1

Chan Stop Cuts=-1
Use User Specified Reach Order=0
Composite Channel Slope=5