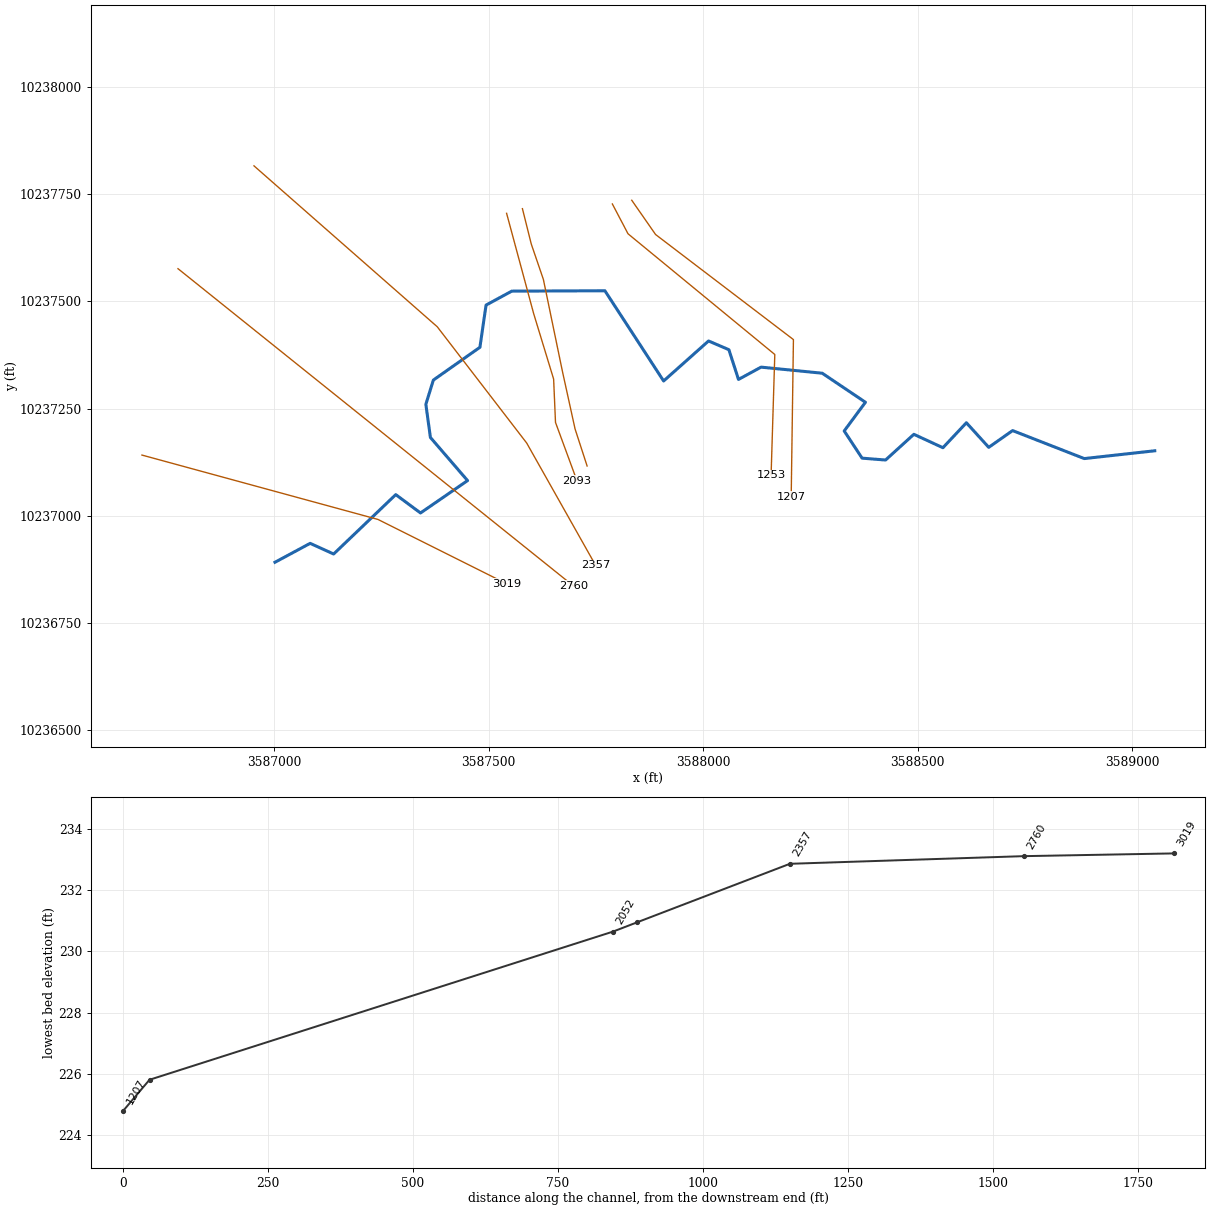
--- WICKSONCREEKTRIB.prj (project) ---

Proj Title=WICKSON CREEK TRIB 9
Current Plan=p01
Default Exp/Contr=0.3,0.1
English Units
Geom File=g01
Flow File=f01
Plan File=p01
Y Axis Title=Elevation
X Axis Title(PF)=Main Channel Distance
X Axis Title(XS)=Station
BEGIN DESCRIPTION:
UNT05259 IN WICK
END DESCRIPTION:
DSS Export Rating Curves= 0
DSS Export Rating Curve Sorted= 0
DSS Export Volume Flow Curves= 0
DXF OffsetX= 0
DXF OffsetY= 0
DXF ScaleX= 1
DXF ScaleY= 10

--- WICKSONCREEKTRIB.p01 (plan) ---

Plan Title=Multiple Run
Short Identifier=Multiple
Geom File=g01
Flow File=f01
Subcritical Flow
K Sum by GR= 0
Std Step Tol= 0.01
Critical Tol= 0.01
Num of Std Step Trials= 20
Max Error Tol= 0.3
Flow Tol Ratio= 0.001
Split Flow NTrial= 30
Split Flow Tol= 0.02
Split Flow Ratio= 0.02
Log Output Level= 0
Friction Slope Method= 1
Unsteady Friction Slope Method= 2
Unsteady Bridges Friction Slope Method= 1
Parabolic Critical Depth
Global Vel Dist=  1 , 1 , 1
Global Log Level= 0
CheckData=True
Encroach Param= -1, 0, 0, 0
BEGIN DESCRIPTION:
Multiple Run
END DESCRIPTION:

--- WICKSONCREEKTRIB.f01 (steady flow) ---

Flow Title=Multiple
Program Version=4.10
Number of Profiles= 7
Profile Names=10-year,25-year,50-year,1pct_min,100-year,1pct_plu,500-year
River Rch & RM=UNT05259 IN WICK,Reach-1         ,3019
     320     415     490     426     576     778     793
River Rch & RM=WICKSONCRTR9,Reach-1         ,3019
     320     415     490     426     576     778     793
Boundary for River Rch & Prof#=WICKSONCRTR9,Reach-1         , 1
Up Type= 0
Dn Type= 3
Dn Slope=0.005
Boundary for River Rch & Prof#=WICKSONCRTR9,Reach-1         , 2
Up Type= 0
Dn Type= 3
Dn Slope=0.005
Boundary for River Rch & Prof#=WICKSONCRTR9,Reach-1         , 3
Up Type= 0
Dn Type= 3
Dn Slope=0.005
Boundary for River Rch & Prof#=WICKSONCRTR9,Reach-1         , 4
Up Type= 0
Dn Type= 3
Dn Slope=0.005
Boundary for River Rch & Prof#=WICKSONCRTR9,Reach-1         , 5
Up Type= 0
Dn Type= 3
Dn Slope=0.005
Boundary for River Rch & Prof#=WICKSONCRTR9,Reach-1         , 6
Up Type= 0
Dn Type= 3
Dn Slope=0.005
Boundary for River Rch & Prof#=WICKSONCRTR9,Reach-1         , 7
Up Type= 0
Dn Type= 3
Dn Slope=0.005
DSS Import GetInterval= 0
DSS Import GetPeak= 0
DSS Import FillOption= 0

--- WICKSONCREEKTRIB.g01 (geometry) ---

Geom Title=Existing Conditions
Program Version=4.10

River Reach=WICKSONCRTR9    ,Reach-1
Reach XY= 30
      3587002.04     10236891.83      3587084.02     10236935.91
      3587138.82     10236911.11      3587283.53     10237049.49
      3587341.18      10237006.7      3587450.83     10237082.17
      3587364.28     10237182.62      3587353.66     10237260.03
      3587371.17     10237316.37      3587479.61     10237392.73
      3587493.93     10237491.06      3587553.83     10237523.61
      3587770.84     10237524.48      3587907.65     10237314.24
      3588012.33     10237407.47      3588059.73     10237387.15
      3588082.13     10237317.88      3588134.73     10237346.53
      3588277.22     10237332.36      3588377.92     10237264.65
      3588328.44     10237197.81       3588370.1     10237134.44
      3588424.79      10237130.1      3588490.76       10237190.
      3588558.47     10237158.75      3588613.16     10237216.91
      3588665.24     10237159.61       3588720.8     10237198.68
      3588887.87     10237133.44      3589052.11     10237151.64

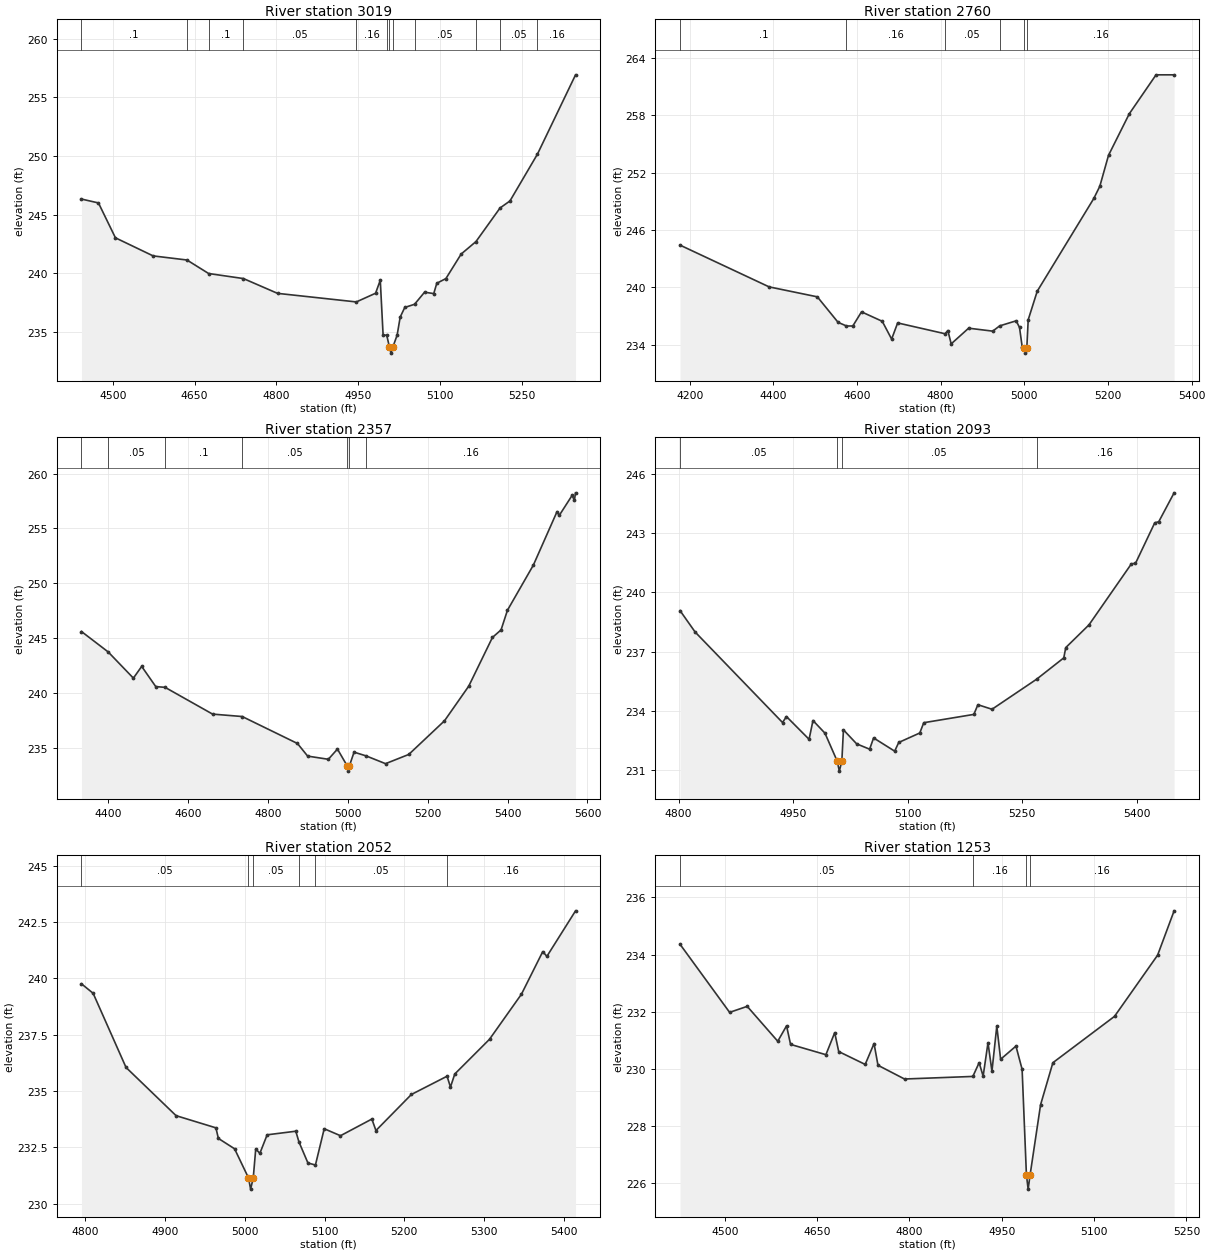
Type RM Length L Ch R = 1 ,3019    ,259,259,259
BEGIN DESCRIPTION:
UNT05259 IN WICK 6.0
END DESCRIPTION:
XS GIS Cut Line= 3
      3586692.09     10237141.65      3587242.11     10236991.64
      3587542.09     10236841.65
#Sta/Elev= 30
  4442.7  246.33  4473.8     246  4504.9  243.03    4574  241.49    4636  241.14
  4675.7  239.99  4739.5  239.56    4802   238.3  4946.4  237.57  4981.7  238.31
  4990.3  239.42  4995.5  234.74  5002.1  234.74  5007.2  233.71    5010  233.21
  5013.2  233.71  5021.2  234.74  5026.8  236.28  5035.2   237.1  5053.1  237.37
  5071.5   238.4  5088.3  238.28  5093.9  239.16  5110.6  239.56  5138.6  241.65
  5165.7  242.71  5209.8  245.57    5228  246.17  5278.3  250.15  5348.2  256.91
#Mann= 12 ,-1 , 0
  4442.7      .1       0    4636     .05       0  4675.7      .1       0
  4739.5     .05       0  4946.4     .16       0  5002.1      .1       0
  5007.2     .07       0  5013.2      .1       0  5053.1     .05       0
  5165.7     .16       0  5209.8     .05       0  5278.3     .16       0
Bank Sta=5007.2,5013.2
XS Rating Curve= 0 ,0
Exp/Cntr=0.3,0.1

Type RM Length L Ch R = 1 ,2760    ,403,403,403
BEGIN DESCRIPTION:
UNT05259 IN WICK 5.0
END DESCRIPTION:
XS GIS Cut Line= 2
      3586776.07     10237575.97      3587697.34     10236836.88
#Sta/Elev= 30
    4177  244.42    4390  240.05  4505.2  239.01  4554.8  236.34  4574.9  235.96
    4590  235.96  4610.8  237.44  4660.4  236.45  4682.8  234.59  4697.2  236.28
  4810.3  235.15  4817.2  235.48  4825.2  234.09  4866.9  235.73  4924.5  235.42
    4941  235.97  4980.5   236.5  4988.5  235.81  4994.9  233.79  4999.9  233.62
  5002.6  233.12  5005.9  233.62  5009.3  236.61  5030.9   239.6  5166.1   249.3
  5180.5  250.58  5201.3  253.82  5250.9  258.16  5314.9  262.24  5358.1  262.24
#Mann= 6 ,-1 , 0
    4177      .1       0  4574.9     .16       0  4810.3     .05       0
    4941     .16       0  4999.9     .07       0  5005.9     .16       0
Bank Sta=4999.9,5005.9
XS Rating Curve= 0 ,0
Exp/Cntr=0.3,0.1

Type RM Length L Ch R = 1 ,2357    ,264,264,264
BEGIN DESCRIPTION:
UNT05259 IN WICK 4.0
END DESCRIPTION:
XS GIS Cut Line= 4
      3586953.18     10237815.53      3587380.26     10237440.54
      3587588.59      10237169.7      3587749.09     10236884.95
#Sta/Elev= 30
  4333.2   245.6    4400  243.74  4463.1  241.35  4483.9  242.42  4519.1  240.58
  4542.5  240.51  4661.4  238.07  4735.5  237.85  4873.9  235.39  4899.4  234.24
  4951.2  233.95    4974  234.88  4998.1  233.37  5000.8  232.87  5004.1  233.37
  5015.6   234.6  5045.7  234.26  5094.4  233.55  5152.5  234.39    5242  237.46
  5302.7  240.62    5362  245.06  5383.6  245.75  5399.6  247.54  5464.5  251.66
  5523.8  256.54  5529.5   256.2  5561.4  258.01  5567.1  257.57  5570.1  258.25
#Mann= 7 ,-1 , 0
  4333.2      .1       0    4400     .05       0  4542.5      .1       0
  4735.5     .05       0  4998.1    .035       0  5004.1     .05       0
  5045.7     .16       0
Bank Sta=4998.1,5004.1
XS Rating Curve= 0 ,0
Exp/Cntr=0.3,0.1

Type RM Length L Ch R = 1 ,2093    ,41,41,41
BEGIN DESCRIPTION:
Mapping XS 90809ebe
END DESCRIPTION:
XS GIS Cut Line= 5
       3587541.8     10237704.94      3587604.73     10237471.65
      3587651.39     10237318.65      3587655.73     10237217.74
      3587705.64     10237082.12
#Sta/Elev= 30
    4802  239.07  4821.7  237.99  4936.2  233.41  4941.4  233.71    4971  232.56
  4976.1  233.51  4991.8  232.87  5007.9  231.45  5010.6  230.95  5013.9  231.45
    5016  233.04  5033.3  232.33  5050.3  232.06  5055.5  232.63  5083.1  231.96
  5088.4   232.4    5116  232.88  5121.2   233.4  5186.8  233.82  5192.1  234.31
  5210.6  234.08    5269   235.6  5304.6  236.68  5307.2   237.2  5337.6  238.35
  5393.2  241.44  5398.5  241.46  5423.7  243.51    5429  243.57  5449.1  245.03
#Mann= 4 ,-1 , 0
    4802     .05       0  5007.9    .035       0  5013.9     .05       0
    5269     .16       0
Bank Sta=5007.9,5013.9
XS Rating Curve= 0 ,0
Exp/Cntr=0.3,0.1

Type RM Length L Ch R = 1 ,2052    ,799,799,799
BEGIN DESCRIPTION:
UNT05259 IN WICK 3.0
END DESCRIPTION:
XS GIS Cut Line= 6
       3587578.7     10237715.77      3587599.31     10237633.32
      3587627.52     10237550.86      3587672.01     10237336.01
      3587701.31     10237202.55      3587729.38     10237116.18
#Sta/Elev= 30
  4795.5  239.76  4810.1  239.34  4851.3  236.05    4914  233.91  4963.9  233.37
    4967   232.9  4987.3  232.44  5004.7  231.15  5007.4  230.65  5010.7  231.15
  5013.8  232.43    5019  232.24  5028.1  233.06    5064  233.22  5067.9  232.75
  5079.2  231.81  5088.6  231.72  5099.6  233.33    5120  233.02  5159.3  233.76
  5164.4  233.25  5208.8  234.85  5253.5  235.66  5257.8  235.18  5263.2  235.76
  5306.7   237.3  5346.7   239.3  5373.4  241.19  5378.6  240.98  5414.5     243
#Mann= 6 ,-1 , 0
  4795.5     .05       0  5004.7    .035       0  5010.7     .05       0
  5067.9     .16       0  5088.6     .05       0  5253.5     .16       0
Bank Sta=5004.7,5010.7
XS Rating Curve= 0 ,0
Exp/Cntr=0.3,0.1

Type RM Length L Ch R = 1 ,1253    ,46,46,46
BEGIN DESCRIPTION:
Mapping XS b140fd96
END DESCRIPTION:
XS GIS Cut Line= 4
      3587788.26      10237726.7      3587824.71     10237657.26
      3588166.73     10237376.01       3588158.1     10237094.87
#Sta/Elev= 30
  4427.5  234.36    4508  231.98  4536.6  232.19  4586.2  230.97  4600.5  231.51
    4607  230.86  4664.4   230.5  4678.7  231.27  4685.2  230.61  4728.2  230.16
  4742.6  230.89    4749  230.13  4792.1  229.65  4903.1  229.74  4913.3  230.22
  4919.8  229.75  4927.7  230.92  4934.1  229.92    4942   231.5  4948.2  230.34
  4973.1   230.8  4983.1  229.99  4990.1   226.3  4992.9   225.8  4996.1   226.3
  5013.1  228.75  5033.1  230.22  5133.2  231.84  5203.2  233.98    5230  235.53
#Mann= 4 ,-1 , 0
  4427.5     .05       0  4903.1     .16       0  4990.1     .07       0
  4996.1     .16       0
Bank Sta=4990.1,4996.1
XS Rating Curve= 0 ,0
Exp/Cntr=0.3,0.1

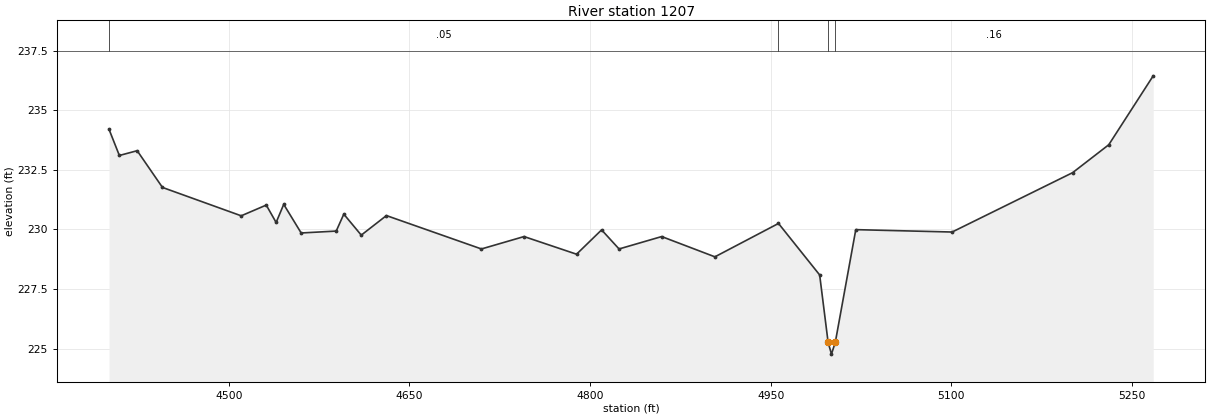
Type RM Length L Ch R = 1 ,1207    ,0,0,0
BEGIN DESCRIPTION:
UNT05259 IN WICK 1.0
END DESCRIPTION:
XS GIS Cut Line= 4
      3587833.39      10237735.4      3587888.95     10237655.53
      3588210.13     10237410.74      3588204.95      10237044.7
#Sta/Elev= 30
  4400.5   234.2  4409.1   233.1  4423.9   233.3  4444.9  231.76  4510.3  230.57
  4531.1  231.02  4539.3  230.29  4545.6  231.05  4560.1  229.85  4589.2  229.93
  4595.5  230.64    4610  229.76  4630.9  230.58  4709.8  229.18  4745.2   229.7
  4788.8  228.96  4809.6  229.98  4824.1  229.18  4859.5   229.7  4903.7  228.85
  4956.5  230.25  4990.7  228.09  4997.7  225.27  5000.5  224.77  5003.7  225.27
  5020.7  229.99  5100.7  229.89  5200.8  232.38  5230.8  233.55  5267.7  236.44
#Mann= 4 ,-1 , 0
  4400.5     .05       0  4956.5     .16       0  4997.7     .07       0
  5003.7     .16       0
Bank Sta=4997.7,5003.7
XS Rating Curve= 0 ,0
Exp/Cntr=0.3,0.1

Chan Stop Cuts=-1
Use User Specified Reach Order=0
Composite Channel Slope=5