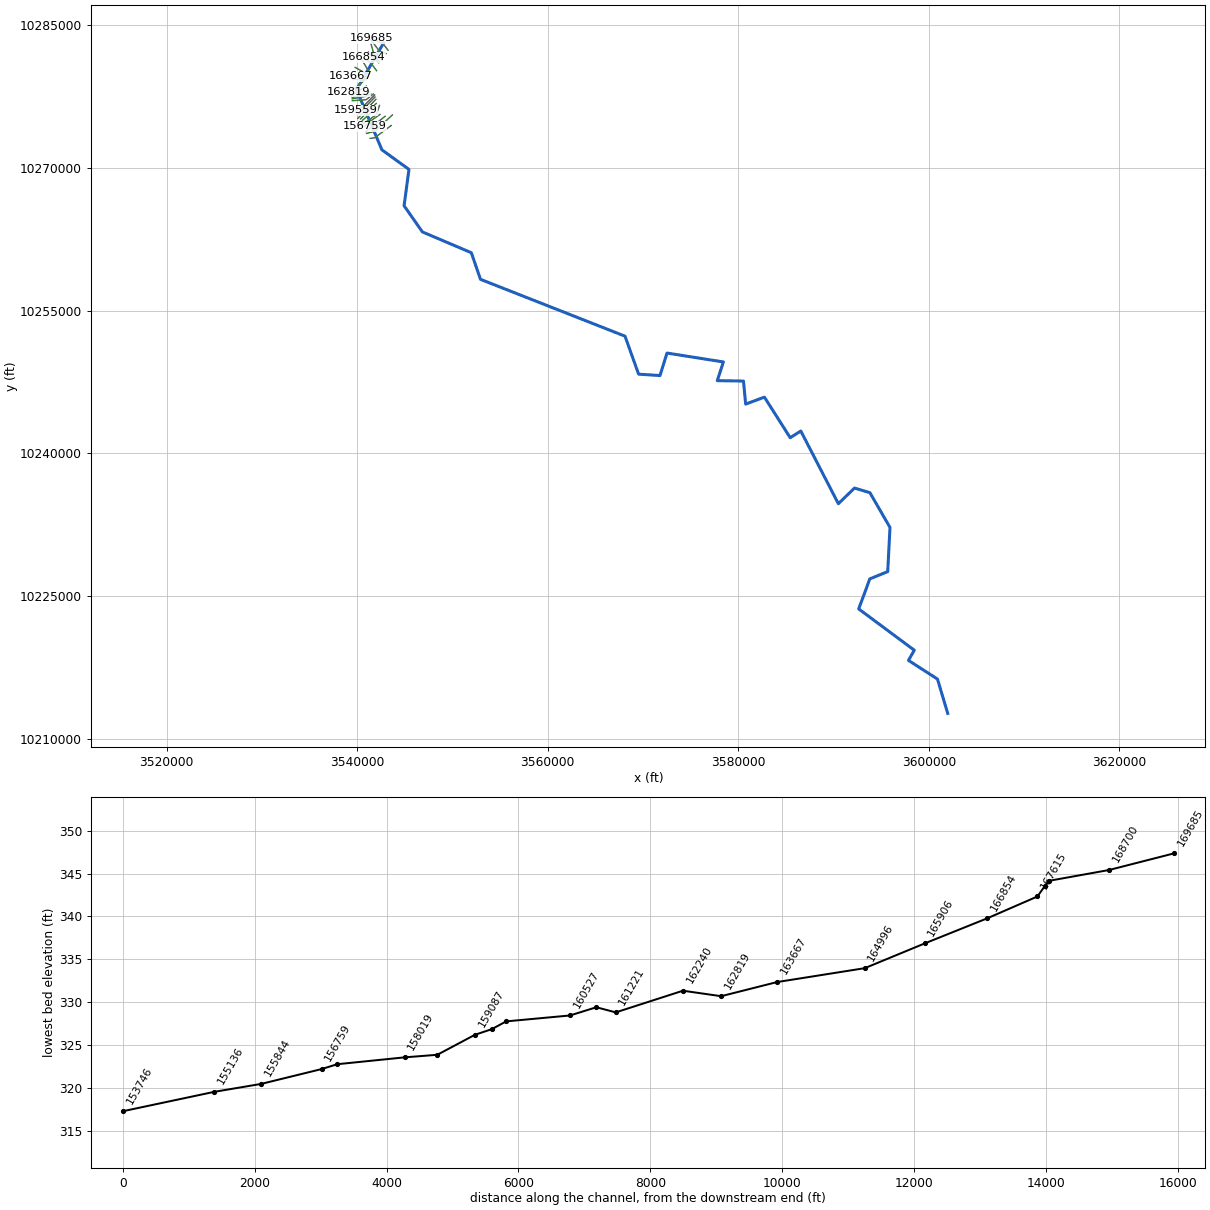
--- WICKSON CREEK.prj (project) ---

Proj Title=WICKSON CREEK Base Level Engineering
Current Plan=p01
Default Exp/Contr=0.3,0.1
English Units
Geom File=g01
Flow File=f01
Plan File=p01
Y Axis Title=Elevation
X Axis Title(PF)=Main Channel Distance
X Axis Title(XS)=Station
BEGIN DESCRIPTION:
WICKSON CREEK
END DESCRIPTION:
DSS Export Rating Curves= 0
DSS Export Rating Curve Sorted= 0
DSS Export Volume Flow Curves= 0
DXF OffsetX= 0
DXF OffsetY= 0
DXF ScaleX= 1
DXF ScaleY= 10

--- WICKSON CREEK.p01 (plan) ---

Plan Title=Multiple Run
Short Identifier=Multiple
Geom File=g01
Flow File=f01
Subcritical Flow
K Sum by GR= 0
Std Step Tol= 0.01
Critical Tol= 0.01
Num of Std Step Trials= 20
Max Error Tol= 0.3
Flow Tol Ratio= 0.001
Split Flow NTrial= 30
Split Flow Tol= 0.02
Split Flow Ratio= 0.02
Log Output Level= 0
Friction Slope Method= 1
Unsteady Friction Slope Method= 2
Unsteady Bridges Friction Slope Method= 1
Parabolic Critical Depth
Global Vel Dist=  1 , 1 , 1
Global Log Level= 0
CheckData=True
Encroach Param= -1, 0, 0, 0
BEGIN DESCRIPTION:
Multiple Run
END DESCRIPTION:

--- WICKSON CREEK.f01 (steady flow) ---

Flow Title=Multiple
Program Version=4.10
Number of Profiles= 7
Profile Names=10-year,25-year,50-year,1pct_min,100-year,1pct_plu,500-year
River Rch & RM=WICKSON CREEK,Reach-1         ,169685
     519     692     830     730     988    1336    1400
River Rch & RM=WICKSON CREEK,Reach-1         ,167730
    1085    1507    1859    1676    2266    3064    3380
River Rch & RM=WICKSON CREEK,Reach-1         ,166854
    1085    1507    1859    1676    2266    3064    3380
River Rch & RM=WICKSON CREEK,Reach-1         ,162240
    1313    1840    2283    2070    2799    3785    4221
River Rch & RM=WICKSON CREEK,Reach-1         ,160527
    1452    2030    2515    2274    3075    4159    4614
River Rch & RM=WICKSON CREEK,Reach-1         ,145453
    1712    2404    2987    2707    3661    4951    5518
River Rch & RM=WICKSON CREEK,Reach-1         ,139852
    2714    3877    4874    4463    6036    8163    9289
River Rch & RM=WICKSON CREEK,Reach-1         ,132818
    3330    4785    6039    5549    7504   10149   11627
River Rch & RM=WICKSON CREEK,Reach-1         ,130718
    3190    4579    5775    5302    7171    9698   11096
River Rch & RM=WICKSON CREEK,Reach-1         ,125846
    3438    4932    6217    5705    7715   10434   11920
River Rch & RM=WICKSON CREEK,Reach-1         ,117075
    3546    5079    6396    5861    7927   10720   12216
River Rch & RM=WICKSON CREEK,Reach-1         ,114881
    4443    6413    8119    7477   10112   13675   15734
River Rch & RM=WICKSON CREEK,Reach-1         ,111131
    4379    6300    7957    7310    9887   13370   15309
River Rch & RM=WICKSON CREEK,Reach-1         ,107055
    4403    6326    7986    7331    9914   13408   15328
River Rch & RM=WICKSON CREEK,Reach-1         ,99859
    4417    6341    7999    7338    9924   13421   15323
River Rch & RM=WICKSON CREEK,Reach-1         ,91302
    5963    8604   10893   10024   13556   18333   21048
River Rch & RM=WICKSON CREEK,Reach-1         ,86403
    5963    8604   10893   10024   13556   18333   21048
River Rch & RM=WICKSON CREEK,Reach-1         ,83158
    6133    8851   11206   10312   13946   18860   21653
River Rch & RM=WICKSON CREEK,Reach-1         ,73759
    6195    8932   11304   10396   14059   19013   21802
River Rch & RM=WICKSON CREEK,Reach-1         ,70897
    6399    9212   11646   10697   14466   19564   22376
River Rch & RM=WICKSON CREEK,Reach-1         ,68155
    6399    9212   11646   10697   14466   19564   22376
River Rch & RM=WICKSON CREEK,Reach-1         ,57540
    6412    9223   11653   10697   14467   19565   22351
River Rch & RM=WICKSON CREEK,Reach-1         ,53782
    6424    9231   11654   10690   14457   19552   22300
River Rch & RM=WICKSON CREEK,Reach-1         ,51627
    6424    9231   11654   10690   14457   19552   22300
River Rch & RM=WICKSON CREEK,Reach-1         ,49437
    6919    9950   12570   11536   15602   21099   24087
River Rch & RM=WICKSON CREEK,Reach-1         ,42310
    6919    9950   12570   11536   15602   21099   24087
River Rch & RM=WICKSON CREEK,Reach-1         ,26566
    7006   10076   12731   11685   15803   21372   24401
River Rch & RM=WICKSON CREEK,Reach-1         ,25485
    6949    9979   12594   11546   15614   21117   24054
River Rch & RM=WICKSON CREEK,Reach-1         ,22763
    7043   10120   12777   11718   15848   21432   24432
River Rch & RM=WICKSON CREEK,Reach-1         ,19360
    7692   11053   13958   12802   17313   23414   26689
River Rch & RM=WICKSON CREEK,Reach-1         ,16416
    7692   11053   13958   12802   17313   23414   26689
Boundary for River Rch & Prof#=WICKSON CREEK,Reach-1         , 1
Up Type= 0
Dn Type= 3
Dn Slope=0.001
Boundary for River Rch & Prof#=WICKSON CREEK,Reach-1         , 2
Up Type= 0
Dn Type= 3
Dn Slope=0.001
Boundary for River Rch & Prof#=WICKSON CREEK,Reach-1         , 3
Up Type= 0
Dn Type= 3
Dn Slope=0.001
Boundary for River Rch & Prof#=WICKSON CREEK,Reach-1         , 4
Up Type= 0
Dn Type= 3
Dn Slope=0.001
Boundary for River Rch & Prof#=WICKSON CREEK,Reach-1         , 5
Up Type= 0
Dn Type= 3
Dn Slope=0.001
Boundary for River Rch & Prof#=WICKSON CREEK,Reach-1         , 6
Up Type= 0
Dn Type= 3
Dn Slope=0.001
Boundary for River Rch & Prof#=WICKSON CREEK,Reach-1         , 7
Up Type= 0
Dn Type= 3
Dn Slope=0.001
DSS Import GetInterval= 0
DSS Import GetPeak= 0
DSS Import FillOption= 0

--- WICKSON CREEK.g01 (geometry) ---

Geom Title=Existing Conditions
Program Version=4.10

River Reach=WICKSON CREEK   ,Reach-1
Reach XY= 30
      3542762.11     10283081.64      3539932.92     10278194.37
      3542597.44     10271878.89      3545437.19      10269821.1
      3544924.11      10266006.7      3546845.55      10263258.2
      3551981.96     10261071.48      3552943.34     10258274.76
      3568108.42     10252304.46       3569537.6      10248313.7
      3571778.85     10248169.84      3572517.97     10250530.36
       3578434.9     10249596.31      3577792.08     10247631.51
      3580541.27     10247589.38      3580773.01     10245171.56
      3582740.03     10245898.46      3585445.53     10241639.09
      3586559.97     10242342.97      3590498.93     10234705.12
      3592193.42     10236349.29      3593809.02     10235865.05
      3595919.37     10232210.47      3595678.16     10227572.35
       3593800.2      10226807.5      3592634.63     10223653.12
      3598468.66     10219315.59      3597857.62     10218249.01
      3600902.05     10216281.58      3601977.21     10212680.81

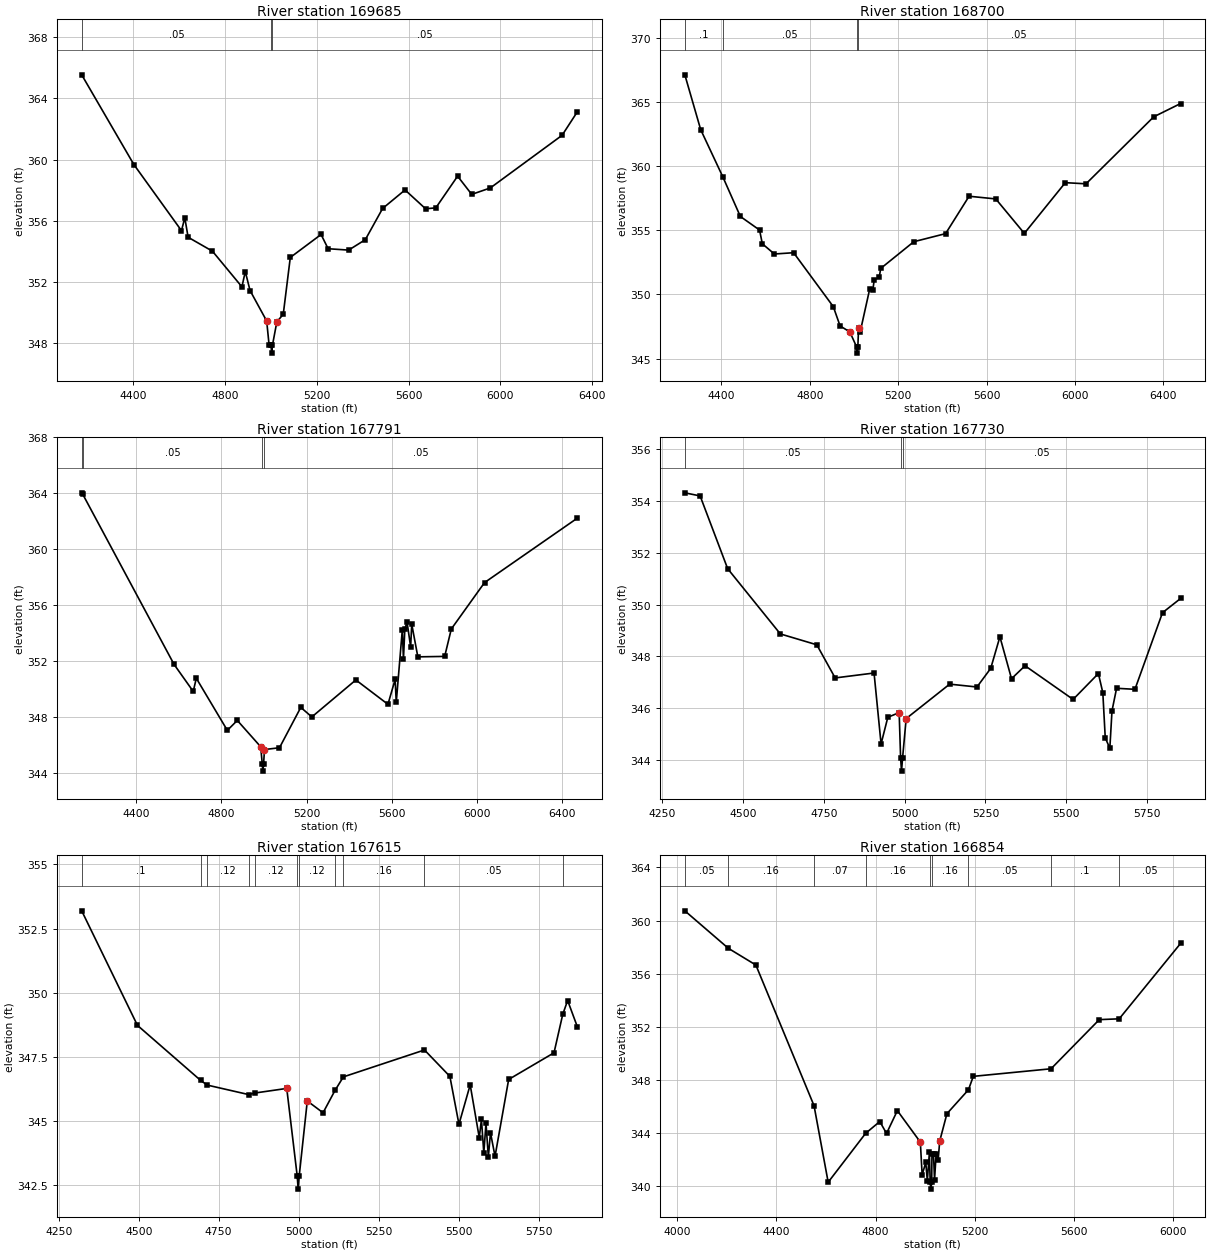
Type RM Length L Ch R = 1 ,169685  ,985,985,985
BEGIN DESCRIPTION:
WICKSON CREEK 123.0
END DESCRIPTION:
XS GIS Cut Line= 3
      3543242.12     10282341.63      3542742.11     10282991.64
      3541542.12     10283591.63
#Sta/Elev= 30
  4174.6  365.54    4402  359.68  4609.6  355.36  4624.1   356.2  4638.6  354.93
  4744.6  354.02  4873.2  351.69  4887.8  352.69  4908.6  351.45  4981.1  349.46
  4991.5  347.91  5000.1  347.86  5002.8  347.36  5006.1  347.86  5025.4   349.4
  5053.4   349.9  5084.1  353.61  5218.3  355.11    5249  354.18  5338.5  354.09
  5411.1  354.77  5486.6  356.81  5584.4  358.02  5673.9  356.79  5718.6  356.85
  5813.6  358.92  5875.1  357.73  5956.2  358.15  6269.2  361.59  6336.3  363.14
#Mann= 3 ,-1 , 0
  4174.6     .05       0  5000.1     .03       0  5006.1     .05       0
Bank Sta=4981.1,5025.4
XS Rating Curve= 0 ,0
Exp/Cntr=0.3,0.1

Type RM Length L Ch R = 1 ,168700  ,909,909,909
BEGIN DESCRIPTION:
WICKSON CREEK 121.0
END DESCRIPTION:
XS GIS Cut Line= 3
      3543042.14     10281991.63      3542342.11     10282241.64
      3541442.13     10283441.61
#Sta/Elev= 30
  4234.9  367.15  4306.6  362.87  4406.6  359.19  4486.1  356.09  4573.1  355.03
  4585.4  353.96    4640  353.16  4727.1  353.26  4906.6  349.05  4937.4  347.54
  4981.4  347.08  5011.7  345.92  5014.5  345.42  5017.7  345.92    5021  347.35
  5028.2  347.07    5071   350.4  5085.5  350.33  5091.8  351.15  5114.7  351.35
    5121  352.03    5271  354.12  5414.7  354.75    5521  357.67  5641.8  357.46
    5771  354.77  5956.4  358.73  6050.1  358.64  6356.4  363.87  6478.2  364.91
#Mann= 4 ,-1 , 0
  4234.9      .1       0  4406.6     .05       0  5011.7     .03       0
  5017.7     .05       0
Bank Sta=4981.4,5021
XS Rating Curve= 0 ,0
Exp/Cntr=0.3,0.1

Type RM Length L Ch R = 1 ,167791  ,61,61,61
BEGIN DESCRIPTION:
WICKSON CREEK 119.0
END DESCRIPTION:
XS GIS Cut Line= 3
      3542642.15     10281291.62      3541842.11     10281641.64
       3541442.1     10283041.66
#Sta/Elev= 30
  4143.5  364.03    4148  363.94  4577.4  351.78  4667.5  349.85  4681.9  350.79
  4827.7  347.07  4874.5  347.78  4984.4   345.9  4991.9  344.66  4994.7  344.16
  4997.9  344.66  5002.3   345.7  5072.7  345.83  5172.8  348.71  5224.8  348.03
  5431.5  350.67  5582.3  348.93  5616.1  350.71  5621.3  349.07  5649.9  354.27
  5655.1  352.15  5661.6  354.29    5672  354.81  5688.9  353.03  5694.1  354.65
  5722.7  352.32  5848.8  352.35    5880  354.31    6036  357.62  6472.8  362.23
#Mann= 4 ,-1 , 0
  4143.5      .1       0    4148     .05       0  4991.9     .03       0
  4997.9     .05       0
Bank Sta=4984.4,5002.3
XS Rating Curve= 0 ,0
Exp/Cntr=0.3,0.1

Type RM Length L Ch R = 1 ,167730  ,115,115,115
BEGIN DESCRIPTION:
Mapping XS b863c6ec
END DESCRIPTION:
XS GIS Cut Line= 2
      3542335.74     10281128.14      3541192.52     10282151.58
#Sta/Elev= 30
  4319.6  354.32  4366.9   354.2  4452.1  351.39  4615.1  348.87    4728  348.45
  4784.8  347.17  4905.2  347.36  4926.9  344.62  4947.8  345.65  4982.9  345.83
  4987.4  344.07  4990.2  343.57  4993.4  344.07  5004.6   345.6  5139.2  346.93
  5223.7  346.82  5266.3  347.54  5294.7  348.76  5330.6  347.14  5372.5  347.64
  5521.2  346.34  5599.5  347.34  5613.2   346.6  5620.7  344.86  5634.9  344.45
  5641.6   345.9  5655.8  346.77  5712.6  346.73  5797.9  349.69    5854  350.24
#Mann= 3 ,-1 , 0
  4319.6     .05       0  4987.4     .04       0  4993.4     .05       0
Bank Sta=4982.9,5004.6
XS Rating Curve= 0 ,0
Exp/Cntr=0.3,0.1

Type RM Length L Ch R = 1 ,167615  ,761,761,761
BEGIN DESCRIPTION:
Mapping XS 2ab0189f
END DESCRIPTION:
XS GIS Cut Line= 2
       3542273.2     10281026.62        3541130.     10282073.47
#Sta/Elev= 30
  4321.8  353.19  4496.1  348.72  4693.9  346.57  4714.3  346.39  4843.7  346.02
    4863  346.08  4962.9  346.26  4995.7  342.83  4998.5  342.33  5001.7  342.83
  5027.1  345.77  5076.4  345.31  5113.7  346.18  5139.9  346.71  5393.5  347.76
  5472.9  346.73  5501.3  344.86  5536.4   346.4  5564.8  344.34  5571.6  345.05
    5579  343.74  5585.8   344.9  5593.2  343.59  5599.9  344.53  5614.1  343.61
  5656.7  346.61  5798.5  347.65  5825.8  349.15  5841.1  349.69  5871.9  348.65
#Mann= 11 ,-1 , 0
  4321.8      .1       0  4693.9     .05       0  4714.3     .12       0
  4843.7     .05       0    4863     .12       0  4995.7     .07       0
  5001.7     .12       0  5113.7     .05       0  5139.9     .16       0
  5393.5     .05       0  5825.8      .1       0
Bank Sta=4962.9,5027.1
XS Rating Curve= 0 ,0
Exp/Cntr=0.3,0.1

Type RM Length L Ch R = 1 ,166854  ,948,948,948
BEGIN DESCRIPTION:
WICKSON CREEK 118.0
END DESCRIPTION:
XS GIS Cut Line= 3
      3542042.13     10280191.61      3541442.11     10280991.64
      3540642.13     10281591.62
#Sta/Elev= 30
  4030.8  360.73  4206.2  357.91  4317.3  356.65    4552  346.06    4609   340.3
  4760.1  343.98  4817.3  344.87  4844.4  343.97  4888.1  345.69  4980.8  343.32
  4988.1  340.86  5002.7  341.79    5009  340.41  5017.3  342.54  5020.5  340.28
  5023.3  339.78  5026.5  340.28  5027.7  342.39    5034  342.39  5038.1  340.48
  5044.4  342.39  5052.7  341.99    5059   343.4  5088.1  345.46  5174.9  347.26
  5194.4  348.27  5508.1  348.84  5702.7  352.54    5783   352.6  6030.8  358.28
#Mann= 9 ,-1 , 0
  4030.8     .05       0  4206.2     .16       0    4552     .07       0
  4760.1     .16       0  5020.5     .07       0  5026.5     .16       0
  5174.9     .05       0  5508.1      .1       0    5783     .05       0
Bank Sta=4980.8,5059
XS Rating Curve= 0 ,0
Exp/Cntr=0.3,0.1

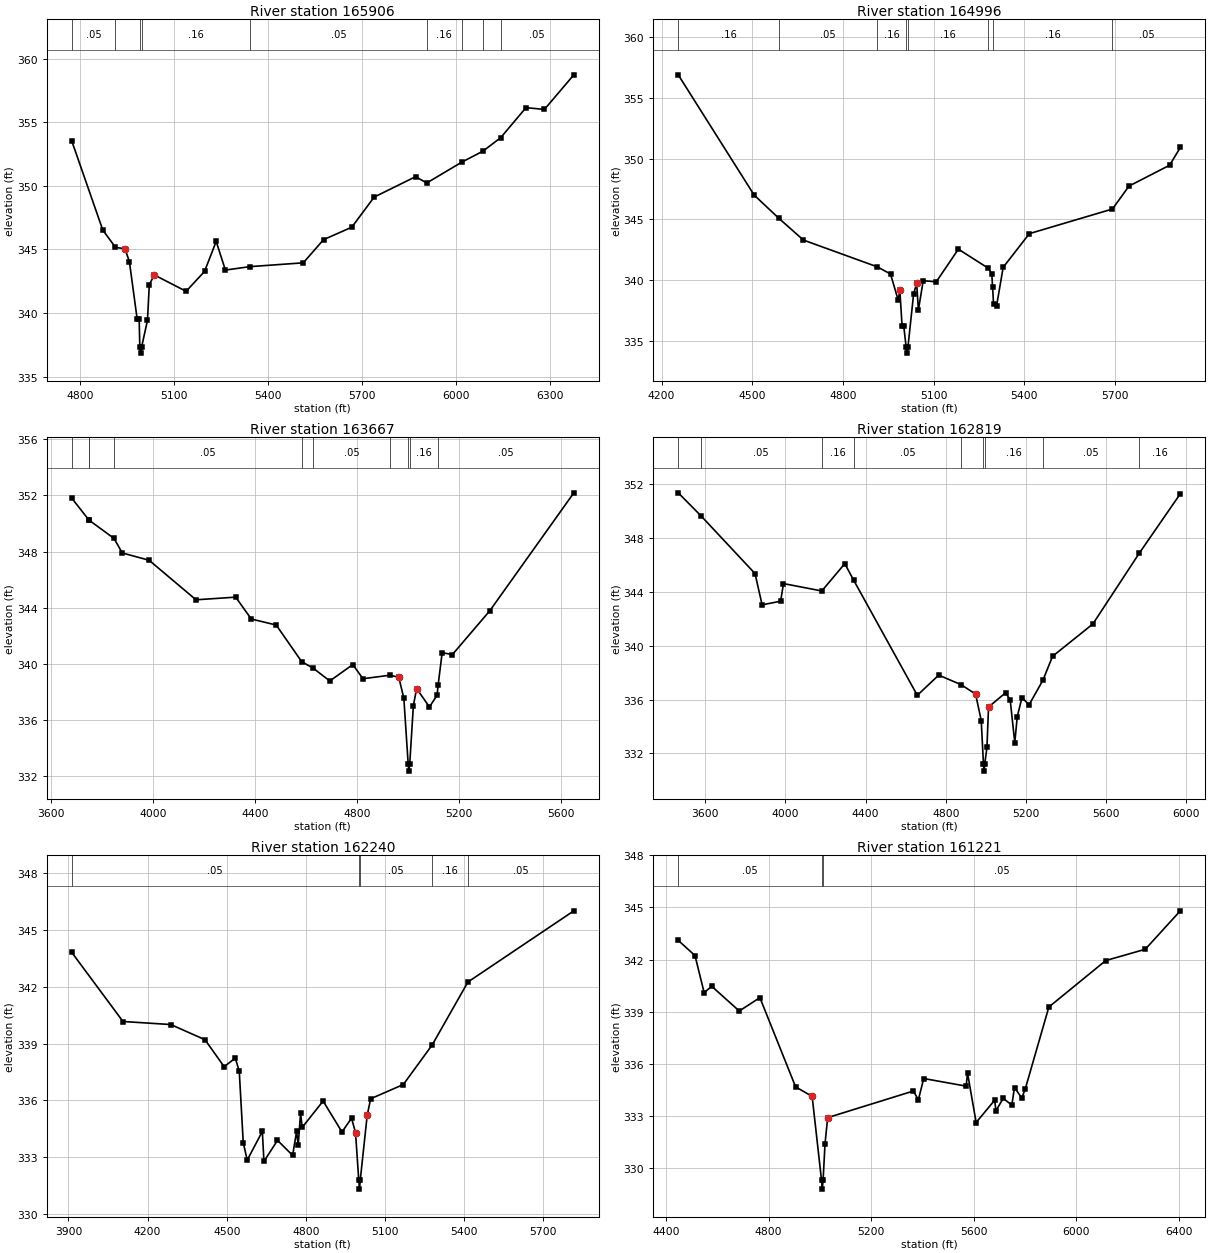
Type RM Length L Ch R = 1 ,165906  ,910,910,910
BEGIN DESCRIPTION:
WICKSON CREEK 116.0
END DESCRIPTION:
XS GIS Cut Line= 3
      3541292.09     10280091.65      3541142.11     10280241.64
      3540442.09     10281441.68
#Sta/Elev= 30
  4773.3  353.53  4872.3  346.52  4912.7  345.17    4943  345.05  4957.1  344.04
  4981.9  339.52  4988.3  339.52  4990.3  337.35    4993  336.85  4996.3  337.35
  5014.8  339.44  5020.6  342.23  5036.3     343    5138  341.71  5196.7  343.27
  5233.9  345.63  5263.3  343.38  5341.6  343.65  5511.8  343.95  5576.3  345.77
  5666.4  346.75  5737.9  349.12  5869.8  350.72  5905.7  350.23  6016.9  351.86
  6084.8  352.73  6141.4  353.79  6222.1  356.15  6280.8  356.01  6374.7  358.73
#Mann= 9 ,-1 , 0
  4773.3     .05       0  4912.7     .16       0  4990.3     .07       0
  4996.3     .16       0  5341.6     .05       0  5905.7     .16       0
  6016.9     .05       0  6084.8     .16       0  6141.4     .05       0
Bank Sta=4943,5036.3
XS Rating Curve= 0 ,0
Exp/Cntr=0.3,0.1

Type RM Length L Ch R = 1 ,164996  ,1329,1329,1329
BEGIN DESCRIPTION:
WICKSON CREEK 114.0
END DESCRIPTION:
XS GIS Cut Line= 3
      3541292.06     10279841.66      3540592.11     10280091.64
      3539792.13     10280541.63
#Sta/Elev= 30
    4255   356.9  4506.1  346.99    4588  345.07  4669.1  343.28  4913.8  341.07
  4957.4  340.48  4982.9  338.31  4988.2  339.15  4995.6  336.19  5001.1  336.19
    5009  334.46  5011.7  333.96    5015  334.46  5033.6  338.81  5043.8  339.72
  5049.6  337.52  5065.5  339.93  5108.8  339.84  5181.8  342.53  5280.7  340.96
  5292.4   340.5    5295  339.39  5298.2  338.02    5308  337.82    5330  341.03
  5416.7  343.81  5691.7  345.84  5746.3  347.73  5880.8  349.45  5916.1  350.91
#Mann= 8 ,-1 , 0
    4255     .16       0    4588     .05       0  4913.8     .16       0
    5009     .07       0    5015     .16       0  5280.7     .12       0
    5295     .16       0  5691.7     .05       0
Bank Sta=4988.2,5043.8
XS Rating Curve= 0 ,0
Exp/Cntr=0.3,0.1

Type RM Length L Ch R = 1 ,163667  ,848,848,848
BEGIN DESCRIPTION:
WICKSON CREEK 112.0
END DESCRIPTION:
XS GIS Cut Line= 4
      3541062.37     10279587.22       3540397.8     10279248.53
      3539553.91     10279288.38      3539357.52     10279611.44
#Sta/Elev= 30
  3680.9  351.81  3746.8  350.28    3748  350.25  3846.5  348.94    3879   347.9
  3984.2  347.38  4168.1  344.56  4323.7  344.75  4384.8  343.19  4482.6  342.76
  4582.4  340.15  4628.5  339.67  4692.8  338.77  4782.9  339.94  4822.9  338.93
  4928.1  339.18  4963.1  339.04  4983.1  337.53  5000.1  332.84  5002.9  332.34
  5006.1  332.84  5020.5  337.02  5033.2  338.23  5083.2  336.92  5113.3  337.74
  5117.5  338.48  5133.3  340.79  5173.3  340.65  5319.8  343.77  5649.7  352.19
#Mann= 10 ,-1 , 0
  3680.9      .1       0  3746.8     .16       0    3748      .1       0
  3846.5     .05       0  4582.4     .16       0  4628.5     .05       0
  4928.1     .16       0  5000.1     .07       0  5006.1     .16       0
  5117.5     .05       0
Bank Sta=4963.1,5033.2
XS Rating Curve= 0 ,0
Exp/Cntr=0.3,0.1

Type RM Length L Ch R = 1 ,162819  ,579,579,579
BEGIN DESCRIPTION:
WICKSON CREEK 110.0
END DESCRIPTION:
XS GIS Cut Line= 3
      3541142.08     10279491.62      3539942.11     10278491.64
      3539142.12     10277991.65
#Sta/Elev= 30
  3464.9  351.36  3577.2  349.67  3848.2  345.36  3883.4  343.04  3975.8  343.31
  3990.1  344.62  4181.3  344.07    4296   346.1  4340.7  344.86  4657.9  336.32
  4764.6  337.82  4876.7  337.11  4948.8  336.41  4976.8  334.45  4988.1  331.19
  4990.9  330.69  4994.1  331.19  5005.4  332.45  5013.3  335.45  5098.3  336.51
  5121.3  335.99  5144.3   332.8  5156.6  334.74  5180.2  336.15  5215.6  335.62
  5284.3  337.43  5332.9  339.22    5534  341.62  5764.8  346.86  5970.3  351.29
#Mann= 9 ,-1 , 0
  3464.9      .1       0  3577.2     .05       0  4181.3     .16       0
  4340.7     .05       0  4876.7     .16       0  4988.1     .07       0
  4994.1     .16       0  5284.3     .05       0  5764.8     .16       0
Bank Sta=4948.8,5013.3
XS Rating Curve= 0 ,0
Exp/Cntr=0.3,0.1

Type RM Length L Ch R = 1 ,162240  ,1019,1019,1019
BEGIN DESCRIPTION:
Mapping XS 24a19fb8
END DESCRIPTION:
XS GIS Cut Line= 2
        3540960.     10278572.42      3539366.02     10277533.62
#Sta/Elev= 30
  3912.9   343.8    4107  340.16  4288.1     340  4417.8   339.2  4490.3  337.78
  4532.5  338.23  4547.6  337.54  4562.7  333.78  4577.8  332.86  4635.1  334.37
  4641.1  332.79  4692.5   333.9  4749.8  333.11  4764.9  334.37  4770.9  333.64
    4780  335.33    4786  334.58  4865.3  335.97  4936.9  334.34  4973.1  335.07
  4988.2   334.3  5000.3  331.83  5003.1  331.33  5006.3  331.83  5032.4  335.22
  5045.5  336.09  5169.3  336.84  5278.9  338.93  5414.1  342.24  5815.5  345.99
#Mann= 5 ,-1 , 0
  3912.9     .05       0  5000.3     .03       0  5006.3     .05       0
  5278.9     .16       0  5414.1     .05       0
Bank Sta=4988.2,5032.4
XS Rating Curve= 0 ,0
Exp/Cntr=0.3,0.1

Type RM Length L Ch R = 1 ,161221  ,294,294,294
BEGIN DESCRIPTION:
Mapping XS 6b78b523
END DESCRIPTION:
XS GIS Cut Line= 3
      3541324.54     10278021.17      3541042.43     10277825.87
      3539490.77     10277374.48
#Sta/Elev= 30
  4447.1   343.1  4512.4  342.23  4548.2   340.1  4577.9  340.46  4685.3  339.04
  4765.7  339.81  4905.1  334.68  4969.6  334.13  5006.3   329.3    5009   328.8
  5012.3   329.3  5019.7  331.38  5030.1  332.91  5364.4  334.44  5384.2  333.94
    5405  335.16  5570.7  334.72  5575.9  335.48  5609.5  332.63  5681.7  333.91
  5686.9  333.31  5715.2  334.02  5748.7  333.63  5759.2  334.64  5787.5  334.04
  5800.8  334.54  5893.3  339.27  6115.2  341.94  6269.4  342.59  6406.2   344.8
#Mann= 3 ,-1 , 0
  4447.1     .05       0  5006.3     .03       0  5012.3     .05       0
Bank Sta=4969.6,5030.1
XS Rating Curve= 0 ,0
Exp/Cntr=0.3,0.1

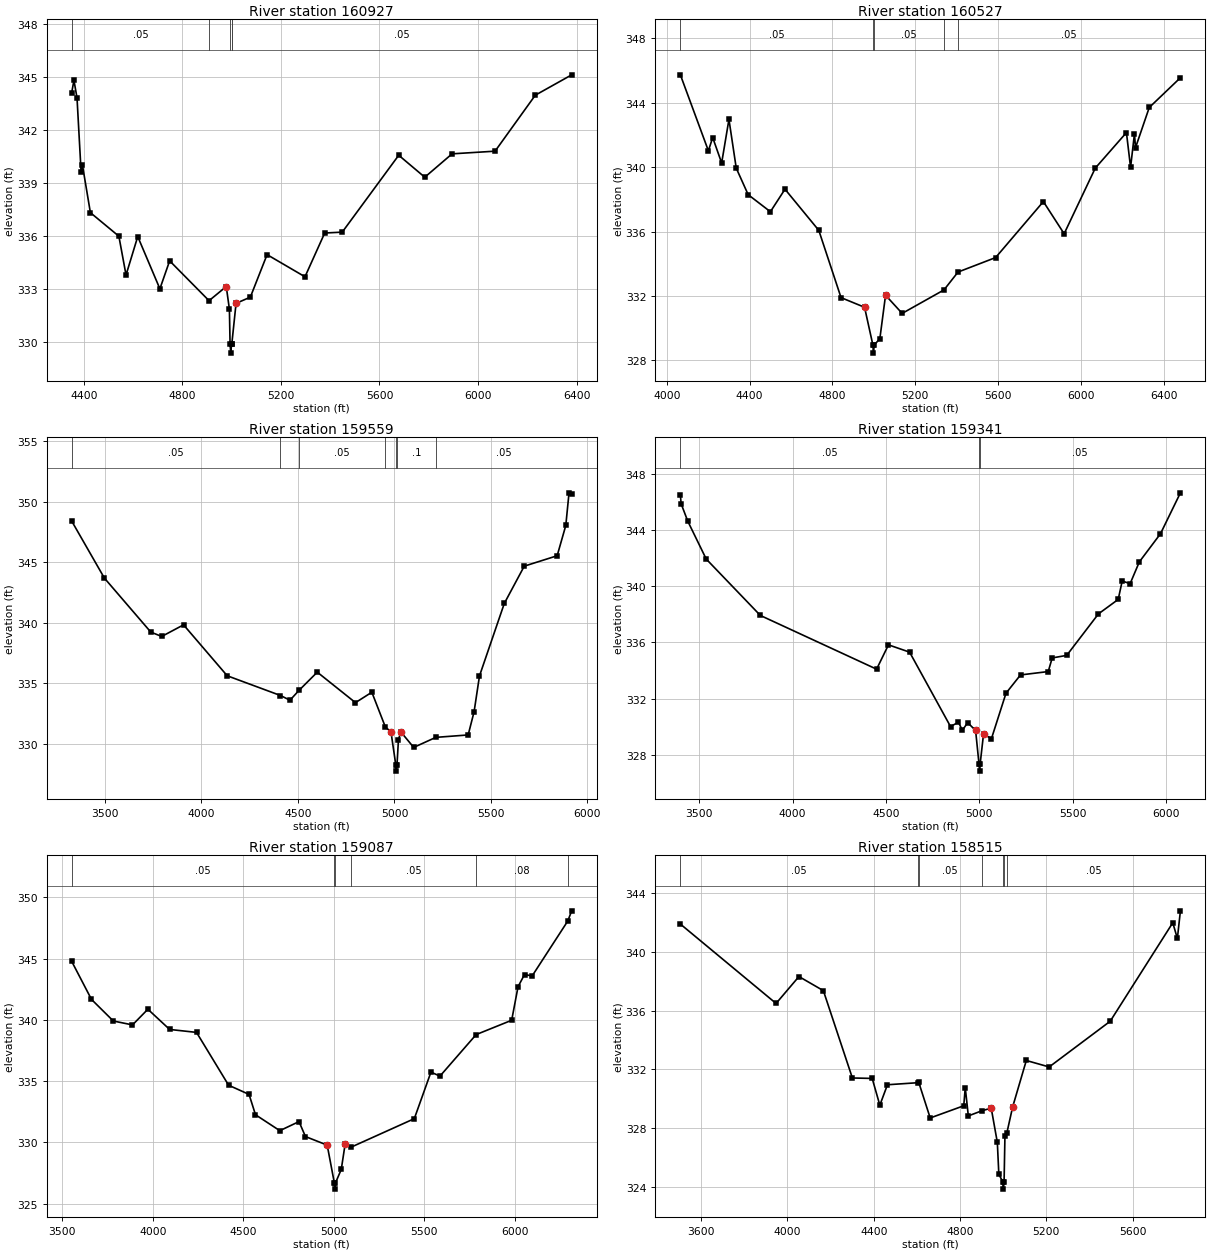
Type RM Length L Ch R = 1 ,160927  ,400,400,400
BEGIN DESCRIPTION:
WICKSON CREEK 108.0
END DESCRIPTION:
XS GIS Cut Line= 3
      3541442.15     10277741.66      3540846.56     10277490.68
      3539486.17     10277238.94
#Sta/Elev= 30
  4350.6  344.09  4359.8   344.8  4372.3  343.81  4388.9  339.62  4394.4  340.01
  4426.6  337.33  4542.2     336  4571.3  333.81  4618.8  335.98  4708.7  333.03
  4748.3  334.61  4908.2  332.36  4978.1  333.16  4990.9  331.88  4993.6   329.9
  4996.4   329.4  4999.6   329.9  5000.5   329.9  5017.9  332.21  5075.9  332.56
  5143.8  334.96  5297.7  333.71  5377.7  336.18  5448.9  336.23  5678.2  340.57
    5784  339.33  5894.8  340.65  6069.3   340.8  6232.6  343.96  6380.4  345.11
#Mann= 5 ,-1 , 0
  4350.6     .05       0  4908.2      .1       0  4993.6     .07       0
  4999.6      .1       0  5000.5     .05       0
Bank Sta=4978.1,5017.9
XS Rating Curve= 0 ,0
Exp/Cntr=0.3,0.1

Type RM Length L Ch R = 1 ,160527  ,968,968,968
BEGIN DESCRIPTION:
WICKSON CREEK 107.0
END DESCRIPTION:
XS GIS Cut Line= 3
      3541692.09     10277741.63      3540942.11     10277141.64
       3539492.1     10277041.64
#Sta/Elev= 30
  4065.8  345.74    4201  341.02  4221.9  341.84  4265.1  340.26  4300.3  342.97
  4335.5  339.94  4393.1  338.29  4500.4  337.23  4570.8  338.63  4734.1  336.07
  4841.4  331.89    4955  331.29  4995.2  328.94    4998  328.44  5001.2  328.94
  5028.8  329.34  5056.3  332.04  5136.5  330.91  5338.4  332.37  5406.1  333.48
  5587.6  334.38  5818.1  337.86  5918.4  335.86  6068.7  339.94  6219.1  342.15
  6239.1  339.99  6257.9  342.08  6262.9  341.21  6329.3  343.71  6479.7  345.56
#Mann= 5 ,-1 , 0
  4065.8     .05       0  4995.2     .03       0  5001.2     .05       0
  5338.4      .1       0  5406.1     .05       0
Bank Sta=4955,5056.3
XS Rating Curve= 0 ,0
Exp/Cntr=0.3,0.1

Type RM Length L Ch R = 1 ,159559  ,218,218,218
BEGIN DESCRIPTION:
WICKSON CREEK 106.0
END DESCRIPTION:
XS GIS Cut Line= 3
      3541842.08     10277641.62      3540642.11     10276441.64
      3539842.15     10276041.66
#Sta/Elev= 30
  3327.2  348.42  3496.9   343.7  3737.3  339.24  3793.9  338.88    3907  339.84
  4133.3  335.63  4409.3     334  4458.5  333.61  4505.8  334.43    4600  335.93
  4797.9  333.41  4882.8  334.27  4953.3  331.38  4981.8  331.01  5007.1  328.25
  5009.8  327.75  5013.1  328.25  5020.7  330.34  5032.6     331  5099.7  329.71
  5214.3  330.54    5382  330.74  5412.7  332.66  5440.7  335.62  5569.3  341.61
  5672.7  344.69  5843.2  345.55  5887.9  348.05  5904.7  350.75  5918.6  350.68
#Mann= 7 ,-1 , 0
  3327.2     .05       0  4409.3      .1       0  4505.8     .05       0
  4953.3      .1       0  5007.1     .07       0  5013.1      .1       0
  5214.3     .05       0
Bank Sta=4981.8,5032.6
XS Rating Curve= 0 ,0
Exp/Cntr=0.3,0.1

Type RM Length L Ch R = 1 ,159341  ,254,254,254
BEGIN DESCRIPTION:
WICKSON CREEK 105.0
END DESCRIPTION:
XS GIS Cut Line= 2
      3541869.74     10277429.92      3540014.25     10275498.48
#Sta/Elev= 30
  3399.2  346.46  3403.4  345.85  3438.6  344.62  3537.7  341.92  3827.6  337.91
  4450.2  334.09  4513.8  335.82    4627   335.3  4846.2  330.01  4888.6  330.32
  4909.7  329.74    4938  330.29  4980.5  329.73  4998.8  327.34  5001.6  326.84
  5004.8  327.34  5022.9  329.47  5065.4  329.15  5143.3  332.38    5221  333.68
  5369.5  333.92  5390.8  334.89  5468.5  335.07  5638.3  338.02  5744.3  339.05
  5765.7  340.36  5808.1  340.17  5857.5  341.72  5970.7  343.72  6077.5  346.63
#Mann= 3 ,-1 , 0
  3399.2     .05       0  4998.8     .03       0  5004.8     .05       0
Bank Sta=4980.5,5022.9
XS Rating Curve= 0 ,0
Exp/Cntr=0.3,0.1

Type RM Length L Ch R = 1 ,159087  ,572,572,572
BEGIN DESCRIPTION:
WICKSON CREEK 104.0
END DESCRIPTION:
XS GIS Cut Line= 2
       3541967.4     10277191.21      3540069.83     10275185.21
#Sta/Elev= 30
  3552.6  344.78  3662.1  341.67  3782.5  339.91  3888.5  339.59  3973.4  340.87
  4093.6  339.22  4242.1  338.98  4419.2  334.67  4532.1  333.92  4567.7  332.26
    4702  330.96    4808   331.7  4843.6  330.48  4963.7  329.78  5003.2  326.69
    5006  326.19  5009.2  326.69  5041.4   327.8  5062.9  329.89  5096.4  329.62
  5444.7  331.94  5536.6  335.74  5586.3  335.41  5786.1   338.8  5982.4  339.97
  6017.6  342.71  6053.2   343.7  6095.6  343.59  6291.8  348.06  6313.9   348.9
#Mann= 6 ,-1 , 0
  3552.6     .05       0  5003.2     .04       0  5009.2     .05       0
  5096.4     .05       0  5786.1     .08       0  6291.8     .05       0
Bank Sta=4963.7,5062.9
XS Rating Curve= 0 ,0
Exp/Cntr=0.3,0.1

Type RM Length L Ch R = 1 ,158515  ,496,496,496
BEGIN DESCRIPTION:
Mapping XS fbceb2e4
END DESCRIPTION:
XS GIS Cut Line= 2
      3542002.68     10276748.26      3540346.76     10275127.06
#Sta/Elev= 30
    3504  341.88  3947.5  336.48  4053.5  338.31  4166.7  337.35  4301.1  331.41
    4393  331.38  4428.4  329.56  4463.7  330.95  4605.8  331.09  4608.3  331.13
  4661.8  328.69  4817.3  329.52  4824.3  330.75  4838.5  328.83  4901.3  329.18
  4944.6  329.36  4972.9  327.03  4979.9  324.86  4998.2  324.35    5001  323.85
  5004.2  324.35  5008.2  327.47  5017.1  327.67  5043.7  329.43  5107.2   332.6
  5213.2  332.16  5496.1  335.27    5786  341.97  5807.3   340.9  5821.4  342.78
#Mann= 7 ,-1 , 0
    3504     .05       0  4605.8     .16       0  4608.3     .05       0
  4901.3     .16       0  4998.2     .07       0  5004.2     .16       0
  5017.1     .05       0
Bank Sta=4944.6,5043.7
XS Rating Curve= 0 ,0
Exp/Cntr=0.3,0.1

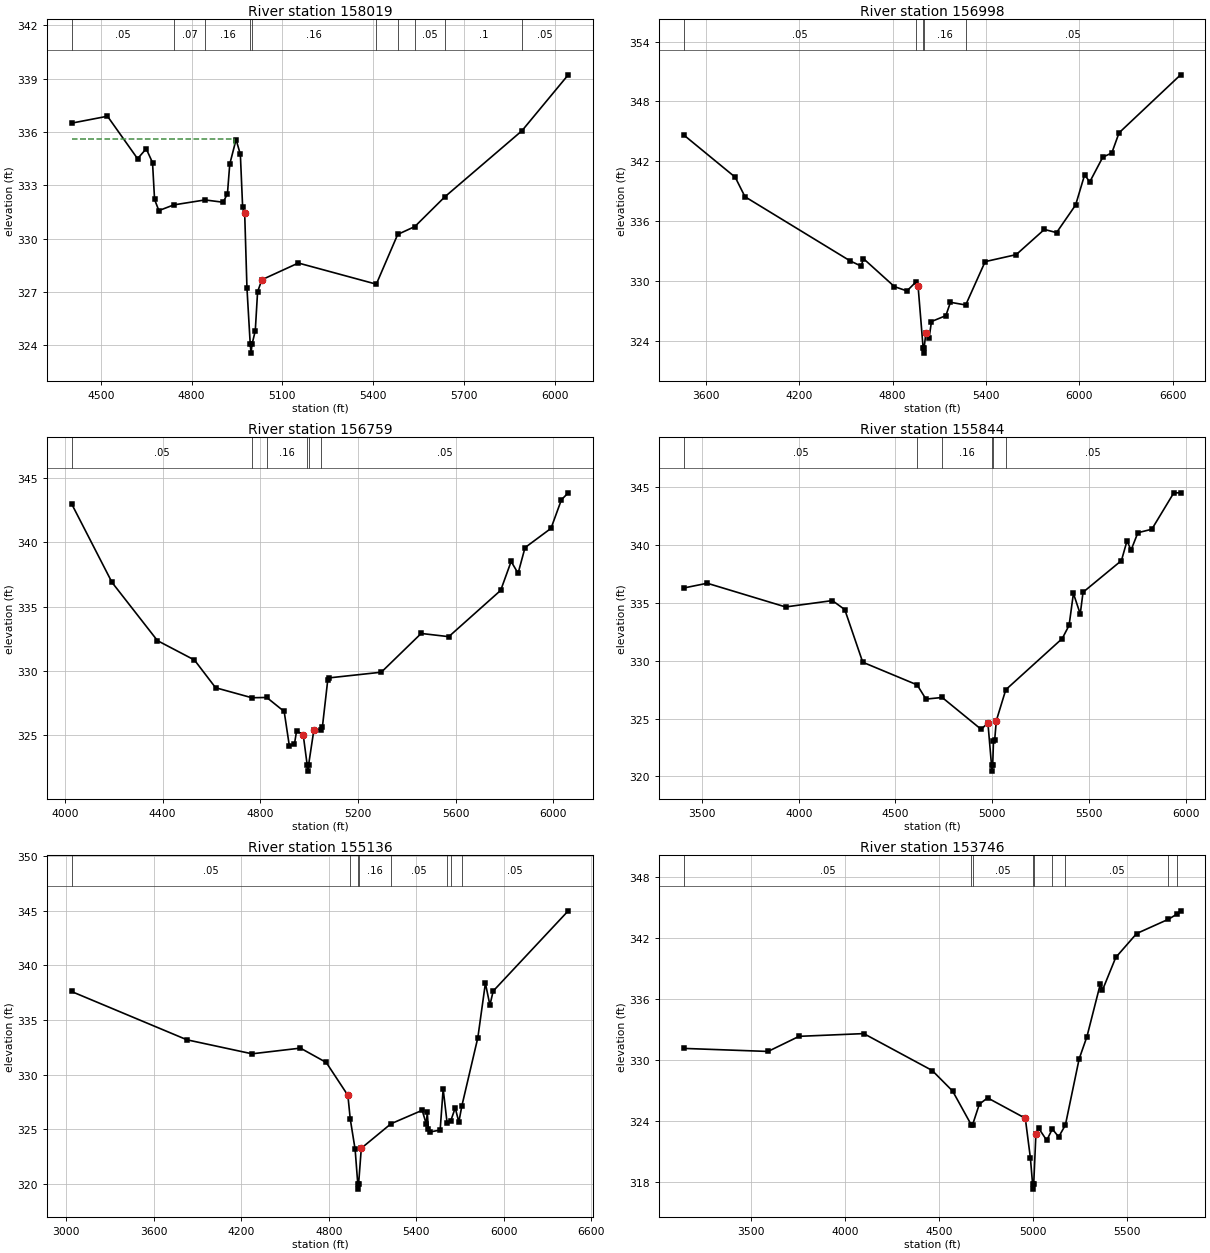
Type RM Length L Ch R = 1 ,158019  ,1021,1021,1021
BEGIN DESCRIPTION:
Mapping XS 511781c7
END DESCRIPTION:
XS GIS Cut Line= 2
       3541787.4     10276064.24      3540555.91     10274978.45
#Sta/Elev= 30
  4403.3  336.49  4522.2  336.88  4621.7  334.49  4650.2  335.05  4671.1  334.27
  4677.8   332.2    4692  331.57    4741  331.89  4844.6  332.17  4904.5  332.04
  4918.7  332.52  4926.3  334.18  4947.2  335.57  4961.4  334.73  4968.9  331.76
  4975.6  331.46  4983.2   327.2    4994  324.05  4996.7  323.55    5000  324.05
  5010.7  324.81  5018.3     327  5032.5  327.68    5153  328.62  5410.7  327.43
  5481.4  330.23  5537.9  330.67  5636.9  332.34  5891.9  336.06  6045.1  339.21
#Mann= 10 ,-1 , 0
  4403.3     .05       0    4741     .07       0  4844.6     .16       0
    4994     .07       0    5000     .16       0  5410.7     .05       0
  5481.4      .1       0  5537.9     .05       0  5636.9      .1       0
  5891.9     .05       0
#XS Ineff= 2 , 0
         4941.02  335.61
Permanent Ineff=
       F       F
Bank Sta=4975.6,5032.5
XS Rating Curve= 0 ,0
Exp/Cntr=0.3,0.1

Type RM Length L Ch R = 1 ,156998  ,239,239,239
BEGIN DESCRIPTION:
WICKSON CREEK 103.0
END DESCRIPTION:
XS GIS Cut Line= 4
      3542342.11     10276541.65      3542015.99     10275576.59
       3540896.2     10274790.14      3540156.85     10274467.32
#Sta/Elev= 30
  3458.1  344.63  3788.4   340.4  3851.3  338.44  4526.6  332.01    4598  331.48
  4612.9  332.23  4812.4  329.42  4892.6  328.99  4950.8  329.89    4964   329.5
  4996.8  323.25  4999.5  322.75  5002.8  323.25  5014.6  324.79  5035.5  324.31
  5050.3  325.92  5142.7  326.51  5172.3  327.85  5270.4  327.58  5395.4  331.93
  5594.9  332.63  5776.2  335.16  5854.5  334.84    5977  337.61  6035.1  340.64
  6067.8  339.92  6151.7  342.41  6209.7  342.83  6256.3  344.85  6651.9  350.67
#Mann= 5 ,-1 , 0
  3458.1     .05       0  4950.8     .16       0  4996.8     .07       0
  5002.8     .16       0  5270.4     .05       0
Bank Sta=4964,5014.6
XS Rating Curve= 0 ,0
Exp/Cntr=0.3,0.1

Type RM Length L Ch R = 1 ,156759  ,915,915,915
BEGIN DESCRIPTION:
WICKSON CREEK 101.0
END DESCRIPTION:
XS GIS Cut Line= 3
       3542392.1     10275591.64      3541592.11     10275041.64
      3540792.13     10274341.67
#Sta/Elev= 30
    4027  343.03  4192.8  336.89  4378.9  332.35  4530.3  330.84  4616.9  328.68
  4765.3   327.9  4826.4  327.92  4897.7  326.83  4918.7  324.17  4939.6  324.27
  4948.5  325.31  4975.5  325.03  4991.8  322.68  4994.5  322.18  4997.8  322.68
  5019.2  325.38  5046.9  325.41  5054.3  325.64  5076.1  329.28  5082.8  329.45
  5295.4  329.89  5458.6  332.91  5571.6  332.66  5784.2  336.27  5826.9  338.52
  5855.4   337.6  5883.8   339.6  5990.1   341.1  6032.8  343.33  6060.8  343.87
#Mann= 6 ,-1 , 0
    4027     .05       0  4765.3      .1       0  4826.4     .16       0
  4991.8     .07       0  4997.8     .16       0  5046.9     .05       0
Bank Sta=4975.5,5019.2
XS Rating Curve= 0 ,0
Exp/Cntr=0.3,0.1

Type RM Length L Ch R = 1 ,155844  ,708,708,708
BEGIN DESCRIPTION:
WICKSON CREEK 99.0
END DESCRIPTION:
XS GIS Cut Line= 2
      3542931.29      10275402.3      3540918.41     10273805.88
#Sta/Elev= 30
  3405.3  336.29  3526.3   336.7  3931.7  334.65  4173.6   335.2  4237.7  334.42
  4330.6  329.87  4611.9  327.91  4657.5  326.68  4741.5  326.82  4942.7  324.07
    4978  324.61  4996.7  320.95  4999.4  320.45  5002.7  320.95  5006.8  323.04
  5013.2  323.17  5021.3   324.8  5070.4  327.49  5362.5  331.92  5397.8  333.06
  5420.2  335.82  5455.5  334.04  5469.9  335.92  5668.6  338.66  5697.4  340.37
  5718.2  339.56  5753.5  341.07  5825.6  341.37  5939.4  344.52  5974.4  344.52
#Mann= 6 ,-1 , 0
  3405.3     .05       0  4611.9      .1       0  4741.5     .16       0
  4996.7     .07       0  5002.7     .16       0  5070.4     .05       0
Bank Sta=4978,5021.3
XS Rating Curve= 0 ,0
Exp/Cntr=0.3,0.1

Type RM Length L Ch R = 1 ,155136  ,1390,1390,1390
BEGIN DESCRIPTION:
WICKSON CREEK 98.0
END DESCRIPTION:
XS GIS Cut Line= 3
      3543692.11     10275541.64       3541843.7     10273832.45
       3540982.6     10273603.29
#Sta/Elev= 30
    3035  337.61  3827.4  333.19  4273.6  331.91  4605.9  332.43  4782.8  331.12
  4931.4  328.11  4947.6  325.95  4981.2  323.16  4999.2  320.03    5002  319.53
  5005.2  320.03  5023.5  323.27  5227.1  325.51  5441.1  326.74  5469.4  325.49
  5476.2  326.56  5483.6  325.06  5497.8  324.77  5564.5  324.93  5585.2  328.69
  5612.6  325.55  5637.9   325.8    5668  326.96  5692.8  325.67  5713.8  327.16
  5823.2  333.39    5875  338.37    5906  336.36  5928.5  337.65  6443.6  344.99
#Mann= 8 ,-1 , 0
    3035     .05       0  4947.6     .16       0  4999.2     .07       0
  5005.2     .16       0  5227.1     .05       0  5612.6      .1       0
  5637.9     .16       0  5713.8     .05       0
Bank Sta=4931.4,5023.5
XS Rating Curve= 0 ,0
Exp/Cntr=0.3,0.1

Type RM Length L Ch R = 1 ,153746  ,1132,1132,1132
BEGIN DESCRIPTION:
Mapping XS f7e3e313
END DESCRIPTION:
XS GIS Cut Line= 3
      3543569.29     10274430.89      3541837.56     10273144.46
      3541360.95     10273079.35
#Sta/Elev= 30
  3144.1  331.14  3591.3  330.84  3756.1  332.33  4099.8   332.6  4463.3  328.96
  4571.8  326.93  4670.2  323.62  4677.4  323.59  4713.6  325.64  4757.4  326.26
  4957.7  324.25  4984.8  320.33  4996.4  317.76  4999.2  317.26  5002.4  317.76
    5014  322.69  5028.6  323.27  5071.5  322.07  5101.2  323.19    5135  322.41
  5170.6  323.58  5243.5  330.09  5285.2  332.31  5355.7  337.46  5367.4  336.88
  5438.1  340.11  5549.1  342.47    5718  343.88  5760.8  344.36  5782.4  344.71
#Mann= 9 ,-1 , 0
  3144.1     .05       0  4670.2     .16       0  4677.4     .05       0
  4996.4    .035       0  5002.4     .05       0  5101.2      .1       0
  5170.6     .05       0    5718      .1       0  5760.8     .05       0
Bank Sta=4957.7,5014
XS Rating Curve= 0 ,0
Exp/Cntr=0.3,0.1