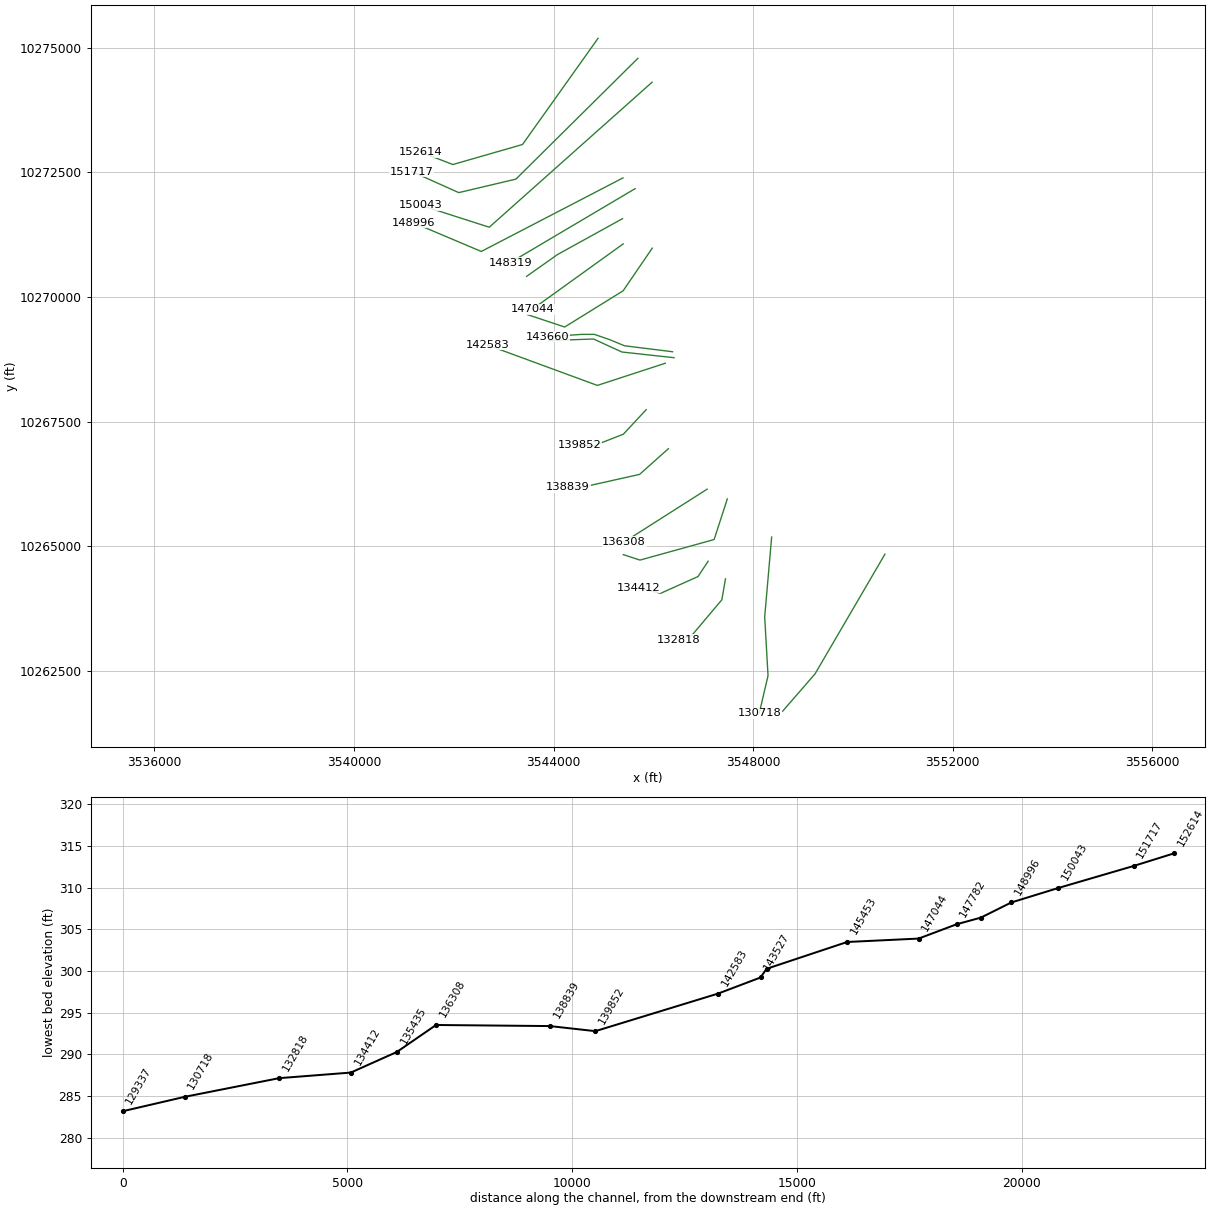
HEC-RAS study WICKSON CREEK.prj: WICKSON CREEK Base Level Engineering

--- WICKSON CREEK.g01 (geometry) --- (continued)

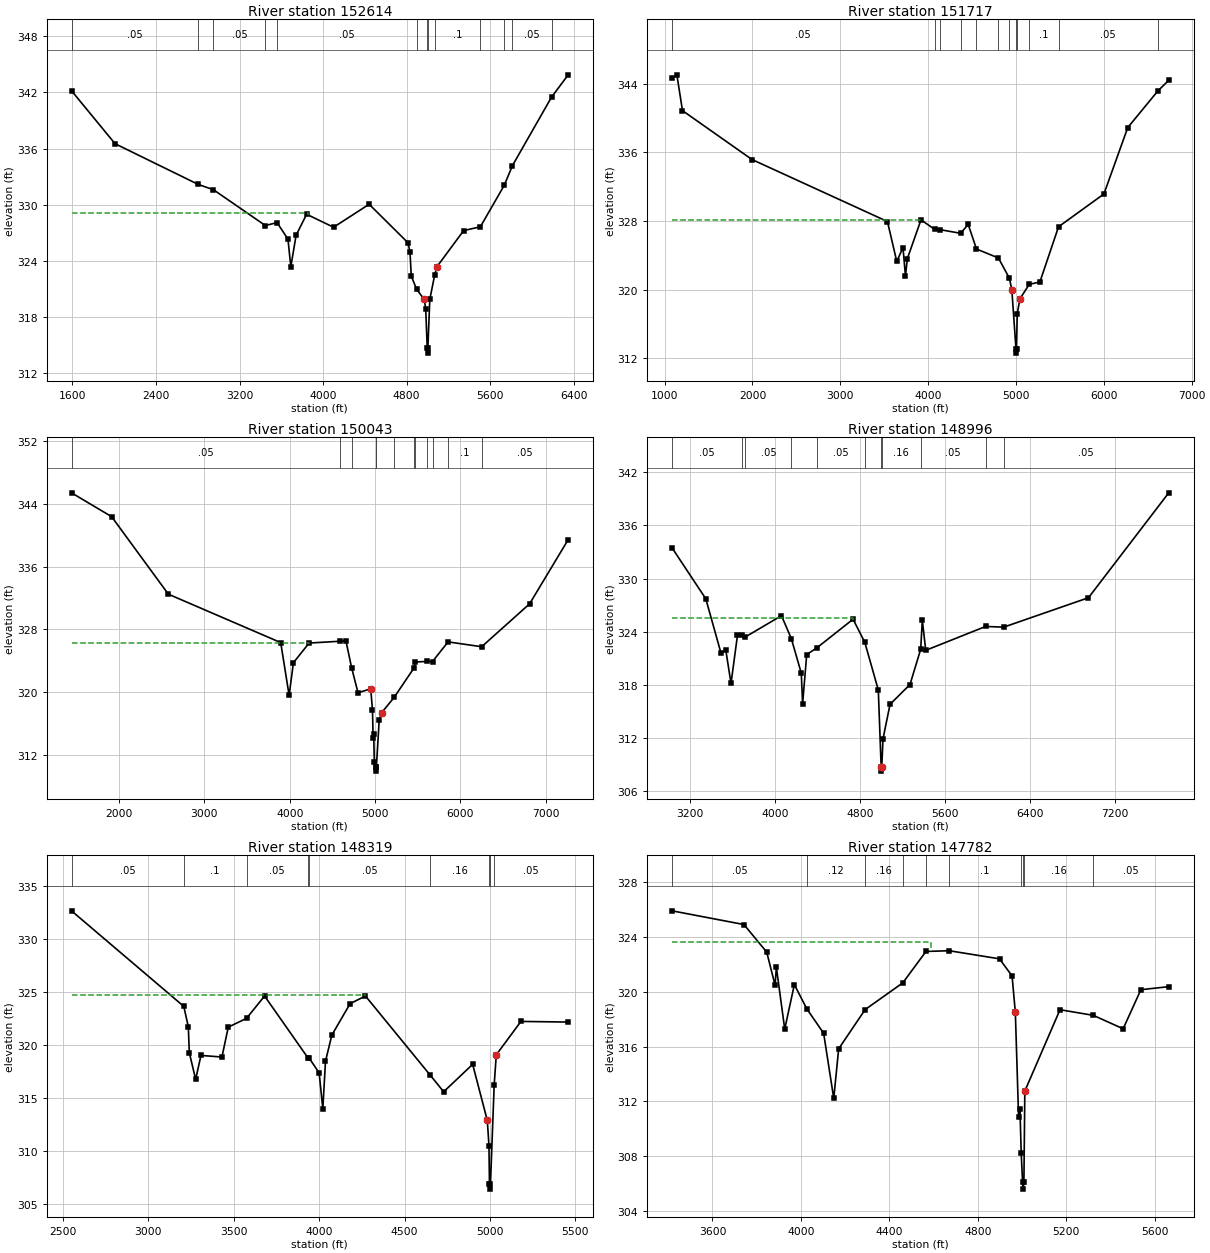
Type RM Length L Ch R = 1 ,152614  ,897,897,897
BEGIN DESCRIPTION:
WICKSON CREEK 96.0
END DESCRIPTION:
XS GIS Cut Line= 4
      3544892.12     10275191.67      3543378.42     10273061.62
      3541982.24     10272660.06      3541336.91     10272908.78
#Sta/Elev= 30
  1590.5  342.19  2007.5  336.52  2803.2  332.17  2950.6  331.59  3448.1  327.76
    3559  328.08  3663.8  326.31  3691.2  323.35  3741.7  326.72  3842.5  328.97
  4100.8  327.58  4441.5  330.04  4813.7  325.92    4833   324.9  4844.9  322.36
  4897.2  320.92  4969.8  319.85  4983.4  318.79    4998  314.61  5000.8  314.11
    5004  314.61  5022.3  319.85  5068.6  322.44  5089.7  323.34  5346.4  327.22
  5506.8  327.63  5735.3  332.06  5813.8  334.17  6188.4   341.5    6348  343.89
#Mann= 13 ,-1 , 0
  1590.5     .05       0  2803.2      .1       0  2950.6     .05       0
  3448.1      .1       0    3559     .05       0  4897.2     .16       0
    4998     .07       0    5004     .16       0  5068.6      .1       0
  5506.8     .05       0  5735.3      .1       0  5813.8     .05       0
  6188.4      .1       0
#XS Ineff= 2 , 0
         3856.82  329.06
Permanent Ineff=
       F       F
Bank Sta=4969.8,5089.7
XS Rating Curve= 0 ,0
Exp/Cntr=0.3,0.1

Type RM Length L Ch R = 1 ,151717  ,1674,1674,1674
BEGIN DESCRIPTION:
WICKSON CREEK 95.0
END DESCRIPTION:
XS GIS Cut Line= 4
      3545690.91     10274790.78      3543246.48     10272367.18
      3542100.64     10272096.34      3541156.61     10272519.77
#Sta/Elev= 30
  1084.6  344.65  1139.7  345.02  1203.4  340.85  1995.3  335.15  3536.8  327.93
  3642.9  323.28  3713.6   324.9  3741.9  321.59  3763.1   323.6  3918.7  328.13
  4073.2  327.02  4132.2  326.99  4369.4  326.56  4456.1  327.59  4550.3  324.73
  4800.3  323.68  4925.1  321.32  4952.6  319.99  5000.1   313.1  5002.9   312.6
  5006.1   313.1  5014.3   317.2  5045.1  318.93    5151  320.61  5272.3  320.89
  5484.5  327.32  6001.1  331.14  6272.6  338.88  6616.7  343.16  6738.9  344.38
#Mann= 12 ,-1 , 0
  1084.6     .05       0  4073.2      .1       0  4132.2     .05       0
  4369.4      .1       0  4550.3     .16       0  4800.3      .1       0
  4925.1     .16       0  5000.1     .07       0  5006.1     .16       0
    5151      .1       0  5484.5     .05       0  6616.7      .1       0
#XS Ineff= 2 , 0
         3928.41  328.07
Permanent Ineff=
       F       F
Bank Sta=4952.6,5045.1
XS Rating Curve= 0 ,0
Exp/Cntr=0.3,0.1

Type RM Length L Ch R = 1 ,150043  ,1047,1047,1047
BEGIN DESCRIPTION:
WICKSON CREEK 93.0
END DESCRIPTION:
XS GIS Cut Line= 3
      3545975.66     10274311.64      3542711.75      10271401.9
      3541329.77     10271846.35
#Sta/Elev= 30
  1441.4  345.38  1911.6  342.35  2577.1  332.48  3894.7  326.32  3993.4   319.6
  4043.6  323.76  4227.5  326.26  4588.6  326.49  4659.7  326.53  4725.6  323.14
  4801.1  319.94  4949.9  320.43  4970.8  317.76  4978.3   314.2    4985  314.64
  4992.5  311.06  5010.4  310.46  5013.2  309.96  5016.4  310.46  5049.4  316.41
    5077  317.37  5227.6  319.39  5460.6  323.14  5473.5  323.85    5611  323.92
  5674.6  323.91  5857.2  326.41    6251  325.79  6813.1  331.25  7265.7  339.42
#Mann= 12 ,-1 , 0
  1441.4     .05       0  4588.6      .1       0  4725.6     .16       0
  5010.4     .07       0  5016.4     .16       0  5227.6     .05       0
  5460.6      .1       0  5473.5     .05       0    5611      .1       0
  5674.6     .05       0  5857.2      .1       0    6251     .05       0
#XS Ineff= 2 , 0
         4221.59  326.29
Permanent Ineff=
       F       F
Bank Sta=4949.9,5077
XS Rating Curve= 0 ,0
Exp/Cntr=0.3,0.1

Type RM Length L Ch R = 1 ,148996  ,677,677,677
BEGIN DESCRIPTION:
WICKSON CREEK 92.0
END DESCRIPTION:
XS GIS Cut Line= 3
      3545392.09     10272391.63      3542552.03     10270915.79
      3541192.07     10271491.66
#Sta/Elev= 30
  3028.1  333.47  3345.9  327.71  3489.4  321.55  3533.6  321.97  3583.5  318.14
  3644.2  323.57    3689  323.62  3718.1  323.39  4058.7   325.8  4151.6   323.2
  4245.2   319.3  4257.7  315.83  4296.3   321.4  4392.9  322.17    4733   325.4
  4843.8  322.77  4970.6  317.39  4997.3  308.72    5000  308.22  5003.3  308.72
  5014.8  311.86  5081.1  315.78  5268.9  318.01  5369.7     322  5385.1  325.29
  5417.2  321.88  5981.4  324.58  6151.1   324.5  6949.9  327.83  7705.6  339.69
#Mann= 11 ,-1 , 0
  3028.1     .05       0    3689      .1       0  3718.1     .05       0
  4151.6     .16       0  4392.9     .05       0  4843.8     .16       0
  4997.3     .07       0  5003.3     .16       0  5369.7     .05       0
  5981.4      .1       0  6151.1     .05       0
#XS Ineff= 2 , 0
          4735.8   325.5
Permanent Ineff=
       F       F
Bank Sta=4997.3,5003.3
XS Rating Curve= 0 ,0
Exp/Cntr=0.3,0.1

Type RM Length L Ch R = 1 ,148319  ,537,537,537
BEGIN DESCRIPTION:
Mapping XS 09543423
END DESCRIPTION:
XS GIS Cut Line= 2
      3545635.16     10272175.55      3543132.96     10270693.26
#Sta/Elev= 30
  2549.9  332.67  3207.4  323.65  3233.9  321.73  3239.7  319.29  3276.8  316.76
    3308  319.02  3430.8  318.87  3467.9  321.69  3574.7  322.52  3680.4  324.63
    3933  318.82  3940.4   318.8  4000.1  317.36  4021.5  313.96  4037.1  318.47
  4074.2  320.94  4181.4  323.91  4271.1  324.63  4651.2  317.14  4729.2  315.59
  4898.8  318.18  4984.6  312.88  4994.3  310.51  4997.2   306.9  4999.9   306.4
  5003.2   306.9  5024.8  316.22  5037.2  319.08  5181.5  322.23  5458.2  322.17
#Mann= 9 ,-1 , 0
  2549.9     .05       0  3207.4      .1       0  3574.7     .05       0
    3933     .16       0  3940.4     .05       0  4651.2     .16       0
  4997.2     .07       0  5003.2     .16       0  5024.8     .05       0
#XS Ineff= 2 , 0
         4271.02  324.71
Permanent Ineff=
       F       F
Bank Sta=4984.6,5037.2
XS Rating Curve= 0 ,0
Exp/Cntr=0.3,0.1

Type RM Length L Ch R = 1 ,147782  ,846,846,846
BEGIN DESCRIPTION:
Mapping XS e02ddf3c
END DESCRIPTION:
XS GIS Cut Line= 3
       3545382.1      10271573.7      3544080.27     10270854.04
      3543460.63     10270416.41
#Sta/Elev= 30
  3417.3   325.9  3742.4   324.9  3845.5  322.89  3883.3  320.47    3889  321.79
  3926.9  317.28  3970.4  320.52  4026.9  318.75  4102.9  316.97  4148.6  312.22
  4170.8  315.84  4290.5   318.7  4460.9  320.65  4565.7  322.94  4670.8  322.99
  4898.2   322.4    4955  321.15  4969.8  318.49  4984.5  310.84  4990.7  311.42
  4996.3  308.24  5002.5  306.11  5005.2  305.61  5008.5  306.11  5012.7  312.76
  5171.7  318.69  5322.3  318.28  5457.3   317.3  5537.4  320.15  5663.4  320.37
#Mann= 10 ,-1 , 0
  3417.3     .05       0  4026.9     .12       0  4290.5     .16       0
  4460.9      .1       0  4565.7     .05       0  4670.8      .1       0
  4996.3     .16       0  5002.5     .07       0  5008.5     .16       0
  5322.3     .05       0
#XS Ineff= 2 , 0
         4588.64  323.65
Permanent Ineff=
       F       F
Bank Sta=4969.8,5012.7
XS Rating Curve= 0 ,0
Exp/Cntr=0.3,0.1

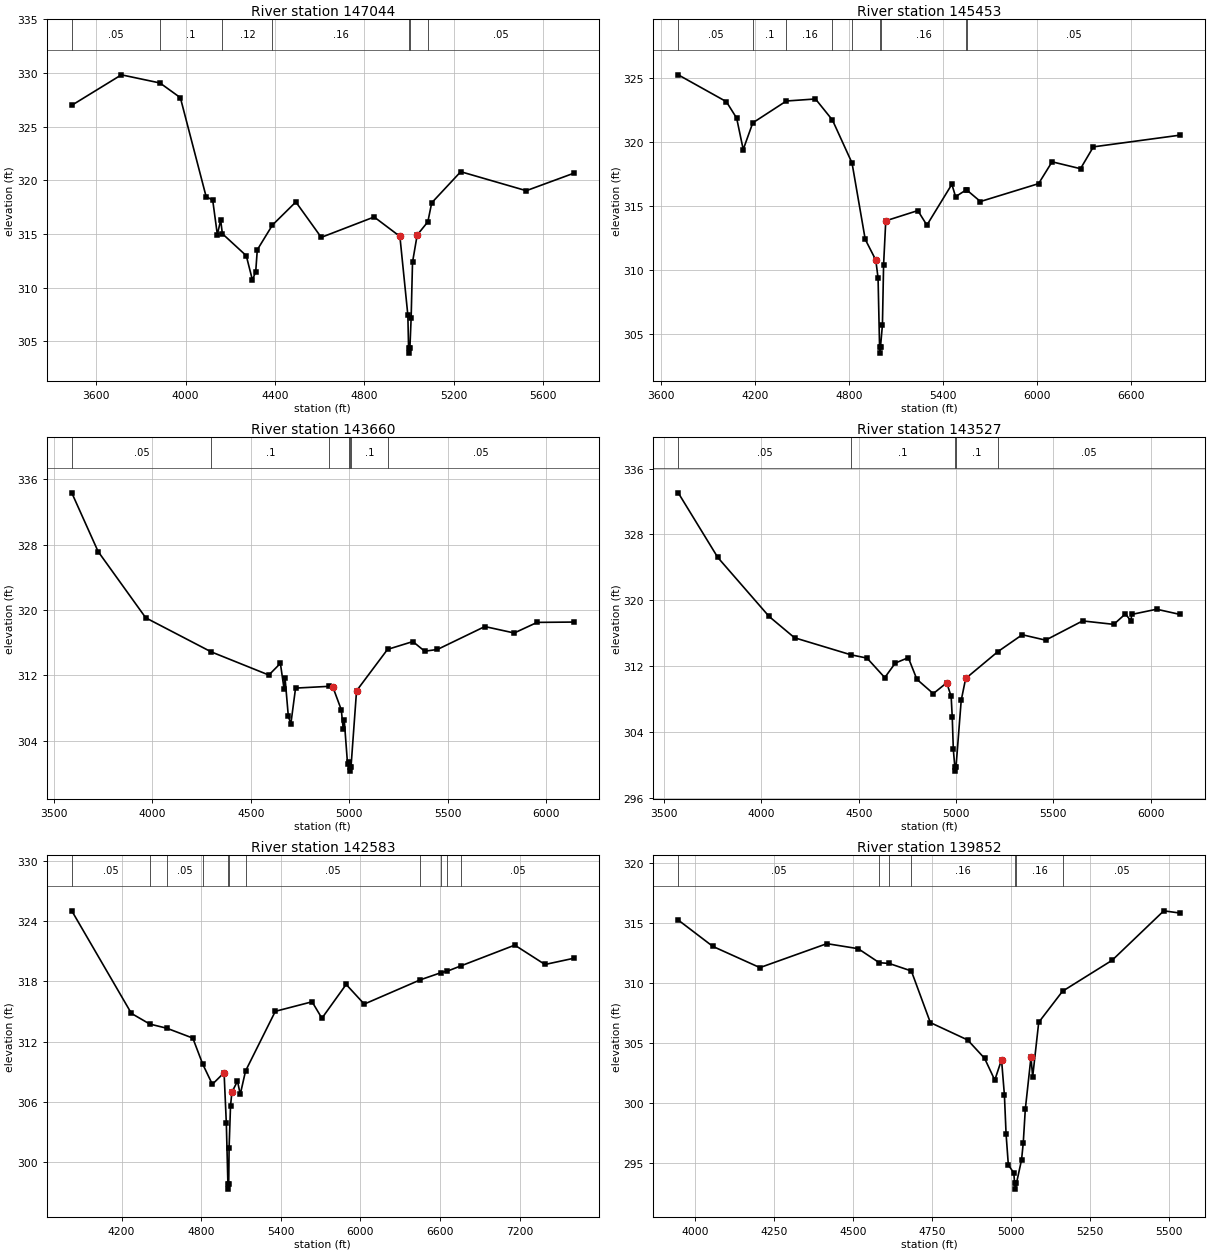
Type RM Length L Ch R = 1 ,147044  ,1591,1591,1591
BEGIN DESCRIPTION:
Mapping XS 1dce0ea9
END DESCRIPTION:
XS GIS Cut Line= 2
      3545396.02     10271067.66      3543572.25     10269753.54
#Sta/Elev= 30
  3490.4  326.99  3712.7  329.83  3885.3  329.07  3976.6   327.7  4091.9  318.48
  4121.4  318.15  4142.2  314.93    4157  316.29  4164.7  315.02  4271.7  312.97
  4299.3   310.7    4314  311.49    4321  313.52  4388.9  315.83  4493.6  317.98
  4607.4  314.68  4844.2  316.58  4959.5  314.77  4995.1  307.43  4998.3  304.39
    5001  303.89  5004.3  304.39  5009.8  307.14    5016  312.36  5036.9   314.9
  5084.6  316.13  5101.9   317.9  5231.9   320.8  5525.3  319.03  5738.3  320.66
#Mann= 7 ,-1 , 0
  3490.4     .05       0  3885.3      .1       0  4164.7     .12       0
  4388.9     .16       0  4998.3     .07       0  5004.3     .16       0
  5084.6     .05       0
Bank Sta=4959.5,5036.9
XS Rating Curve= 0 ,0
Exp/Cntr=0.3,0.1

Type RM Length L Ch R = 1 ,145453  ,1793,1793,1793
BEGIN DESCRIPTION:
WICKSON CREEK 91.0
END DESCRIPTION:
XS GIS Cut Line= 4
      3545978.63     10270982.05      3545395.47     10270126.72
       3544223.6     10269399.73      3543476.01     10269648.92
#Sta/Elev= 30
  3711.3  325.27  4018.1  323.17  4083.9  321.88  4125.8  319.42  4186.7  321.51
    4401  323.22  4586.6  323.38  4694.8  321.73  4819.7  318.37  4903.9  312.39
  4971.2  310.77  4985.8  309.37  4995.4  303.98  4998.1  303.48  5001.4  303.98
  5013.7  305.69  5021.1  310.41    5035  313.84  5239.4  314.64  5297.2   313.5
  5456.6   316.7  5480.1  315.73  5549.2  316.27  5549.9  316.27  5638.6  315.35
  6009.6  316.75  6095.7  318.46    6277  317.92    6359  319.63  6913.6  320.55
#Mann= 9 ,-1 , 0
  3711.3     .05       0  4186.7      .1       0    4401     .16       0
  4694.8      .1       0  4819.7     .16       0  4995.4     .07       0
  5001.4     .16       0  5549.2      .1       0  5549.9     .05       0
Bank Sta=4971.2,5035
XS Rating Curve= 0 ,0
Exp/Cntr=0.3,0.1

Type RM Length L Ch R = 1 ,143660  ,133,133,133
BEGIN DESCRIPTION:
WICKSON CREEK 90.0
END DESCRIPTION:
XS GIS Cut Line= 6
      3546384.93     10268903.96      3545421.36     10269023.76
      3545119.28     10269148.76      3544817.19     10269252.92
      3544577.61     10269252.92      3543886.03     10269206.13
#Sta/Elev= 30
  3591.2  334.35    3725  327.16  3966.9  319.04  4299.3  314.87  4592.2  312.03
  4650.8  313.46  4669.3  310.37  4674.7  311.61  4691.2  306.97    4704  306.05
  4727.9  310.43  4900.1  310.65  4918.2  310.51  4960.2  307.77  4970.1  305.39
  4975.3  306.47  4991.9  301.15    5001  301.33  5003.5  300.76  5006.3  300.26
  5009.5  300.76  5037.7   310.1    5195  315.17  5323.7  316.13  5383.7  314.95
  5448.2  315.16  5689.3  317.97  5838.6  317.18  5954.9  318.48  6141.4  318.52
#Mann= 7 ,-1 , 0
  3591.2     .05       0  4299.3      .1       0  4900.1     .16       0
    5001      .1       0  5003.5     .07       0  5009.5      .1       0
    5195     .05       0
Bank Sta=4918.2,5037.7
XS Rating Curve= 0 ,0
Exp/Cntr=0.3,0.1

Type RM Length L Ch R = 1 ,143527  ,944,944,944
BEGIN DESCRIPTION:
Mapping XS f6fca8eb
END DESCRIPTION:
XS GIS Cut Line= 4
      3546416.12     10268784.18      3545369.28     10268898.76
      3544801.57     10269159.17      3543900.49     10269127.92
#Sta/Elev= 30
  3572.5  333.05  3775.8  325.19  4039.3  318.02  4170.1  315.43  4459.8  313.36
  4542.3  312.96  4633.5  310.59  4687.7  312.36  4754.5  313.01  4798.5  310.38
  4882.7  308.64  4951.7  309.96  4974.5  308.31  4980.2  305.77  4985.7  301.85
  4993.5  299.72  4996.3  299.22  4999.5  299.72  5026.2  307.82  5049.1  310.48
  5214.3  313.74  5339.7   315.8  5459.8  315.14  5649.9  317.48    5810  317.06
    5870  318.34  5897.6  317.48  5902.6  318.27  6030.1   318.9  6151.8  318.26
#Mann= 5 ,-1 , 0
  3572.5     .05       0  4459.8      .1       0  4993.5     .07       0
  4999.5      .1       0  5214.3     .05       0
Bank Sta=4951.7,5049.1
XS Rating Curve= 0 ,0
Exp/Cntr=0.3,0.1

Type RM Length L Ch R = 1 ,142583  ,2731,2731,2731
BEGIN DESCRIPTION:
WICKSON CREEK 88.0
END DESCRIPTION:
XS GIS Cut Line= 3
      3546239.58     10268672.75      3544878.42     10268228.29
      3542670.13     10269040.77
#Sta/Elev= 30
  3824.2  325.04  4273.9  314.81  4412.2  313.75  4541.6  313.33  4736.7  312.35
  4810.5  309.78    4884  307.74  4972.4   308.9  4989.2   303.9  5001.3  297.79
  5004.1  297.29  5007.3  297.79  5010.3  301.44  5020.8  305.54    5031  306.94
  5073.4  308.06  5094.4  306.74  5134.2  309.07  5358.7  315.02  5635.8  315.97
  5709.9  314.33  5892.6   317.7    6029  315.74  6451.6  318.16  6611.2  318.89
  6652.8  319.01  6759.6  319.56  7163.8  321.62  7391.5  319.69  7609.1  320.31
#Mann= 11 ,-1 , 0
  3824.2     .05       0  4412.2      .1       0  4541.6     .05       0
  4810.5     .16       0  5001.3     .07       0  5007.3     .16       0
  5134.2     .05       0  6451.6      .1       0  6611.2     .05       0
  6652.8      .1       0  6759.6     .05       0
Bank Sta=4972.4,5031
XS Rating Curve= 0 ,0
Exp/Cntr=0.3,0.1

Type RM Length L Ch R = 1 ,139852  ,1013,1013,1013
BEGIN DESCRIPTION:
WICKSON CREEK 87.0
END DESCRIPTION:
XS GIS Cut Line= 4
      3545857.36     10267741.58      3545399.25     10267249.12
      3544795.09     10267013.01      3544526.98      10267030.1
#Sta/Elev= 30
  3947.2  315.24  4056.8  313.04  4205.8  311.27  4417.9  313.27    4517  312.85
  4583.8  311.68  4614.7  311.62  4685.4  310.99  4745.6  306.68  4863.7  305.23
  4917.3   303.7  4949.6  301.88    4971  303.58  4980.1  300.62  4985.4  297.36
  4992.5  294.81  5009.9  294.12  5012.3  293.28    5015  292.78  5018.3  293.28
  5034.4  295.23  5039.8  296.66  5046.2  299.43  5064.2  303.79  5069.6  302.16
  5088.7   306.7  5164.2   309.3  5321.1  311.88  5484.8  316.01  5537.1  315.82
#Mann= 7 ,-1 , 0
  3947.2     .05       0  4583.8     .16       0  4614.7     .05       0
  4685.4     .16       0  5012.3     .07       0  5018.3     .16       0
  5164.2     .05       0
Bank Sta=4971,5064.2
XS Rating Curve= 0 ,0
Exp/Cntr=0.3,0.1

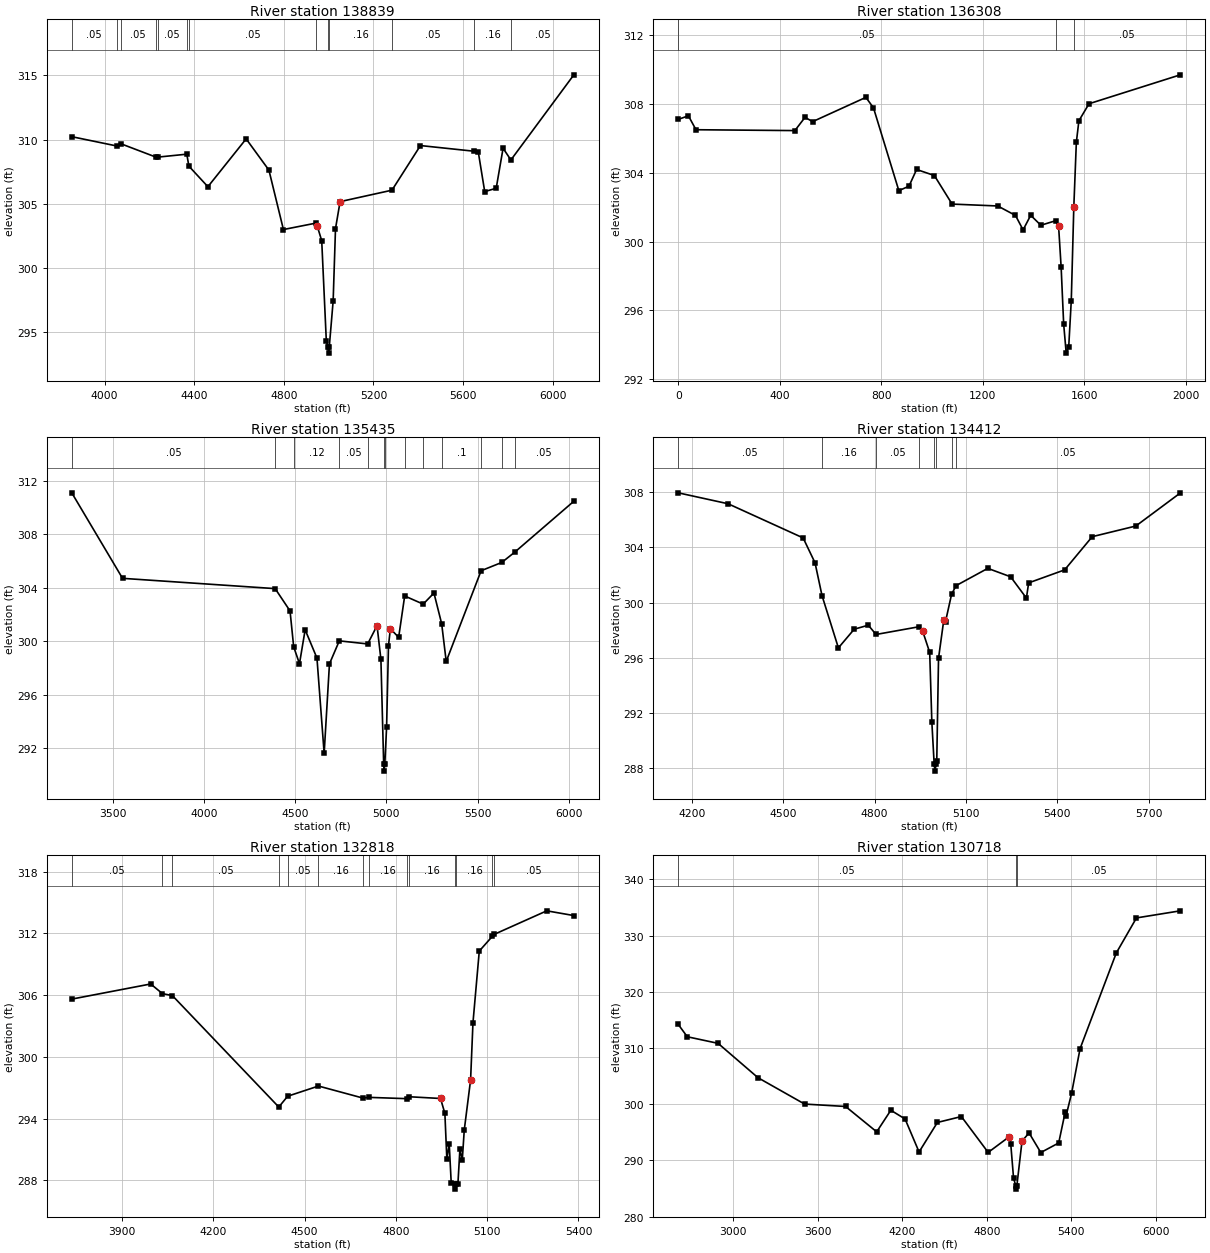
Type RM Length L Ch R = 1 ,138839  ,2531,2531,2531
BEGIN DESCRIPTION:
WICKSON CREEK 86.0
END DESCRIPTION:
XS GIS Cut Line= 4
      3546302.84     10266959.28      3545725.64     10266443.56
      3544454.81     10266158.84      3544292.72     10266189.34
#Sta/Elev= 30
  3853.3  310.22  4053.5   309.5  4072.6  309.67  4227.8  308.64  4236.7  308.63
  4366.8  308.86  4376.1  307.93    4461  306.33  4631.7  310.05  4733.4  307.62
  4798.1     303  4943.3   303.5  4948.6   303.3  4969.1  302.13  4989.6  294.34
  4996.9  293.89  4999.6  293.39  5002.9  293.89  5020.1  297.44  5030.6  303.07
  5051.1  305.17  5282.7  306.06  5409.8  309.53  5648.6  309.09  5668.2  309.01
  5696.7  305.95    5748  306.21  5778.7  309.32  5813.6  308.41  6094.6  315.03
#Mann= 13 ,-1 , 0
  3853.3     .05       0  4053.5      .1       0  4072.6     .05       0
  4227.8      .1       0  4236.7     .05       0  4366.8      .1       0
  4376.1     .05       0  4943.3     .16       0  4996.9     .07       0
  5002.9     .16       0  5282.7     .05       0  5648.6     .16       0
  5813.6     .05       0
Bank Sta=4948.6,5051.1
XS Rating Curve= 0 ,0
Exp/Cntr=0.3,0.1

Type RM Length L Ch R = 1 ,136308  ,873,873,873
XS GIS Cut Line= 2
      3547078.24    10266146.389     3545414.177    10265086.493
#Sta/Elev= 30
       0   307.1   39.96  307.31   69.93   306.5  459.52  306.45  499.48  307.22
  529.45  306.97  739.23  308.38   769.2  307.77  869.09  302.96  909.05  303.22
  939.02  304.19 1008.95  303.84 1078.87  302.18 1258.69  302.07 1328.61  301.52
 1358.58  300.68 1388.55  301.53 1428.51  300.95 1488.45  301.22 1498.44  300.89
 1508.42  298.52 1518.41  295.21  1528.4  293.52 1538.39   293.9 1548.38  296.57
 1558.37  302.01 1568.36  305.77 1578.35  307.02 1618.31  308.01 1977.93  309.69
#Mann= 3 ,-1 , 0
       0     .05       0 1488.45     .07       0 1558.37     .05       0
Bank Sta=1498.44,1558.37
XS Rating Curve= 0 ,0
Exp/Cntr=0.3,0.1

Type RM Length L Ch R = 1 ,135435  ,1023,1023,1023
BEGIN DESCRIPTION:
WICKSON CREEK 84.0
END DESCRIPTION:
XS GIS Cut Line= 4
      3547483.05     10265950.71       3547219.1     10265136.06
      3545732.56     10264723.73      3545398.17     10264833.32
#Sta/Elev= 30
  3276.4  311.11  3554.6  304.71  4390.8  303.94  4472.3  302.27  4492.2  299.59
    4524  298.32  4555.1  300.86  4619.8  298.74  4659.2  291.61  4688.3  298.31
  4742.2  300.03  4897.7   299.8    4949  301.17  4970.2  298.64  4985.4  290.78
  4988.2  290.28  4991.4  290.78  5001.3  293.55  5011.7  299.67  5022.1  300.94
  5067.4  300.29  5100.4  303.39  5201.8  302.78  5260.8  303.61  5303.1  301.31
    5328  298.49  5519.2  305.28  5632.5   305.9  5703.6  306.67  6027.3  310.48
#Mann= 13 ,-1 , 0
  3276.4     .05       0  4390.8     .16       0  4492.2     .12       0
  4742.2     .05       0  4897.7     .16       0  4985.4     .07       0
  4991.4     .16       0  5100.4      .1       0  5201.8     .05       0
  5303.1      .1       0  5519.2     .05       0  5632.5      .1       0
  5703.6     .05       0
Bank Sta=4949,5022.1
XS Rating Curve= 0 ,0
Exp/Cntr=0.3,0.1

Type RM Length L Ch R = 1 ,134412  ,1594,1594,1594
BEGIN DESCRIPTION:
Mapping XS 6d187f69
END DESCRIPTION:
XS GIS Cut Line= 4
      3547098.86     10264700.89      3546896.22     10264393.65
      3546147.52     10264057.28      3545701.93     10264172.16
#Sta/Elev= 30
  4154.8  307.93  4318.5  307.14    4565  304.67  4604.1  302.87    4627   300.5
  4680.8  296.72  4732.7  298.07    4779  298.36  4804.5  297.69  4946.1  298.25
  4957.6  297.93  4980.7  296.39  4987.8  291.33  4995.4  288.31  4998.2  287.81
  5001.4  288.31  5003.9  288.56  5009.7  295.97  5027.1  298.76  5032.6  298.62
  5052.5  300.59  5067.3  301.22  5171.5  302.47  5246.5  301.86  5298.3  300.32
  5305.7  301.42  5423.9  302.36  5514.5  304.76  5657.7  305.53  5803.8  307.92
#Mann= 8 ,-1 , 0
  4154.8     .05       0    4627     .16       0  4804.5     .05       0
  4946.1     .12       0  4995.4     .07       0  5001.4     .12       0
  5052.5     .16       0  5067.3     .05       0
Bank Sta=4957.6,5027.1
XS Rating Curve= 0 ,0
Exp/Cntr=0.3,0.1

Type RM Length L Ch R = 1 ,132818  ,2100,2100,2100
BEGIN DESCRIPTION:
WICKSON CREEK 83.0
END DESCRIPTION:
XS GIS Cut Line= 4
      3547446.76     10264347.15      3547373.65     10263927.07
       3546765.2     10263205.62      3546496.86     10263125.53
#Sta/Elev= 30
  3734.7  305.61  3994.1  307.08  4032.8  306.14  4065.4  305.95  4415.1  295.12
  4444.3  296.17  4545.5  297.16  4691.8  295.99  4710.1  296.06  4838.1  295.93
  4843.1  296.12  4946.7  295.95    4961   294.5  4967.5  290.05  4975.3  291.54
  4981.8  287.77  4993.1  287.64  4995.9  287.14  4999.1  287.64  5003.9  287.66
  5010.4  291.02  5018.2  289.97  5024.7  292.88  5045.5  297.75  5053.3   303.3
  5074.1  310.28    5117  311.71  5122.9   311.9  5295.9  314.19  5384.9  313.73
#Mann= 14 ,-1 , 0
  3734.7     .05       0  4032.8      .1       0  4065.4     .05       0
  4415.1     .16       0  4444.3     .05       0  4545.5     .16       0
  4691.8     .12       0  4710.1     .16       0  4838.1     .12       0
  4843.1     .16       0  4993.1     .07       0  4999.1     .16       0
    5117      .1       0  5122.9     .05       0
Bank Sta=4946.7,5045.5
XS Rating Curve= 0 ,0
Exp/Cntr=0.3,0.1

Type RM Length L Ch R = 1 ,130718  ,1381,1381,1381
BEGIN DESCRIPTION:
WICKSON CREEK 82.0
END DESCRIPTION:
XS GIS Cut Line= 4
      3548371.91     10265185.79      3548232.46     10263585.03
      3548299.37     10262403.75      3548122.34     10261648.42
#Sta/Elev= 30
    2609   314.2  2673.4     312    2892  310.83  3175.3  304.72  3506.5  300.03
  3797.6   299.6  4018.5  295.09  4118.8  298.93    4220  297.38  4319.4  291.51
  4449.6  296.76  4619.9  297.81  4810.2  291.43  4960.4  294.23  4970.4  292.99
  4990.5  286.85  5007.5   285.4  5010.2   284.9  5013.5   285.4  5050.6  293.44
  5100.6   294.9  5183.9  291.41    5311  293.11  5357.5  298.63  5362.5  297.84
  5402.6  301.94  5462.8  309.88  5720.2  326.91  5863.4  333.14  6174.8   334.4
#Mann= 3 ,-1 , 0
    2609     .05       0  5007.5    .035       0  5013.5     .05       0
Bank Sta=4960.4,5050.6
XS Rating Curve= 0 ,0
Exp/Cntr=0.3,0.1

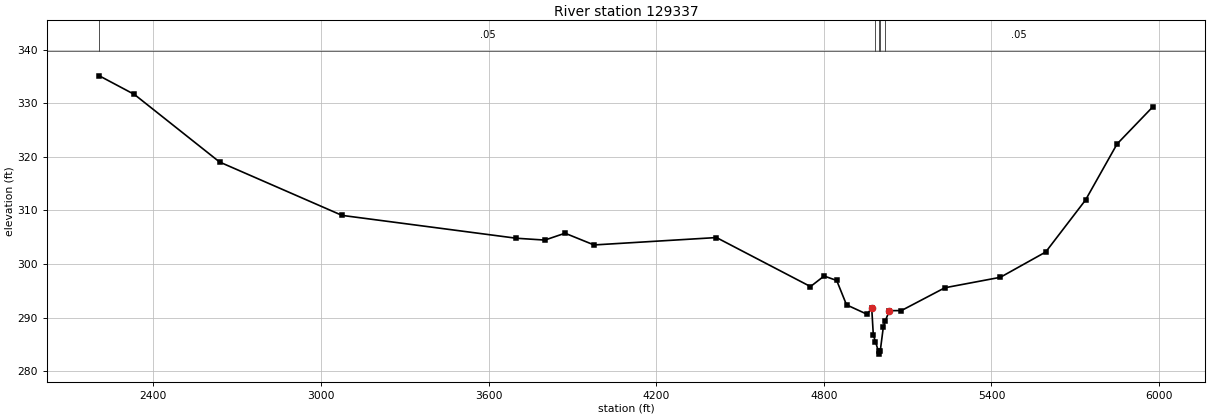
Type RM Length L Ch R = 1 ,129337  ,864,864,864
BEGIN DESCRIPTION:
WICKSON CREEK 81.0
END DESCRIPTION:
XS GIS Cut Line= 3
      3550642.13     10264841.68      3549242.11     10262441.64
      3548592.11     10261691.65
#Sta/Elev= 30
  2206.4  335.12  2331.7  331.65  2636.9  319.03  3075.1  309.07  3699.5   304.8
  3801.2  304.46  3873.5  305.74  3977.3  303.55  4415.6  304.93  4752.2  295.78
  4800.9  297.75    4846  296.92  4881.2  292.37  4955.6  290.59  4971.3  291.86
  4977.1  286.74  4984.7  285.49  4995.7  283.67  4998.4  283.17  5001.7  283.67
  5012.9  288.21  5019.7  289.36  5034.8  291.28  5077.6   291.3  5233.3  295.56
  5431.8  297.51  5594.2  302.23  5736.7  311.93  5849.7   322.4  5977.4  329.32
#Mann= 5 ,-1 , 0
  2206.4     .05       0  4984.7      .1       0  4995.7     .07       0
  5001.7      .1       0  5019.7     .05       0
Bank Sta=4971.3,5034.8
XS Rating Curve= 0 ,0
Exp/Cntr=0.3,0.1