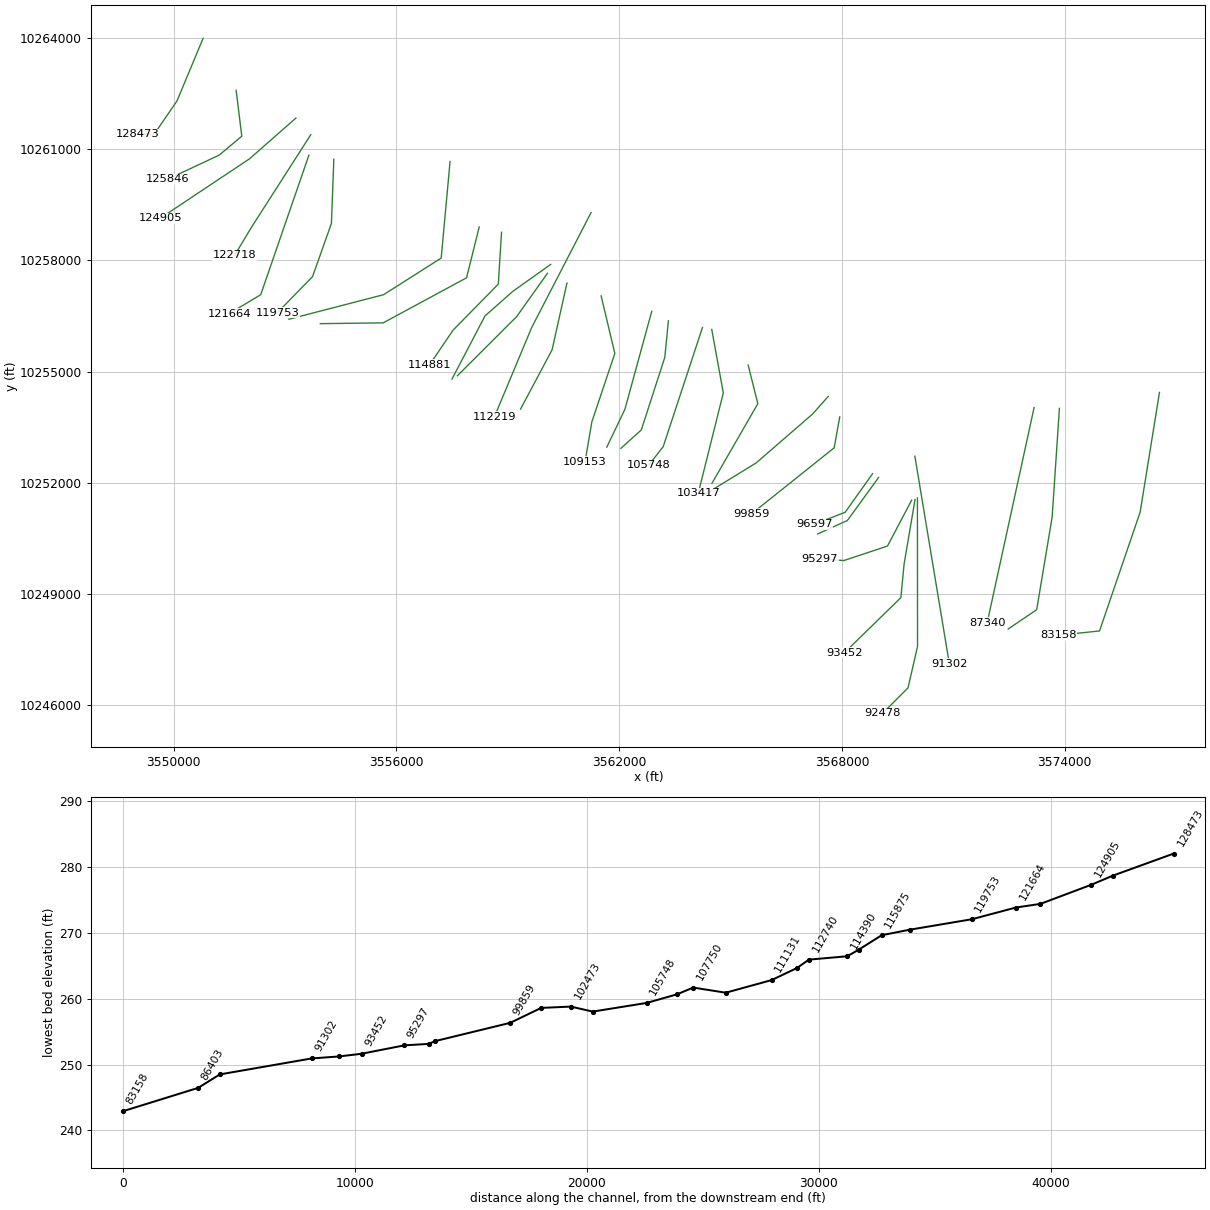
HEC-RAS study WICKSON CREEK.prj: WICKSON CREEK Base Level Engineering

--- WICKSON CREEK.g01 (geometry) --- (continued)

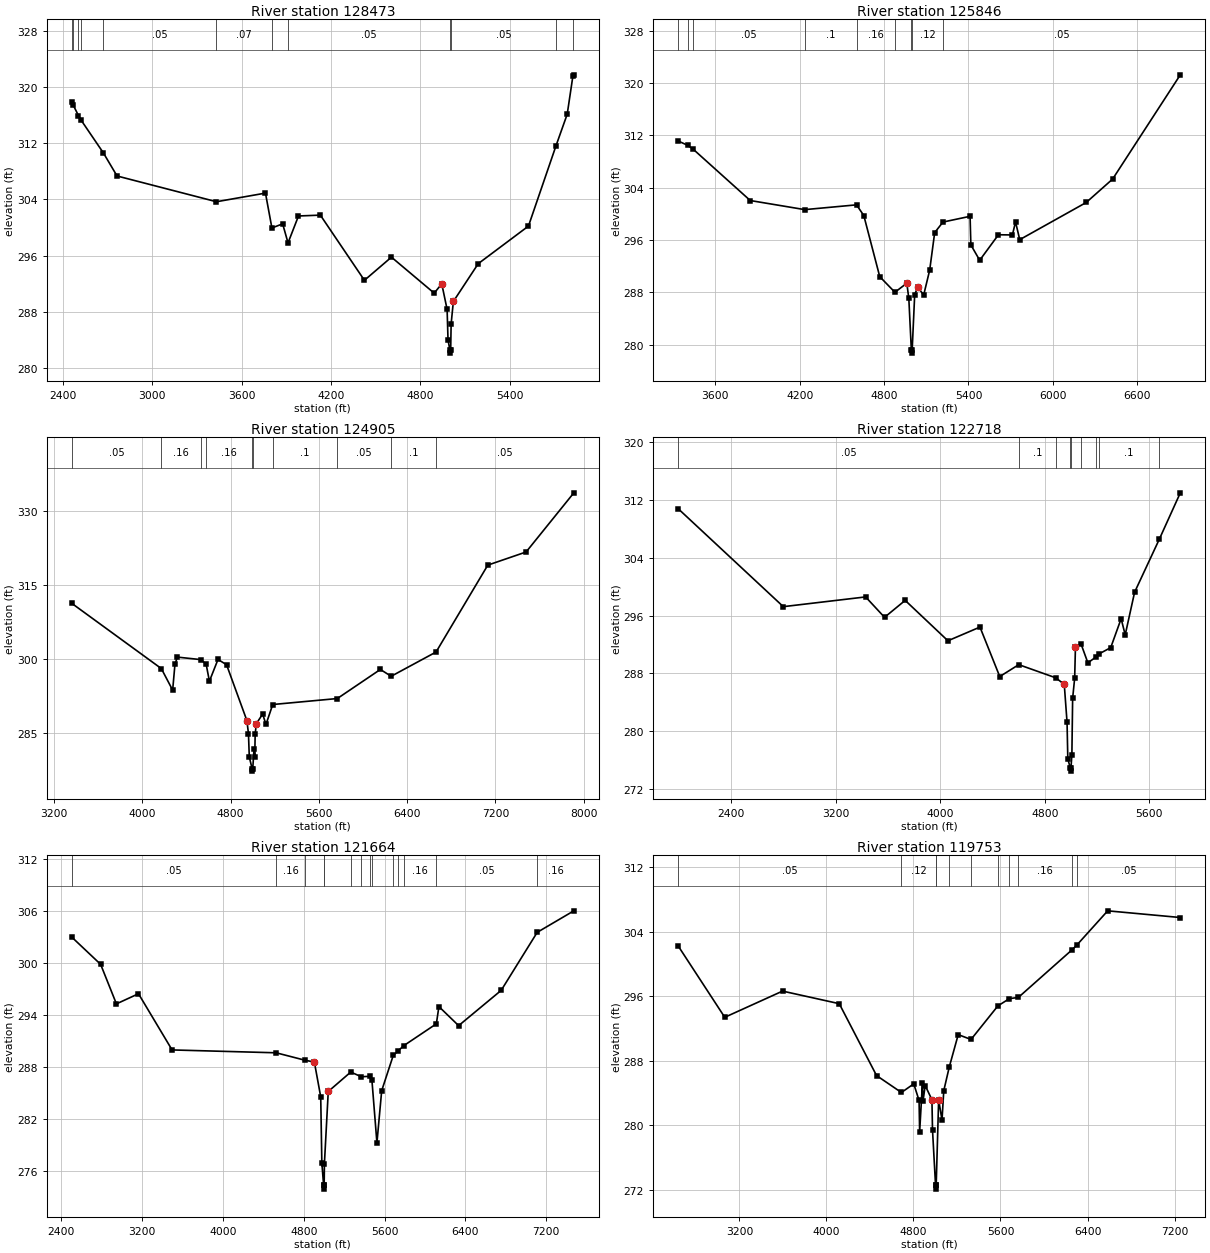
Type RM Length L Ch R = 1 ,128473  ,2627,2627,2627
BEGIN DESCRIPTION:
WICKSON CREEK 79.0
END DESCRIPTION:
XS GIS Cut Line= 4
      3550792.12     10263991.68      3550087.63      10262300.9
      3549479.31     10261413.24      3549017.64     10261398.02
#Sta/Elev= 30
  2460.5  317.84  2471.2  317.41  2505.3  315.95  2524.1  315.27  2672.6  310.63
  2764.4  307.34  3431.7  303.67  3760.5   304.9  3803.7  299.93  3875.9  300.52
  3911.9   297.8  3982.1  301.64  4128.9  301.76  4424.6  292.47    4606  295.77
    4893  290.64  4943.7  291.97  4979.6  288.32  4985.7  283.98  4997.6  282.59
  5000.3  282.09  5003.6  282.59  5006.6  286.25  5021.5  289.45  5188.4  294.84
  5525.6   300.2  5710.5  311.65  5785.7  316.15  5823.5  321.54  5830.2  321.76
#Mann= 12 ,-1 , 0
  2460.5     .05       0  2471.2     .16       0  2505.3     .05       0
  2524.1     .16       0  2672.6     .05       0  3431.7     .07       0
  3803.7     .16       0  3911.9     .05       0  4997.6    .035       0
  5003.6     .05       0  5710.5      .1       0  5823.5     .05       0
Bank Sta=4943.7,5021.5
XS Rating Curve= 0 ,0
Exp/Cntr=0.3,0.1

Type RM Length L Ch R = 1 ,125846  ,941,941,941
BEGIN DESCRIPTION:
WICKSON CREEK 78.0
END DESCRIPTION:
XS GIS Cut Line= 4
        3551682.     10262589.84      3551833.92     10261352.83
      3551226.28     10260842.85       3549842.1     10260191.64
#Sta/Elev= 30
  3336.7  311.14    3403   310.5  3442.1  309.91  3848.7  302.05  4236.2  300.66
  4604.3  301.39    4656  299.75  4769.2  290.42  4877.1  288.03  4961.7  289.42
    4976  287.08  4993.8  279.23  4996.6  278.73  4999.8  279.23  5017.7  287.68
  5039.7  288.83  5081.5   287.6  5124.3  291.42  5159.8  297.15  5218.9  298.76
  5411.4  299.64    5417  295.27  5479.8  292.92    5613  296.82  5712.4  296.79
  5734.5  298.79  5764.4  296.07    6237  301.75  6424.8  305.33    6906  321.26
#Mann= 9 ,-1 , 0
  3336.7     .05       0    3403      .1       0  3442.1     .05       0
  4236.2      .1       0  4604.3     .16       0  4877.1     .12       0
  4993.8     .07       0  4999.8     .12       0  5218.9     .05       0
Bank Sta=4961.7,5039.7
XS Rating Curve= 0 ,0
Exp/Cntr=0.3,0.1

Type RM Length L Ch R = 1 ,124905  ,2187,2187,2187
BEGIN DESCRIPTION:
WICKSON CREEK 77.0
END DESCRIPTION:
XS GIS Cut Line= 3
      3553292.12     10261841.66      3552042.11     10260741.64
      3549642.14     10259141.67
#Sta/Elev= 30
  3361.6  311.31  4173.1   298.1  4275.8  293.73  4296.6  298.97  4318.4  300.42
  4532.8  299.91  4579.4  298.96  4608.8  295.54  4686.6  299.95  4764.4  298.87
  4948.4  287.57  4962.7  284.93  4970.2  280.19  4995.7  277.83  4998.5  277.33
  5001.7  277.83  5012.9  281.84  5019.6  280.14  5023.4  284.82  5034.2  286.95
  5091.3  288.89  5121.4  286.78  5182.5  290.82  5767.8  292.03  6157.9  297.92
  6255.8  296.54  6662.5  301.45  7131.4  319.05  7478.5  321.71  7911.1  333.69
#Mann= 10 ,-1 , 0
  3361.6     .05       0  4173.1     .16       0  4532.8      .1       0
  4579.4     .16       0  4995.7     .07       0  5001.7     .16       0
  5182.5      .1       0  5767.8     .05       0  6255.8      .1       0
  6662.5     .05       0
Bank Sta=4948.4,5034.2
XS Rating Curve= 0 ,0
Exp/Cntr=0.3,0.1

Type RM Length L Ch R = 1 ,122718  ,1054,1054,1054
BEGIN DESCRIPTION:
WICKSON CREEK 75.0
END DESCRIPTION:
XS GIS Cut Line= 3
      3553692.11     10261391.64      3552092.11     10258891.64
      3551642.11     10258141.65
#Sta/Elev= 30
    1995   310.8  2799.2  297.23  3429.2  298.58  3574.1  295.75  3731.9   298.1
  4059.2   292.5  4304.4   294.4  4455.8  287.54  4601.3  289.19  4885.4  287.36
  4949.6  286.45  4970.9   281.2  4976.8   276.1  4995.2  274.93  4997.9  274.43
  5001.2  274.93  5007.9  276.71  5013.7  284.53  5029.2  287.31  5035.1  291.57
  5077.6  292.08  5130.3  289.44    5195  290.29  5214.5  290.67  5305.2  291.55
  5384.9  295.56    5416  293.32  5487.9  299.23  5677.8  306.61  5837.8  313.01
#Mann= 9 ,-1 , 0
    1995     .05       0  4601.3      .1       0  4885.4     .16       0
  4995.2     .07       0  5001.2     .16       0  5077.6      .1       0
    5195     .16       0  5214.5      .1       0  5677.8     .05       0
Bank Sta=4949.6,5035.1
XS Rating Curve= 0 ,0
Exp/Cntr=0.3,0.1

Type RM Length L Ch R = 1 ,121664  ,1911,1911,1911
BEGIN DESCRIPTION:
WICKSON CREEK 73.0
END DESCRIPTION:
XS GIS Cut Line= 3
      3553642.12     10260841.68       3552343.9     10257077.66
      3551497.58      10256567.7
#Sta/Elev= 30
  2504.4  302.94    2790   299.8  2946.3  295.24  3164.7  296.41  3497.3  289.93
  4527.4   289.6  4810.7  288.75  4905.7  288.53  4968.6  284.52  4979.7  276.93
  4996.8  274.38  4999.5  273.88  5002.8  274.38  5005.1  276.81  5043.2  285.14
  5265.9  287.38  5370.3  286.84  5458.8  286.89  5475.6  286.41  5524.9  279.22
  5572.1  285.23  5686.3  289.29  5730.6  289.78  5791.7  290.43  6113.2  292.94
  6138.4  294.93  6333.7  292.73    6755   296.8  7111.5  303.49  7474.1  305.97
#Mann= 14 ,-1 , 0
  2504.4     .05       0  4527.4     .16       0  4810.7     .12       0
  4996.8     .07       0  5002.8     .12       0  5265.9     .05       0
  5370.3     .12       0  5458.8     .16       0  5475.6     .12       0
  5686.3     .16       0  5730.6     .05       0  5791.7     .16       0
  6113.2     .05       0  7111.5     .16       0
Bank Sta=4905.7,5043.2
XS Rating Curve= 0 ,0
Exp/Cntr=0.3,0.1

Type RM Length L Ch R = 1 ,119753  ,2678,2678,2678
BEGIN DESCRIPTION:
WICKSON CREEK 72.0
END DESCRIPTION:
XS GIS Cut Line= 4
      3554313.29     10260730.67      3554248.18     10258998.91
      3553740.37     10257566.61      3552789.86     10256590.06
#Sta/Elev= 30
  2637.6  302.25  3065.2  293.41  3596.5  296.66  4117.7   295.1  4460.7  286.18
  4689.3  284.08  4802.7  285.15  4851.5  283.09  4856.8   279.2  4882.4  285.26
  4887.7  283.02    4908  284.94  4969.7  283.18    4975  279.45  5002.9  272.59
  5005.7  272.09  5008.9  272.59  5031.5  283.18  5062.4  280.65  5078.5   284.3
  5129.1  287.24  5211.4  291.26    5329  290.66  5576.5  294.83  5682.4  295.73
  5763.9  295.87    6260  301.81  6298.9  302.33  6585.5  306.62    7253  305.79
#Mann= 11 ,-1 , 0
  2637.6     .05       0  4689.3     .12       0  5002.9     .07       0
  5008.9     .12       0  5129.1     .16       0    5329     .05       0
  5576.5      .1       0  5682.4     .05       0  5763.9     .16       0
    6260      .1       0  6298.9     .05       0
Bank Sta=4969.7,5031.5
XS Rating Curve= 0 ,0
Exp/Cntr=0.3,0.1

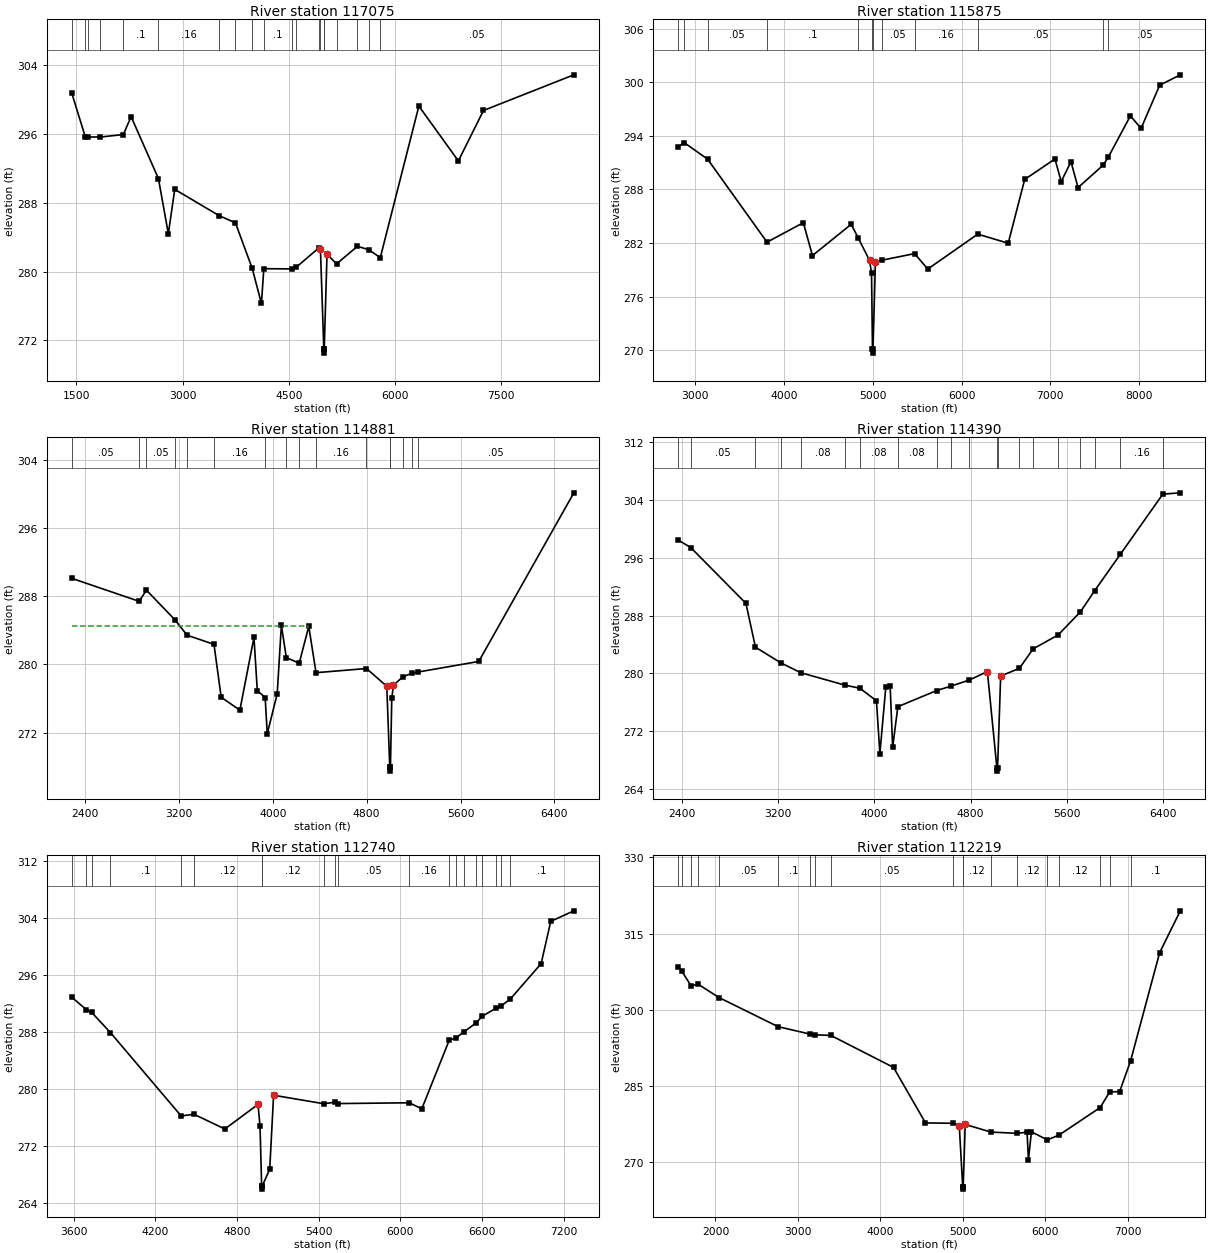
Type RM Length L Ch R = 1 ,117075  ,1200,1200,1200
BEGIN DESCRIPTION:
WICKSON CREEK 71.0
END DESCRIPTION:
XS GIS Cut Line= 4
      3557443.73     10260669.26      3557205.01     10258065.07
      3555653.36     10257077.66      3553103.45     10256415.77
#Sta/Elev= 30
  1434.6  300.76  1624.8  295.69  1663.6  295.66  1837.4  295.65  2162.5  295.94
  2272.3  298.02  2658.2  290.82  2797.9  284.39  2888.3  289.56  3513.2  286.51
  3745.5  285.66  3982.3  280.36  4112.4  276.28  4146.1  280.33  4538.9   280.3
  4602.8  280.49  4929.1  282.79  4945.3  282.62  4993.1     271  4995.8   270.5
  4999.1     271  5038.4     282  5173.6  280.89  5467.2  282.93  5627.3  282.54
  5790.6  281.61  6335.2  299.25  6892.7  292.87  7247.5  298.74  8523.3  302.89
#Mann= 20 ,-1 , 0
  1434.6      .1       0  1624.8     .05       0  1663.6      .1       0
  1837.4     .12       0  2162.5      .1       0  2658.2     .16       0
  3513.2      .1       0  3745.5      .1       0  3982.3     .16       0
  4146.1      .1       0  4538.9     .16       0  4602.8     .05       0
  4929.1      .1       0  4945.3     .12       0  4993.1     .07       0
  4999.1     .12       0  5173.6     .16       0  5467.2     .05       0
  5627.3     .16       0  5790.6     .05       0
Bank Sta=4945.3,5038.4
XS Rating Curve= 0 ,0
Exp/Cntr=0.3,0.1

Type RM Length L Ch R = 1 ,115875  ,994,994,994
BEGIN DESCRIPTION:
WICKSON CREEK 70.0
END DESCRIPTION:
XS GIS Cut Line= 4
      3558228.38     10258903.21       3557888.6     10257533.39
      3555642.51     10256318.11      3553949.77     10256296.41
#Sta/Elev= 30
    2807  292.75  2873.2  293.24  3137.9  291.38  3807.3  282.09  4216.7  284.27
  4319.5  280.59  4756.1  284.09  4832.4  282.61  4963.5  280.04  4985.4   278.6
  4995.9  270.17  4998.6  269.67  5001.9  270.17  5029.2  279.91  5102.8  280.07
  5470.6  280.81    5619  279.08  6182.6  282.99  6525.6  281.97  6711.1  289.11
  7052.5   291.4  7122.6  288.87  7232.6   291.1  7312.6   288.2  7594.4   290.7
  7654.8  291.63  7902.6  296.23  8022.6  294.82  8232.6  299.66    8465  300.82
#Mann= 12 ,-1 , 0
    2807     .05       0  2873.2      .1       0  3137.9     .05       0
  3807.3      .1       0  4832.4     .12       0  4995.9     .07       0
  5001.9     .12       0  5102.8     .05       0  5470.6     .16       0
  6182.6     .05       0  7594.4     .16       0  7654.8     .05       0
Bank Sta=4963.5,5029.2
XS Rating Curve= 0 ,0
Exp/Cntr=0.3,0.1

Type RM Length L Ch R = 1 ,114881  ,491,491,491
BEGIN DESCRIPTION:
WICKSON CREEK 69.0
END DESCRIPTION:
XS GIS Cut Line= 4
      3558830.06     10258761.96      3558743.26      10257362.2
      3557527.98     10256125.22      3556887.81     10255181.24
#Sta/Elev= 30
  2288.3  290.12  2862.2  287.42  2924.7  288.73    3170   285.2    3270  283.44
  3499.8  282.36  3561.1  276.15  3720.2  274.62  3840.5  283.17  3868.8  276.92
  3935.7  276.11  3953.6  271.85  4038.5  276.56  4073.8  284.61  4116.2   280.8
  4225.9  280.14  4307.2  284.47  4369.2  279.03    4799  279.52  4971.9  277.43
  4997.1  267.96  4999.9  267.46  5003.1  267.96  5014.3  276.01  5028.4  277.56
  5108.7  278.54  5182.9  278.95  5234.9   279.1  5755.4  280.35  6565.4  300.17
#Mann= 16 ,-1 , 0
  2288.3     .05       0  2862.2      .1       0  2924.7     .05       0
    3170     .16       0    3270     .05       0  3499.8     .16       0
  3935.7     .07       0  4116.2     .05       0  4225.9     .07       0
  4369.2     .16       0    4799     .12       0  4997.1     .07       0
  5003.1     .12       0  5108.7     .05       0  5182.9     .12       0
  5234.9     .05       0
#XS Ineff= 2 , 0
         4302.44  284.47
Permanent Ineff=
       F       F
Bank Sta=4971.9,5028.4
XS Rating Curve= 0 ,0
Exp/Cntr=0.3,0.1

Type RM Length L Ch R = 1 ,114390  ,1650,1650,1650
BEGIN DESCRIPTION:
WICKSON CREEK 68.0
END DESCRIPTION:
XS GIS Cut Line= 4
      3560153.83     10257893.88      3559133.88     10257166.89
      3558385.18       10256505.      3557496.29     10254803.09
#Sta/Elev= 30
  2370.8  298.46    2475  297.42  2933.1   289.7  3012.5  283.63  3223.1  281.46
  3389.7  280.09  3753.1  278.39  3880.5  277.94  4017.8  276.21  4046.3   268.9
  4095.6  278.11  4131.6  278.27  4152.5  269.77  4195.6  275.39  4517.2  277.62
    4640  278.25  4790.4  279.09  4939.6  280.25  5018.3  266.97    5021  266.47
  5024.3  266.97    5050  279.64  5205.8   280.7    5319  283.39    5528  285.33
  5712.5  288.52  5831.2  291.45  6044.9   296.5  6397.4  304.82  6542.7     305
#Mann= 20 ,-1 , 0
  2370.8     .08       0    2475     .05       0  3012.5     .05       0
  3223.1     .08       0  3389.7     .08       0  3753.1     .08       0
  3880.5     .08       0  4195.6     .08       0  4517.2     .08       0
    4640     .12       0  4790.4     .12       0  5018.3     .07       0
  5024.3     .12       0  5205.8      .1       0    5319     .05       0
    5528     .05       0  5712.5     .16       0  5831.2     .05       0
  6044.9     .16       0  6397.4      .1       0
Bank Sta=4939.6,5050
XS Rating Curve= 0 ,0
Exp/Cntr=0.3,0.1

Type RM Length L Ch R = 1 ,112740  ,521,521,521
BEGIN DESCRIPTION:
WICKSON CREEK 67.0
END DESCRIPTION:
XS GIS Cut Line= 3
      3560067.01     10257655.13      3559242.11     10256491.64
       3557642.1     10254891.64
#Sta/Elev= 30
  3586.5  292.92  3693.9  291.17  3733.4  290.78  3870.7  287.95  4390.2  276.24
    4484  276.48  4711.3  274.41  4954.9  277.86  4969.7  274.78  4981.5  266.46
  4984.2  265.96  4987.5  266.46    5041  268.76  5069.3  279.15  5437.6  277.96
  5518.8  278.16  5544.1  277.98  6066.7  278.09  6158.3  277.24  6359.5  286.87
  6411.9  287.24  6469.7  288.08  6556.5   289.3    6604  290.27  6701.2  291.35
  6738.4  291.66  6808.4  292.66  7035.1  297.64  7105.8  303.58  7275.5  305.06
#Mann= 20 ,-1 , 0
  3586.5     .05       0  3693.9      .1       0  3733.4     .05       0
  3870.7      .1       0  4390.2     .05       0    4484     .12       0
  4981.5     .07       0  4987.5     .12       0  5437.6     .16       0
  5518.8     .12       0  5544.1     .05       0  6066.7     .16       0
  6359.5     .05       0  6411.9      .1       0  6469.7     .05       0
  6556.5      .1       0    6604     .05       0  6701.2      .1       0
  6738.4     .05       0  6808.4      .1       0
Bank Sta=4954.9,5069.3
XS Rating Curve= 0 ,0
Exp/Cntr=0.3,0.1

Type RM Length L Ch R = 1 ,112219  ,1088,1088,1088
BEGIN DESCRIPTION:
WICKSON CREEK 66.0
END DESCRIPTION:
XS GIS Cut Line= 3
      3561242.11     10259291.65      3559642.11     10256191.64
      3558642.09     10253791.61
#Sta/Elev= 30
  1548.7  308.41  1592.4   307.6  1703.6  304.74  1792.4  305.01  2042.2  302.42
  2758.9  296.68    3150   295.2  3205.9  295.08  3399.3  294.95  4159.7  288.65
  4547.2  277.72    4884  277.65  4956.9  277.16  4998.2  265.18    5001  264.68
  5004.2  265.18    5029  277.42  5339.7  275.92  5652.4  275.67  5778.8  275.88
  5795.6   270.5  5831.9  275.98  6024.3  274.37    6169  275.35  6665.7  280.75
    6782  283.85  6901.1  283.86  7034.6  289.96  7386.5  311.25  7637.3  319.49
#Mann= 19 ,-1 , 0
  1548.7     .15       0  1592.4      .1       0  1703.6     .15       0
  1792.4      .1       0  2042.2     .05       0  2758.9      .1       0
    3150     .05       0  3205.9      .1       0  3399.3     .05       0
    4884     .12       0  4998.2     .07       0  5004.2     .12       0
  5339.7     .16       0  5652.4     .12       0  6024.3     .16       0
    6169     .12       0  6665.7     .05       0    6782     .12       0
  7034.6      .1       0
Bank Sta=4956.9,5029
XS Rating Curve= 0 ,0
Exp/Cntr=0.3,0.1

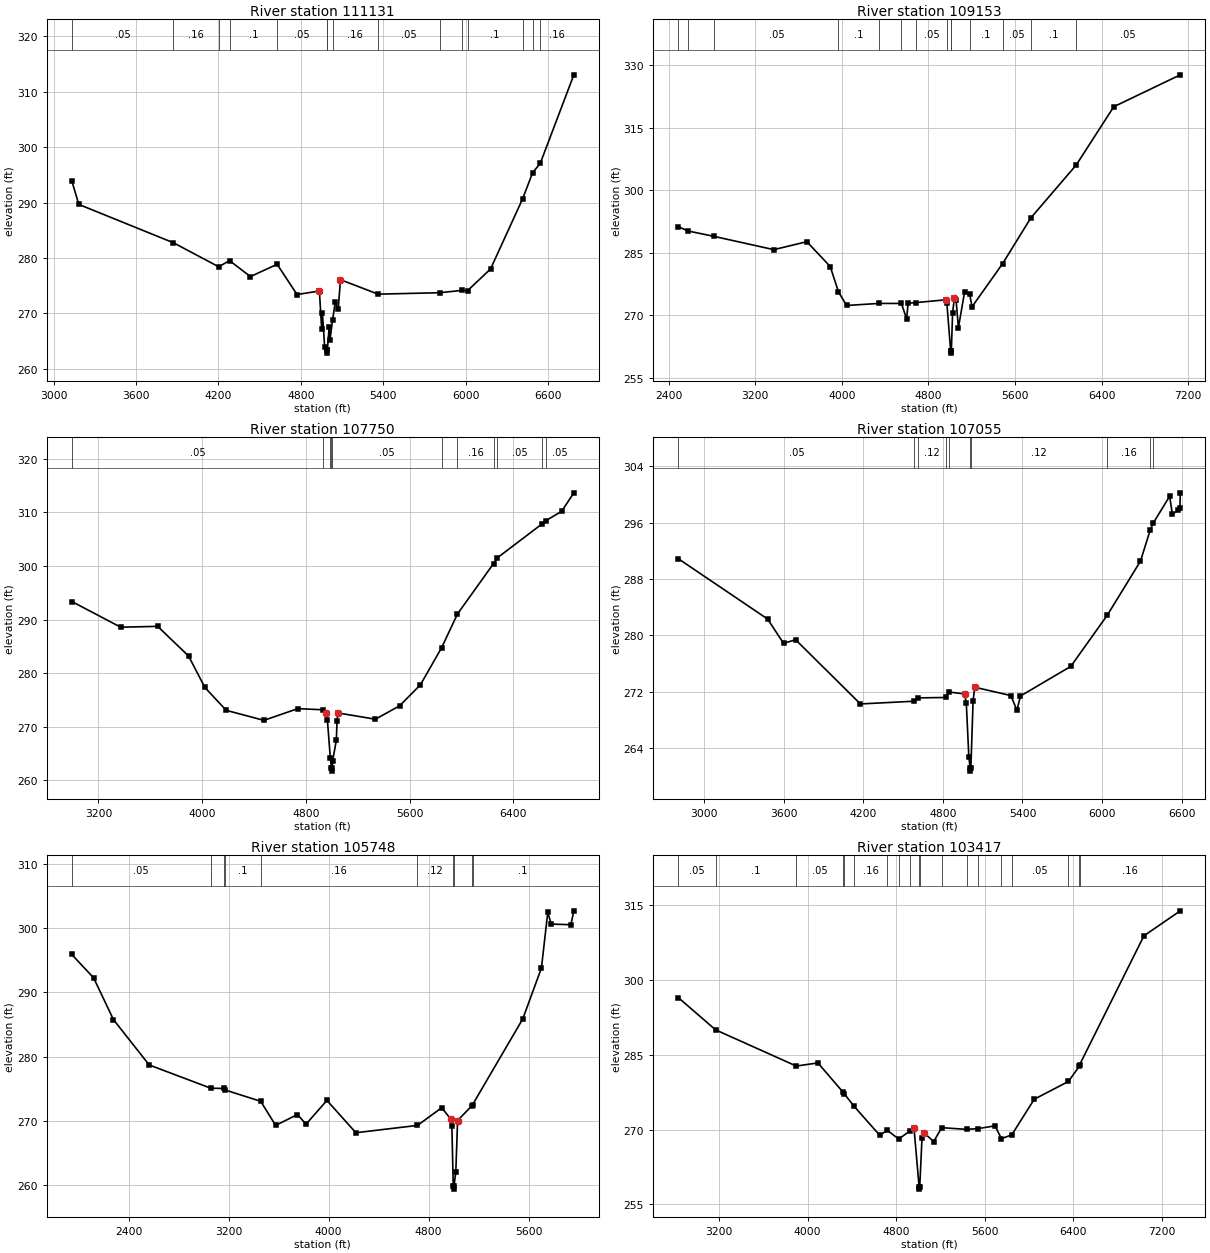
Type RM Length L Ch R = 1 ,111131  ,1978,1978,1978
BEGIN DESCRIPTION:
WICKSON CREEK 64.0
END DESCRIPTION:
XS GIS Cut Line= 3
       3560592.1     10257391.61      3560192.11     10255591.64
      3559342.12     10253991.68
#Sta/Elev= 30
  3132.6  293.95  3183.8  289.68    3873  282.76  4202.2  278.43  4281.2  279.54
  4433.5  276.66  4627.8  278.88  4772.9  273.42  4935.5  274.06  4952.1  267.22
  4957.3  270.16  4973.9  263.99  4987.3  263.35    4990  262.85  4993.3  263.35
  5006.6  267.49  5012.3  265.23  5031.8  268.86  5050.6     272  5072.6  270.78
  5088.9   276.1    5363  273.49  5813.3  273.75  5976.9  274.18    6014  274.11
  6181.6  278.03  6414.9  290.67  6487.8  295.38  6544.1  297.12  6788.2  313.06
#Mann= 15 ,-1 , 0
  3132.6     .05       0    3873     .16       0  4202.2     .05       0
  4281.2      .1       0  4627.8     .05       0  4987.3     .03       0
  4993.3     .05       0  5031.8     .16       0    5363     .05       0
  5813.3      .1       0  5976.9     .05       0    6014      .1       0
  6414.9     .16       0  6487.8      .1       0  6544.1     .16       0
Bank Sta=4935.5,5088.9
XS Rating Curve= 0 ,0
Exp/Cntr=0.3,0.1

Type RM Length L Ch R = 1 ,109153  ,1403,1403,1403
BEGIN DESCRIPTION:
WICKSON CREEK 62.0
END DESCRIPTION:
XS GIS Cut Line= 4
      3561512.74     10257045.11      3561881.66     10255493.46
      3561263.17     10253648.84      3561078.96     10252565.24
#Sta/Elev= 30
  2487.9  291.24  2579.8   290.2  2820.7   288.9  3370.9  285.73  3676.4  287.64
  3892.4  281.69  3968.2  275.64  4043.6  272.35  4340.4  272.84  4550.4  272.84
  4598.3  269.11  4612.1  272.89    4688  273.05  4960.1  273.71  4970.4  272.86
  5005.5  261.43  5008.2  260.93  5011.5  261.43  5023.4  270.62    5040   274.2
  5055.1  273.77  5076.9     267  5134.7   275.7  5180.4  275.09    5203  272.05
  5486.2  282.41  5745.7  293.32  6166.2  306.04  6512.4  319.98  7127.5  327.63
#Mann= 14 ,-1 , 0
  2487.9     .05       0  2579.8      .1       0  2820.7     .05       0
  3968.2      .1       0  4340.4     .05       0  4550.4     .16       0
    4688     .05       0  4970.4     .16       0  5005.5     .07       0
  5011.5     .16       0  5180.4      .1       0  5486.2     .05       0
  5745.7      .1       0  6166.2     .05       0
Bank Sta=4960.1,5040
XS Rating Curve= 0 ,0
Exp/Cntr=0.3,0.1

Type RM Length L Ch R = 1 ,107750  ,695,695,695
BEGIN DESCRIPTION:
WICKSON CREEK 59.0
END DESCRIPTION:
XS GIS Cut Line= 3
      3562876.91     10256630.86      3562152.93     10253985.21
      3561664.96     10252965.91
#Sta/Elev= 30
  2994.2  293.38  3372.1  288.58  3656.9  288.74  3895.4  283.19  4020.7  277.34
  4185.7  273.06  4476.1  271.19  4738.3  273.38  4934.7  273.16  4952.9  272.65
    4966  271.28  4988.7  264.17  4997.5  262.21  5000.2  261.71  5003.5  262.21
  5005.7  263.53    5035  267.44  5040.2  271.01  5046.2  272.58  5336.5   271.4
  5523.1  273.91  5683.6  277.82  5847.2  284.76  5969.5  291.05    6248  300.47
  6278.1  301.55  6624.3  307.91  6650.2  308.45  6773.6  310.23  6867.2  313.67
#Mann= 11 ,-1 , 0
  2994.2     .05       0  4934.7     .16       0  4988.7     .05       0
  4997.5     .03       0  5003.5     .05       0  5847.2      .1       0
  5969.5     .16       0    6248      .1       0  6278.1     .05       0
  6624.3      .1       0  6650.2     .05       0
Bank Sta=4952.9,5046.2
XS Rating Curve= 0 ,0
Exp/Cntr=0.3,0.1

Type RM Length L Ch R = 1 ,107055  ,1307,1307,1307
BEGIN DESCRIPTION:
WICKSON CREEK 58.0
END DESCRIPTION:
XS GIS Cut Line= 4
       3563324.8     10256372.38      3563227.14     10255384.95
      3562595.17     10253430.03      3562045.79     10252933.93
#Sta/Elev= 30
  2803.6  290.89  3477.6  282.31  3598.2  278.85  3688.6  279.37  4177.7  270.24
  4585.6  270.63  4612.5   271.1  4821.6  271.16  4842.6  271.94  4963.5  271.67
  4976.4  270.35  4995.5  262.74  5004.9  261.19  5007.7  260.69  5010.9  261.19
  5027.5   270.6  5039.5  272.62  5312.7  271.43  5358.2  269.35    5385  271.37
  5764.6  275.58  6041.1  282.89  6290.3  290.55  6364.2     295  6387.6  295.99
    6510  299.76  6530.9  297.23  6573.5  297.75  6587.7  298.11  6590.6  300.25
#Mann= 10 ,-1 , 0
  2803.6     .05       0  4585.6      .1       0  4612.5     .12       0
  4821.6      .1       0  4842.6     .12       0  5004.9     .07       0
  5010.9     .12       0  6041.1     .16       0  6364.2      .1       0
  6387.6     .16       0
Bank Sta=4963.5,5039.5
XS Rating Curve= 0 ,0
Exp/Cntr=0.3,0.1

Type RM Length L Ch R = 1 ,105748  ,2331,2331,2331
BEGIN DESCRIPTION:
WICKSON CREEK 56.0
END DESCRIPTION:
XS GIS Cut Line= 3
       3564242.1     10256191.64      3563184.88     10252979.46
      3562793.15     10252477.01
#Sta/Elev= 30
  1943.6  295.87  2118.4  292.24  2277.3  285.74  2563.4  278.69  3055.7  275.08
  3160.5  275.03  3173.7  274.78  3455.8  273.04  3575.4  269.29    3750  270.98
  3818.8  269.48    3986  273.18  4217.6  268.15  4710.9  269.29  4904.7  272.04
  4975.6  270.32  4986.1  269.14  4997.1  259.88  4999.8  259.38  5003.1  259.88
  5017.7   262.1  5031.9  270.05    5148  272.38  5151.4   272.5  5553.2  285.84
  5702.9  293.76  5753.6  302.42  5781.2   300.6  5938.6   300.5  5962.4  302.66
#Mann= 10 ,-1 , 0
  1943.6     .05       0  3055.7      .1       0  3160.5     .16       0
  3173.7      .1       0  3455.8     .16       0  4710.9     .12       0
  4997.1     .07       0  5003.1     .12       0    5148     .16       0
  5151.4      .1       0
Bank Sta=4975.6,5031.9
XS Rating Curve= 0 ,0
Exp/Cntr=0.3,0.1

Type RM Length L Ch R = 1 ,103417  ,944,944,944
BEGIN DESCRIPTION:
WICKSON CREEK 54.0
END DESCRIPTION:
XS GIS Cut Line= 3
       3564492.1     10256141.66      3564803.55     10254428.68
      3564127.75      10251717.4
#Sta/Elev= 30
  2831.7  296.48  3169.3     290  3898.1  282.74  4093.3  283.37  4319.2  277.54
  4330.8   277.2  4418.3  274.72  4652.2  268.85  4720.3  269.87  4822.5   268.1
  4924.8  269.72  4961.3  270.32  5007.3  258.56  5010.1  258.06  5013.3  258.56
  5033.5  268.23  5051.6  269.38  5139.3  267.58  5211.6  270.39    5436  270.04
  5538.3  270.19  5693.1  270.75  5751.2  268.17    5845  268.96  6047.6  276.09
  6356.3  279.65  6456.2  282.75  6458.4  283.04  7038.4  308.86    7367  313.87
#Mann= 19 ,-1 , 0
  2831.7     .05       0  3169.3      .1       0  3898.1     .05       0
  4319.2     .16       0  4330.8      .1       0  4418.3     .16       0
  4720.3      .1       0  4822.5     .16       0  4924.8     .12       0
  5007.3     .07       0  5013.3     .12       0  5211.6     .16       0
    5436      .1       0  5538.3     .05       0  5751.2     .16       0
    5845     .05       0  6356.3     .16       0  6456.2      .1       0
  6458.4     .16       0
Bank Sta=4961.3,5051.6
XS Rating Curve= 0 ,0
Exp/Cntr=0.3,0.1

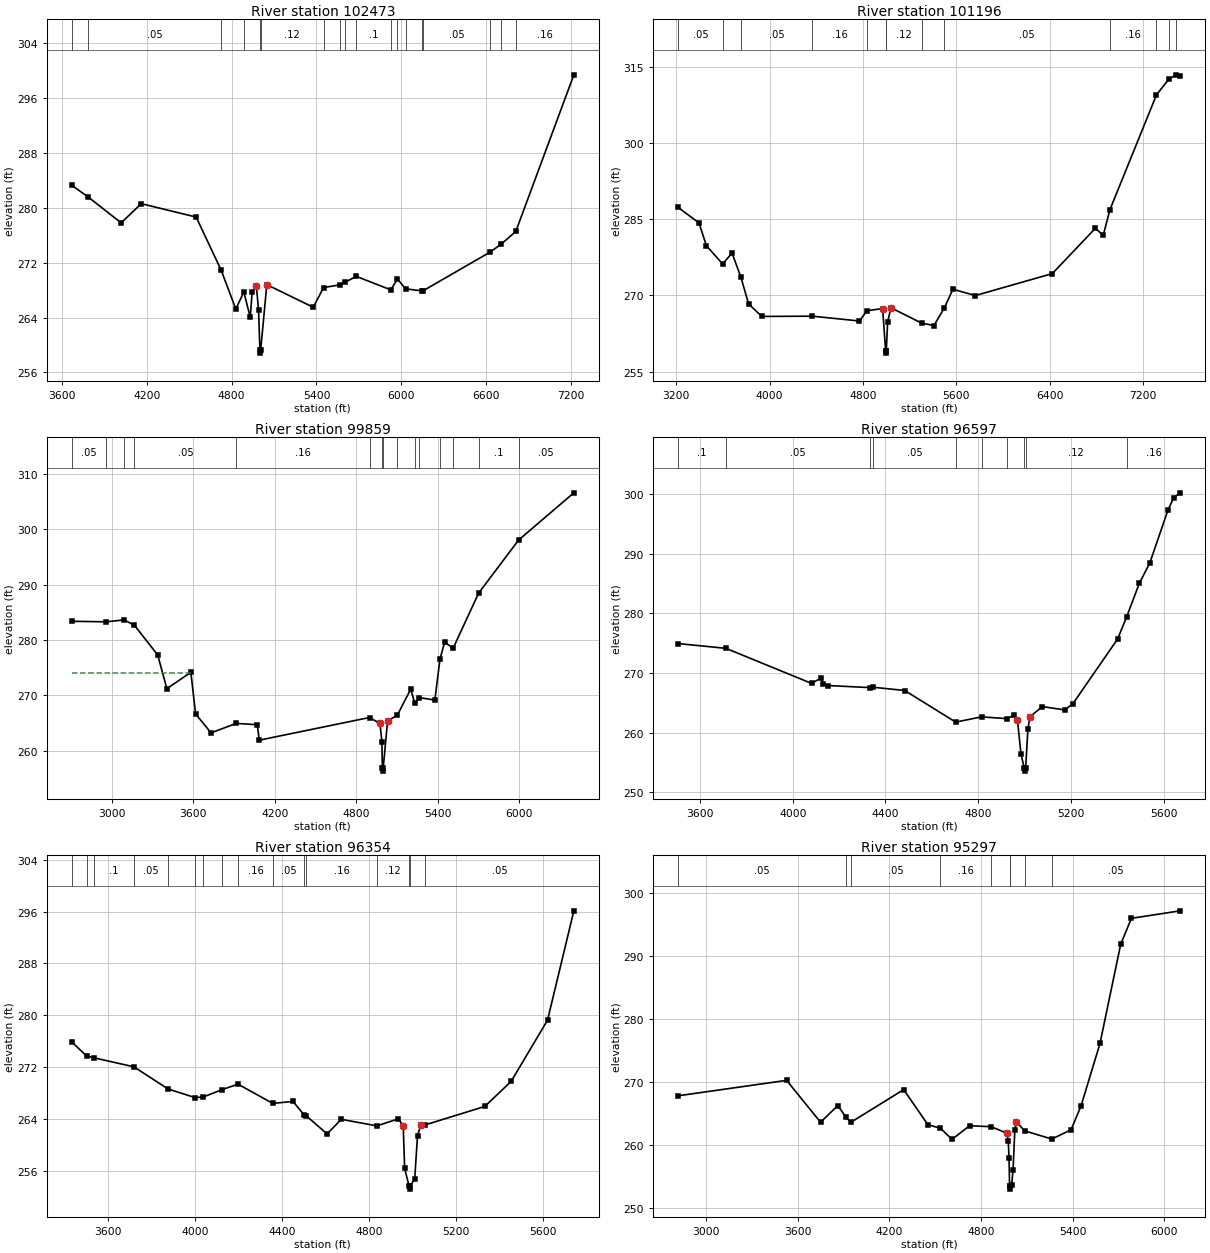
Type RM Length L Ch R = 1 ,102473  ,1277,1277,1277
BEGIN DESCRIPTION:
WICKSON CREEK 53.0
END DESCRIPTION:
XS GIS Cut Line= 3
      3565473.25     10255178.76      3565733.66     10254137.12
      3564496.87     10251989.02
#Sta/Elev= 30
  3668.7  283.27    3783  281.59  4017.9   277.8  4160.5  280.59  4548.8  278.64
  4725.1  270.93  4829.5  265.24  4886.1  267.74  4931.7  264.01  4944.9  267.75
  4974.9  268.58  4990.6  265.03  4999.6  259.32  5002.3  258.82  5005.6  259.32
  5048.7   268.8  5377.2   265.5  5450.1  268.37  5566.1  268.77  5602.9  269.15
  5682.1     270  5925.7  268.04  5973.3  269.62  6030.1  268.18  6146.1   267.9
  6151.7  267.87  6629.9  273.55  6704.5  274.66  6810.4  276.54  7221.1  299.36
#Mann= 18 ,-1 , 0
  3668.7      .1       0    3783     .05       0  4725.1     .16       0
  4886.1     .12       0  4999.6     .07       0  5005.6     .12       0
  5450.1     .16       0  5566.1      .1       0  5602.9     .05       0
  5682.1      .1       0  5925.7     .05       0  5973.3      .1       0
  6030.1     .05       0  6146.1      .1       0  6151.7     .05       0
  6629.9     .16       0  6704.5     .05       0  6810.4     .16       0
Bank Sta=4974.9,5048.7
XS Rating Curve= 0 ,0
Exp/Cntr=0.3,0.1

Type RM Length L Ch R = 1 ,101196  ,1337,1337,1337
BEGIN DESCRIPTION:
WICKSON CREEK 50.0
END DESCRIPTION:
XS GIS Cut Line= 4
      3567630.18     10254334.48      3567202.16     10253852.96
      3565690.25     10252542.07      3564279.67     10251674.02
#Sta/Elev= 30
  3217.1  287.28  3394.8  284.24  3458.8  279.74  3597.2  276.17  3677.9  278.31
  3752.9  273.64    3820   268.3  3933.1  265.84  4366.1  265.89  4769.8  264.94
  4834.3  266.97  4968.3  267.39  4993.8  259.12  4996.6  258.62  4999.8  259.12
  5011.1  264.72  5039.4  267.55  5302.6  264.52  5408.1  264.05  5497.2  267.53
  5570.4  271.19  5762.3  269.95  6422.1  274.27  6791.2  283.19  6858.3  281.79
  6916.1  286.87  7314.6  309.44  7420.2  312.53  7482.3  313.38  7518.7  313.16
#Mann= 13 ,-1 , 0
  3217.1     .05       0  3597.2      .1       0  3752.9     .05       0
  4366.1     .16       0  4834.3     .12       0  4993.8     .07       0
  4999.8     .12       0  5302.6     .16       0  5497.2     .05       0
  6916.1     .16       0  7314.6      .1       0  7420.2     .16       0
  7482.3      .1       0
Bank Sta=4968.3,5039.4
XS Rating Curve= 0 ,0
Exp/Cntr=0.3,0.1

Type RM Length L Ch R = 1 ,99859   ,3262,3262,3262
BEGIN DESCRIPTION:
WICKSON CREEK 47.0
END DESCRIPTION:
XS GIS Cut Line= 3
      3567940.22     10253781.28      3567788.66     10252947.71
      3565560.08     10251164.06
#Sta/Elev= 30
  2703.5  283.37  2956.9  283.28  3089.5  283.62  3165.6  282.65  3337.1   277.3
  3404.4  271.22  3581.4  274.17  3616.6  266.66  3730.3  263.25  3916.5  264.96
  4071.5  264.72  4085.6  261.93  4898.8  266.02  4975.6  264.94    4990  261.69
  4993.4  256.85  4996.2  256.35  4999.4  256.85  5032.1  265.42  5103.9  266.44
  5202.9  271.15  5232.5  268.55  5265.1  269.61  5380.6  269.17    5418  276.53
  5452.6  279.62    5515   278.5  5703.2  288.45  5997.7  298.02  6405.2  306.54
#Mann= 15 ,-1 , 0
  2703.5     .05       0  2956.9     .16       0  3089.5      .1       0
  3165.6     .05       0  3916.5     .16       0  4898.8     .12       0
  4993.4     .07       0  4999.4     .12       0  5103.9     .16       0
  5232.5     .05       0  5265.1     .16       0    5418     .05       0
    5515     .16       0  5703.2      .1       0  5997.7     .05       0
#XS Ineff= 2 , 0
         3581.82  274.11
Permanent Ineff=
       F       F
Bank Sta=4975.6,5032.1
XS Rating Curve= 0 ,0
Exp/Cntr=0.3,0.1

Type RM Length L Ch R = 1 ,96597   ,243,243,243
BEGIN DESCRIPTION:
Mapping XS 035d4f1b
END DESCRIPTION:
XS GIS Cut Line= 3
      3568824.07     10252250.89      3568086.22     10251209.23
      3567257.18     10250888.03
#Sta/Elev= 30
  3506.1  274.94  3711.9  274.14  4081.1  268.26  4123.9   269.2  4130.2   268.1
  4153.4   267.9  4331.2  267.56  4346.1  267.62  4483.2  267.07  4702.7  261.77
  4814.2  262.65  4924.4  262.35  4954.6  262.93  4969.3  262.06  4984.5  256.44
  4998.5  254.05  5001.3  253.55  5004.5  254.05  5014.4  260.63    5023  262.67
  5076.6  264.37  5172.5  263.82  5207.8  264.82  5401.2   275.7    5440   279.4
  5494.8  285.03  5540.1  288.46  5619.2  297.41  5643.7  299.42  5671.7  300.22
#Mann= 10 ,-1 , 0
  3506.1      .1       0  3711.9     .05       0  4331.2     .16       0
  4346.1     .05       0  4702.7     .16       0  4814.2     .05       0
  4924.4     .12       0  4998.5     .07       0  5004.5     .12       0
    5440     .16       0
Bank Sta=4969.3,5023
XS Rating Curve= 0 ,0
Exp/Cntr=0.3,0.1

Type RM Length L Ch R = 1 ,96354   ,1057,1057,1057
BEGIN DESCRIPTION:
WICKSON CREEK 44.0
END DESCRIPTION:
XS GIS Cut Line= 3
      3568985.95     10252147.36      3568145.68     10250987.63
      3567347.25      10250626.6
#Sta/Elev= 30
    3432  275.88  3499.8  273.72  3535.4  273.42  3717.6  272.04  3874.5  268.62
  3999.4  267.28  4036.8  267.39  4124.2  268.53  4196.4  269.36    4356  266.39
  4449.1  266.69  4501.6  264.56  4509.1   264.5    4606  261.67    4671  263.93
  4834.8  262.92  4933.9  264.01  4955.9  262.93  4962.5  256.34  4982.6  253.65
  4985.3  253.15  4988.6  253.65  5008.7  254.74  5021.7  261.42  5037.3   263.1
  5057.5  263.08  5331.1  265.92  5452.1  269.79  5619.4  279.24  5740.4  296.13
#Mann= 16 ,-1 , 0
    3432      .1       0  3499.8     .05       0  3535.4      .1       0
  3717.6     .05       0  3874.5     .16       0  3999.4     .05       0
  4036.8     .16       0  4124.2     .05       0  4196.4     .16       0
    4356     .05       0  4501.6      .1       0  4509.1     .16       0
  4834.8     .12       0  4982.6     .07       0  4988.6     .12       0
  5057.5     .05       0
Bank Sta=4955.9,5037.3
XS Rating Curve= 0 ,0
Exp/Cntr=0.3,0.1

Type RM Length L Ch R = 1 ,95297   ,1845,1845,1845
BEGIN DESCRIPTION:
Mapping XS c38ecd11
END DESCRIPTION:
XS GIS Cut Line= 4
      3569876.68     10251535.83      3569225.64     10250298.85
      3568053.77     10249908.22      3567402.72     10249951.63
#Sta/Elev= 30
  2819.3  267.77  3528.6  270.22  3750.7  263.56  3863.7  266.22  3917.1  264.36
  3948.6  263.55  4294.7  268.75  4452.8  263.18  4535.5   262.6  4610.9  260.84
  4725.8  263.01  4868.4  262.85  4969.3  261.82  4978.8  260.64  4984.1  257.95
  4987.4  253.43  4990.1  252.93  4993.4  253.43  5000.9  253.53  5010.4  256.02
    5022  262.36  5032.5  263.64  5085.6   262.2  5264.2  260.89  5389.9  262.36
  5455.7  266.19  5579.2  276.08  5714.7  291.85  5784.8  295.98  6104.9  297.17
#Mann= 9 ,-1 , 0
  2819.3     .05       0  3917.1      .1       0  3948.6     .05       0
  4535.5     .16       0  4868.4     .12       0  4987.4     .07       0
  4993.4     .12       0  5085.6     .16       0  5264.2     .05       0
Bank Sta=4969.3,5032.5
XS Rating Curve= 0 ,0
Exp/Cntr=0.3,0.1

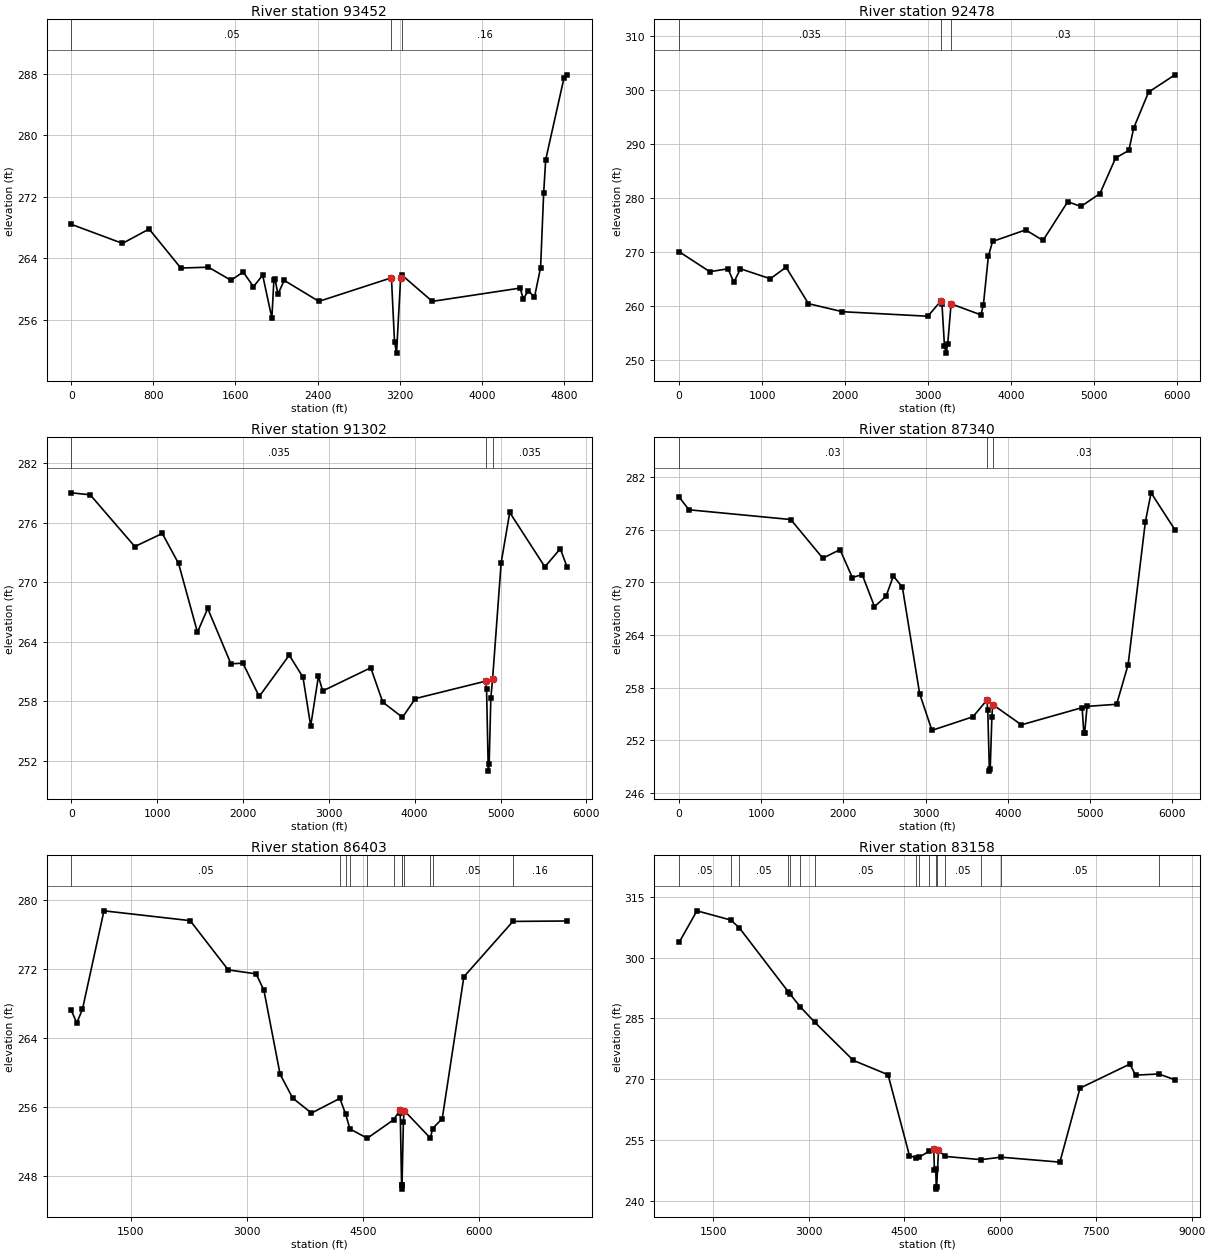
Type RM Length L Ch R = 1 ,93452   ,974,974,974
XS GIS Cut Line= 4
     3569967.883    10251553.679     3569672.744    10249808.887
     3569585.939     10248906.11     3568066.842    10247421.735
#Sta/Elev= 30
       0  268.42  498.69  265.94  758.01  267.81  1067.2  262.73 1336.49  262.84
 1555.91  261.14  1675.6  262.21 1775.34   260.3 1865.02   261.8  1954.7  256.22
 1974.62   261.2 1984.59  261.33 2014.48  259.32 2074.27  261.13 2413.06  258.39
 3120.24  261.46 3150.12  253.16 3170.04  251.65 3209.87  261.45 3219.83  261.84
 3518.57  258.39 4374.97  260.12 4404.85  258.72 4454.64  259.76 4514.39  258.94
 4574.13   262.8 4604.01  272.49 4623.92  276.84 4803.17  287.54 4833.05  287.89
#Mann= 3 ,-1 , 0
       0     .05       0 3120.24     .07       0 3219.83     .16       0
Bank Sta=3120.24,3209.87
XS Rating Curve= 0 ,0
Exp/Cntr=0.3,0.1

Type RM Length L Ch R = 1 ,92478   ,1176,1176,1176
XS GIS Cut Line= 4
     3570032.266    10251594.627     3570035.158    10247590.369
     3569778.213    10246472.313     3569097.658    10245791.758
#Sta/Elev= 30
       0  270.05  369.92  266.34  589.87  266.87  659.85  264.37  739.84  266.88
 1099.76  265.03 1289.71  267.17 1559.65  260.41 1969.56  258.92 2999.33  258.08
  3159.3  260.96  3169.3  260.44 3199.29  252.62 3219.28  251.24 3239.28  252.99
 3279.27  260.38 3639.19  258.33 3669.18  260.24 3729.17  269.22 3779.16  271.94
 4178.38  274.09 4387.43  272.13 4686.06  279.32 4845.34  278.43 5074.29  280.83
 5263.22  287.43 5422.08  288.82 5481.66  292.99 5660.37  299.63  5978.1  302.84
#Mann= 3 ,-1 , 0
       0    .035       0  3159.3     .07       0 3279.27     .03       0
Bank Sta=3159.3,3279.27
XS Rating Curve= 0 ,0
Exp/Cntr=0.3,0.1

Type RM Length L Ch R = 1 ,91302   ,3962,3962,3962
XS GIS Cut Line= 2
     3569962.821    10252723.099     3570891.641    10247124.141
#Sta/Elev= 30
       0  279.02  219.88  278.82  739.61   273.6 1059.44  274.92 1249.34  271.89
 1469.23  264.96 1589.16  267.35 1859.02  261.77 1998.95  261.83 2188.85  258.47
 2538.66  262.64 2698.58  260.42 2788.53   255.5 2878.48   260.5 2928.46  259.03
 3488.16  261.37 3628.09   257.9 3857.97  256.37 4007.89  258.26 4827.45  260.02
 4837.45  259.24 4857.44  250.94 4867.43  251.61 4887.42  258.35 4907.41   260.2
 5007.36  271.96 5107.29  277.04 5516.73  271.55 5696.48  273.38 5776.37  271.51
#Mann= 3 ,-1 , 0
       0    .035       0 4827.45     .07       0 4907.41    .035       0
Bank Sta=4827.45,4907.41
XS Rating Curve= 0 ,0
Exp/Cntr=0.3,0.1

Type RM Length L Ch R = 1 ,87340   ,937,937,937
XS GIS Cut Line= 2
     3573174.627    10254033.8633571912.0805483110248234.2948256
#Sta/Elev= 30
       0  279.71  119.93  278.26 1359.19  277.15 1748.96  272.75 1958.83  273.72
 2108.72  270.55 2228.61  270.88 2378.47  267.24 2518.34   268.4 2608.26  270.72
 2718.16  269.44 2927.97  257.33 3077.83  253.15 3577.37   254.7 3747.21   256.6
  3757.2  255.44 3777.18  248.51 3787.17  248.75 3807.15  254.62 3817.14  256.09
 4166.82  253.78 4906.14  255.74 4926.12  252.84 4936.11  252.81 4966.08  255.88
 5325.75  256.12 5465.62  260.63 5675.43  276.88 5745.36  280.19 6035.27  275.98
#Mann= 3 ,-1 , 0
       0     .03       0 3747.21     .07       0 3817.14     .03       0
Bank Sta=3747.21,3817.14
XS Rating Curve= 0 ,0
Exp/Cntr=0.3,0.1

Type RM Length L Ch R = 1 ,86403   ,3245,3245,3245
BEGIN DESCRIPTION:
WICKSON CREEK 43.0
END DESCRIPTION:
XS GIS Cut Line= 4
      3573856.51      10254011.7      3573661.19     10251082.02
      3573244.53     10248582.02      3572476.72     10248061.47
#Sta/Elev= 30
     735  267.21   805.2  265.76   878.3  267.34    1156  278.78  2268.5  277.64
  2759.5  271.92  3120.3  271.46  3220.6  269.53    3429   259.8  3591.4  257.04
  3833.8  255.29  4200.5     257    4276  255.13  4330.2  253.45  4553.8  252.37
  4896.7  254.53  4973.9  255.62  4979.4  255.25  4996.6  246.96  4999.4  246.46
  5002.6  246.96  5019.9   254.3  5029.3  255.55  5029.6  255.59    5369  252.38
  5396.4  253.49  5521.3  254.65  5800.5  271.12  6433.3  277.55  7133.3   277.6
#Mann= 12 ,-1 , 0
     735     .05       0  4200.5     .12       0    4276     .05       0
  4330.2     .12       0  4553.8     .05       0  4896.7     .16       0
  4996.6     .07       0  5002.6     .16       0  5029.3     .05       0
    5369     .12       0  5396.4     .05       0  6433.3     .16       0
Bank Sta=4973.9,5029.6
XS Rating Curve= 0 ,0
Exp/Cntr=0.3,0.1

Type RM Length L Ch R = 1 ,83158   ,2161,2161,2161
BEGIN DESCRIPTION:
WICKSON CREEK 42.0
END DESCRIPTION:
XS GIS Cut Line= 4
      3576551.82     10254441.42      3576030.98     10251212.23
      3574937.23      10248009.1      3573830.46     10247891.92
#Sta/Elev= 30
   968.3  303.76  1247.9  311.56  1778.7  309.29  1912.2  307.36  2682.2  291.52
  2702.5  291.12  2866.4  287.89  3095.9  284.04  3698.1  274.67  4242.2  271.13
    4578  251.15  4681.3  250.65  4722.8  250.73  4891.7  252.31  4958.1  252.82
    4969  247.71  4989.4  247.78  4997.7  243.41  5000.4  242.91  5003.7  243.41
  5032.4  252.49  5136.5  250.98  5699.7  250.18  6010.7  250.79  6934.4  249.57
  7249.6  267.82  8031.8  273.76  8119.5  271.03  8485.5  271.31  8736.9  269.88
#Mann= 16 ,-1 , 0
   968.3     .05       0  1778.7      .1       0  1912.2     .05       0
  2682.2      .1       0  2702.5     .05       0  2866.4      .1       0
  3095.9     .05       0  4681.3      .1       0  4722.8     .05       0
  4891.7     .16       0  4997.7     .07       0  5003.7     .16       0
  5136.5     .05       0  5699.7      .1       0  6010.7     .05       0
  8485.5     .16       0
Bank Sta=4958.1,5032.4
XS Rating Curve= 0 ,0
Exp/Cntr=0.3,0.1