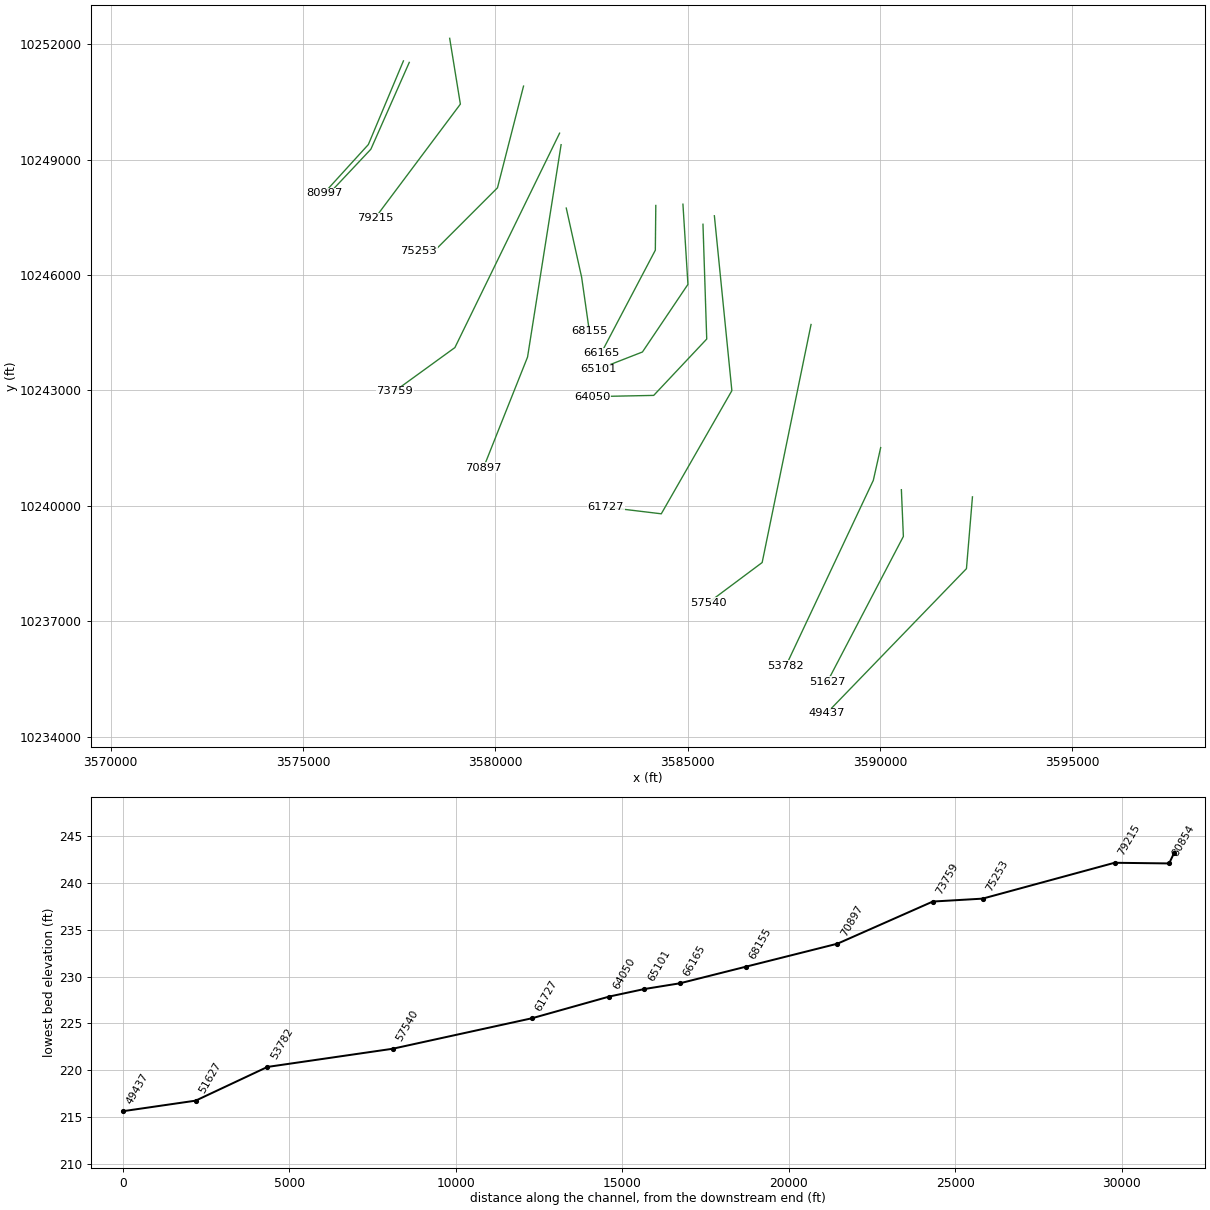
HEC-RAS study WICKSON CREEK.prj: WICKSON CREEK Base Level Engineering

--- WICKSON CREEK.g01 (geometry) --- (continued)

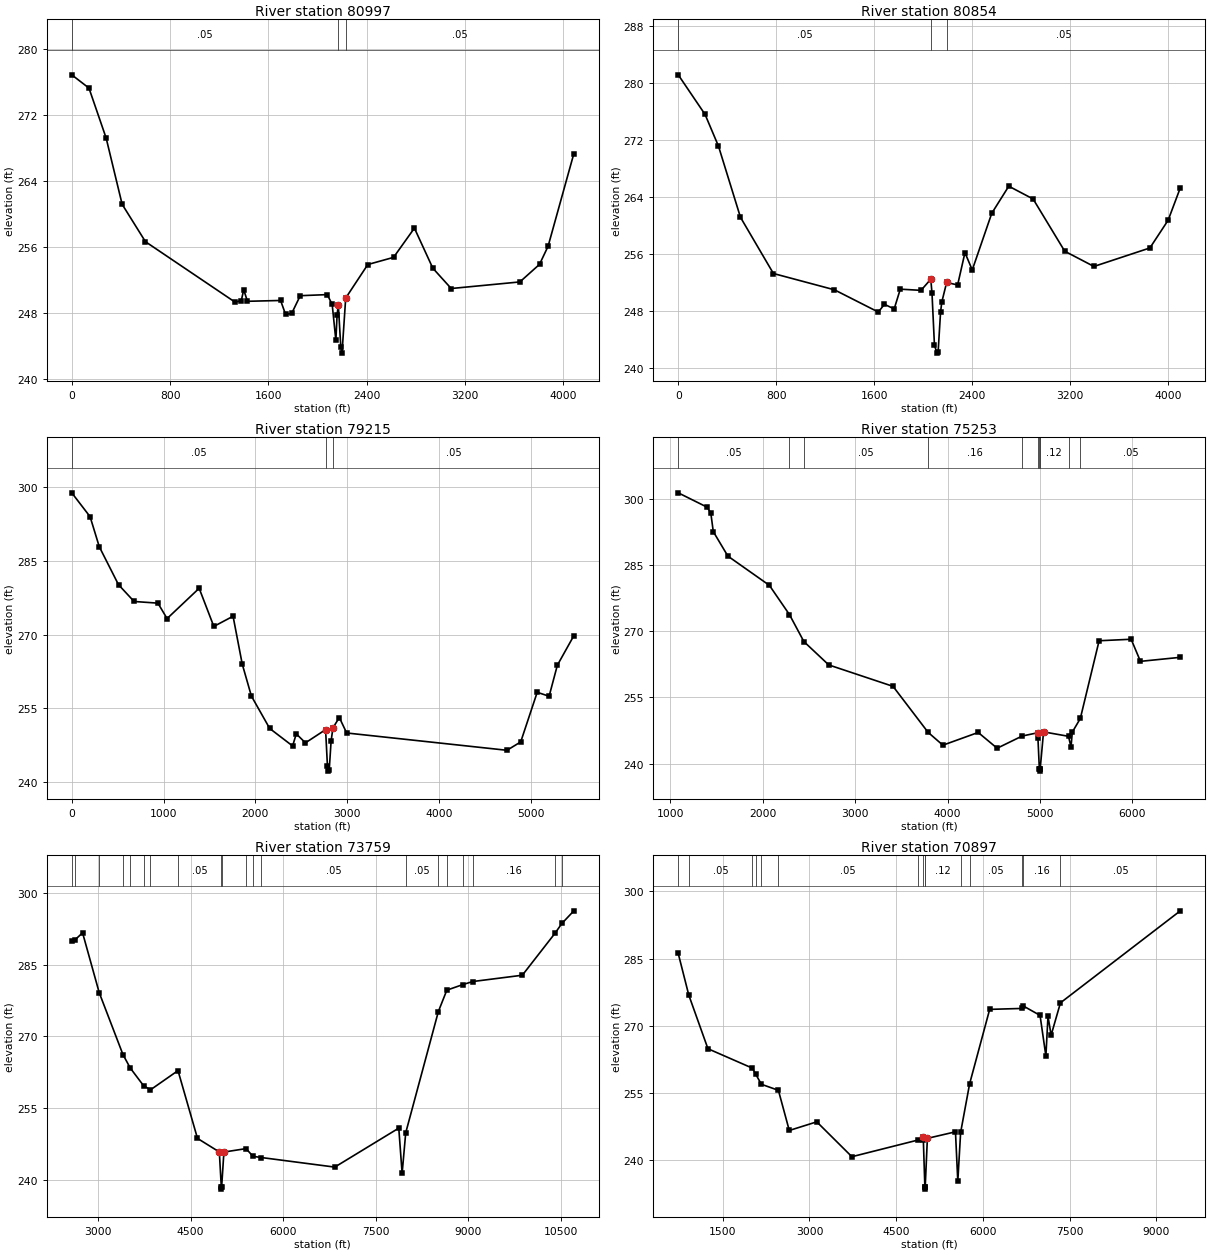
Type RM Length L Ch R = 1 ,80997   ,143,143,143
XS GIS Cut Line= 3
      3577609.53    10251568.229     3576698.071    10249393.749
     3575547.898    10248130.729
#Sta/Elev= 30
       0  276.92   139.9  275.31  279.79  269.24   409.7  261.21  599.55  256.67
 1329.01  249.33 1378.97  249.53 1398.96  250.84 1428.94  249.44 1698.74  249.54
 1738.71  247.87 1788.67  247.96 1858.62  250.12 2078.45  250.25 2118.42  249.06
  2148.4  244.69 2158.39  247.81 2168.39  248.98 2188.37  243.91 2198.37  243.15
 2228.34  249.83 2408.18   253.9 2617.69  254.77 2787.29  258.32 2936.94  253.46
  3086.6  250.99 3645.29  251.79 3804.92  253.92 3874.76  256.12 4084.27  267.36
#Mann= 3 ,-1 , 0
       0     .05       0 2168.39     .07       0 2228.34     .05       0
Bank Sta=2168.39,2228.34
XS Rating Curve= 0 ,0
Exp/Cntr=0.3,0.1

Type RM Length L Ch R = 1 ,80854   ,1639,1639,1639
XS GIS Cut Line= 3
     3577761.439    10251529.166     3576763.176    10249272.222
     3575656.405    10248096.006
#Sta/Elev= 30
       0  281.19  219.31  275.62  328.96  271.16  508.39  261.17  777.54  253.27
 1275.97  250.98 1634.83  247.85 1684.67  248.94 1764.42  248.29 1814.26  251.07
 1983.73   250.9 2063.48  252.47 2073.44  250.49 2093.38  243.21 2113.32  242.08
 2123.29  242.21 2143.22  247.81 2153.19  249.24 2193.07  252.01 2282.78  251.66
 2342.59   256.2  2402.4  253.77 2561.61  261.73 2700.77  265.54 2899.56  263.74
    3158   256.4 3396.55  254.26 3853.78  256.86 4002.88  260.76 4102.28  265.31
#Mann= 3 ,-1 , 0
       0     .05       0 2063.48     .04       0 2193.07     .05       0
Bank Sta=2063.48,2193.07
XS Rating Curve= 0 ,0
Exp/Cntr=0.3,0.1

Type RM Length L Ch R = 1 ,79215   ,3962,3962,3962
XS GIS Cut Line= 3
     3578811.787    10252154.166     3579089.564    10250444.097
     3576867.342    10247475.347
#Sta/Elev= 30
       0  298.91  199.72  294.04  299.57  287.92  509.28  280.17  679.04  276.75
  938.67  276.41 1038.53  273.26 1388.03  279.44  1547.8  271.66 1757.49  273.74
 1857.31  263.99 1957.13  257.46 2156.76  250.85  2406.3  247.28 2446.23  249.75
 2546.04  247.92 2765.64  250.61  2785.6  243.26 2795.58  242.15 2805.57  242.48
 2825.53  248.23 2845.49  250.97 2915.36  253.08 2995.22  249.93    4742   246.4
 4891.73  248.11  5071.4  258.23 5201.16  257.42 5290.99  263.75 5470.66  269.77
#Mann= 3 ,-1 , 0
       0     .05       0 2765.64     .03       0 2845.49     .05       0
Bank Sta=2765.64,2845.49
XS Rating Curve= 0 ,0
Exp/Cntr=0.3,0.1

Type RM Length L Ch R = 1 ,75253   ,1494,1494,1494
BEGIN DESCRIPTION:
WICKSON CREEK 40.0
END DESCRIPTION:
XS GIS Cut Line= 4
       3580731.5     10250912.73      3580054.42     10248269.52
      3578489.39     10246703.66      3578005.23      10246634.5
#Sta/Elev= 30
  1086.9  301.29  1397.7  298.06    1439  296.76  1466.1  292.51  1624.1  286.97
  2072.8  280.36  2290.3  273.73  2446.3  267.63  2715.2  262.35  3410.7   257.5
  3789.7   247.1  3949.9  244.19  4331.8  247.07  4536.8   243.5  4807.5  246.26
  4975.2     247  4978.3  245.75  4993.5  238.82  4996.2  238.32  4999.5  238.82
  5002.6  238.86  5038.9   247.2  5308.9   246.2  5335.9  243.76    5350  247.15
  5436.7  250.23  5639.9  267.82  5986.4  268.16  6087.2  263.16  6518.4  264.07
#Mann= 11 ,-1 , 0
  1086.9     .05       0  2290.3      .1       0  2446.3     .05       0
  3789.7     .16       0  4807.5     .12       0  4978.3     .16       0
  4993.5     .07       0  4999.5     .16       0  5002.6     .12       0
  5308.9     .16       0  5436.7     .05       0
Bank Sta=4975.2,5038.9
XS Rating Curve= 0 ,0
Exp/Cntr=0.3,0.1

Type RM Length L Ch R = 1 ,73759   ,2862,2862,2862
BEGIN DESCRIPTION:
WICKSON CREEK 39.0
END DESCRIPTION:
XS GIS Cut Line= 3
      3581669.02     10249688.81      3578947.65     10244115.87
      3577386.15     10242983.79
#Sta/Elev= 30
  2576.8  290.03    2631  290.22  2751.7  291.67  3021.5  279.13  3405.7  266.18
  3524.1  263.36  3740.1  259.65  3851.6   258.8  4297.2  262.82  4612.6  248.63
  4966.3  245.79  4998.1  238.51  5000.8  238.01  5004.1  238.51  5040.5  245.77
  5399.3  246.49  5510.8  244.88    5644  244.63  6835.9  242.62  7872.4  250.78
  7926.5   241.3  7984.8   249.8  8513.4  275.19  8650.3  279.66  8912.1  280.84
    9072  281.47  9873.2  282.79 10404.5  291.61 10513.2  293.62 10707.4  296.27
#Mann= 20 ,-1 , 0
  2576.8     .05       0    2631      .1       0  3021.5     .05       0
  3405.7     .16       0  3524.1     .05       0  3740.1      .1       0
  3851.6     .05       0  4297.2     .05       0  4998.1     .07       0
  5004.1     .12       0  5399.3     .05       0  5510.8     .12       0
    5644     .05       0  7984.8     .05       0  8513.4      .1       0
  8650.3     .16       0  8912.1      .1       0    9072     .16       0
 10404.5      .1       0 10513.2     .05       0
Bank Sta=4966.3,5040.5
XS Rating Curve= 0 ,0
Exp/Cntr=0.3,0.1

Type RM Length L Ch R = 1 ,70897   ,2742,2742,2742
BEGIN DESCRIPTION:
WICKSON CREEK 38.0
END DESCRIPTION:
XS GIS Cut Line= 3
      3581708.06     10249389.27      3580835.67     10243868.48
      3579689.85     10240990.91
#Sta/Elev= 30
   730.2  286.14   912.5  276.86    1244  264.87  2013.3  260.53  2068.5  259.23
  2168.5  256.93  2463.2  255.58  2651.4  246.61  3127.2  248.54  3734.6  240.75
  4870.9  244.45  4959.7  245.18  4970.9  244.48  4997.2  234.01  4999.9  233.51
  5003.2  234.01  5040.7  244.85  5526.6  246.31  5567.1  235.27    5616  246.17
  5771.6  257.04  6118.5  273.66  6683.1  273.87  6698.3  274.43  6990.1  272.32
  7091.1  263.24  7127.6  272.13  7181.6  267.89  7342.9  275.12  9416.8  295.67
#Mann= 15 ,-1 , 0
   730.2      .1       0   912.5     .05       0  2013.3     .16       0
  2068.5     .05       0  2168.5     .16       0  2463.2     .05       0
  4870.9      .1       0  4970.9     .12       0  4997.2     .07       0
  5003.2     .12       0    5616     .16       0  5771.6     .05       0
  6683.1      .1       0  6698.3     .16       0  7342.9     .05       0
Bank Sta=4959.7,5040.7
XS Rating Curve= 0 ,0
Exp/Cntr=0.3,0.1

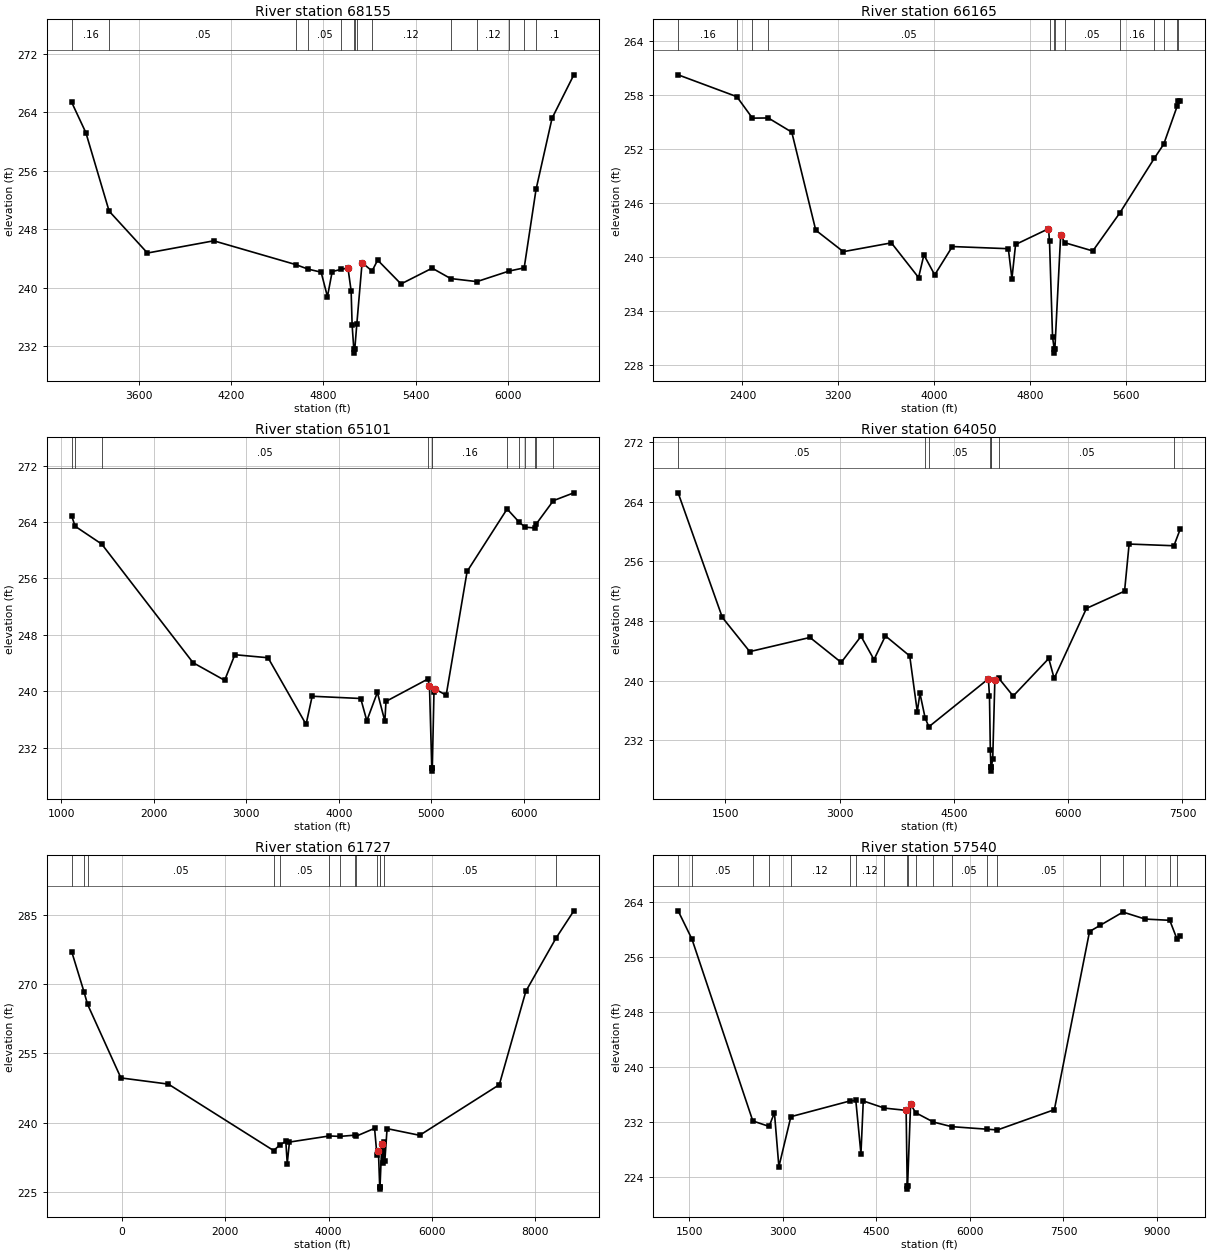
Type RM Length L Ch R = 1 ,68155   ,1990,1990,1990
BEGIN DESCRIPTION:
WICKSON CREEK 37.0
END DESCRIPTION:
XS GIS Cut Line= 3
       3581842.1     10247741.65      3582242.11     10245941.64
       3582442.1     10244541.67
#Sta/Elev= 30
  3166.1  265.37  3258.3  261.21  3409.2  250.48  3657.8  244.75  4088.1  246.42
  4619.7  243.17  4699.7  242.55  4784.7  242.13  4825.6  238.78  4856.4  242.21
  4916.7  242.53  4958.8   242.7  4979.3  239.58  4985.7  234.92  4996.8  231.56
  4999.5  231.06  5002.8  231.56  5016.4  235.09  5050.4  243.43  5115.1  242.29
  5151.4  243.78    5303  240.52    5505  242.68  5624.8  241.26  5795.3  240.84
  6003.3  242.28    6102  242.72    6179  253.45  6282.8  263.18  6424.2  269.12
#Mann= 14 ,-1 , 0
  3166.1     .16       0  3409.2     .05       0  4619.7     .16       0
  4699.7     .05       0  4916.7     .12       0  4996.8     .07       0
  5002.8     .12       0  5016.4     .16       0  5115.1     .12       0
  5624.8     .16       0  5795.3     .12       0  6003.3      .1       0
    6102     .16       0    6179      .1       0
Bank Sta=4958.8,5050.4
XS Rating Curve= 0 ,0
Exp/Cntr=0.3,0.1

Type RM Length L Ch R = 1 ,66165   ,1064,1064,1064
BEGIN DESCRIPTION:
WICKSON CREEK 35.0
END DESCRIPTION:
XS GIS Cut Line= 3
      3584169.71     10247809.75      3584157.59     10246647.27
      3582748.25     10243968.54
#Sta/Elev= 30
  1863.3  260.25    2353  257.82  2483.3  255.43  2615.4  255.45  2811.5  253.87
  3011.5  242.96  3241.5  240.57  3642.4  241.55  3869.3  237.69  3913.6  240.21
    4004  237.99  4150.9  241.14    4618   240.9    4648  237.57  4678.5  241.37
  4953.1  243.12  4961.6  241.71    4987  231.06  5000.4  229.78  5003.1  229.28
  5006.4  229.78  5054.8  242.46  5088.4  241.57  5322.7  240.65    5548  244.88
  5837.2  250.99  5914.3  252.53  6027.6   256.8  6034.5   257.3  6052.7  257.38
#Mann= 13 ,-1 , 0
  1863.3     .16       0    2353     .05       0  2483.3     .16       0
  2615.4     .05       0  4961.6     .16       0  5000.4     .07       0
  5006.4     .16       0  5088.4     .05       0    5548     .16       0
  5837.2     .05       0  5914.3     .16       0  6027.6     .05       0
  6034.5     .16       0
Bank Sta=4953.1,5054.8
XS Rating Curve= 0 ,0
Exp/Cntr=0.3,0.1

Type RM Length L Ch R = 1 ,65101   ,1051,1051,1051
BEGIN DESCRIPTION:
WICKSON CREEK 33.0
END DESCRIPTION:
XS GIS Cut Line= 4
        3584875.     10247842.27      3585005.21     10245758.94
      3583822.49     10244001.13      3582683.69     10243556.45
#Sta/Elev= 30
    1111  264.86  1148.6   263.4  1436.1  260.87  2423.2  244.05  2764.9  241.55
  2875.1  245.18  3234.1  244.75    3645   235.3  3710.9  239.29  4235.8  238.97
  4301.8  235.81  4415.8  239.84  4496.8  235.75  4508.9  238.56  4960.3  241.72
    4979  240.81  5003.7  229.17  5006.4  228.67  5009.7  229.17  5027.7  239.89
  5036.6  240.33  5159.6  239.44  5385.8  256.99  5818.2  265.85  5946.4  264.01
    6012  263.27  6122.2  263.15    6133  263.72  6318.3  267.03  6539.6  268.14
#Mann= 12 ,-1 , 0
    1111     .05       0  1148.6     .16       0  1436.1     .05       0
  4960.3     .16       0  5003.7     .07       0  5009.7     .16       0
  5818.2     .16       0  5946.4     .05       0    6012     .16       0
  6122.2     .05       0    6133     .16       0  6318.3     .05       0
Bank Sta=4979,5036.6
XS Rating Curve= 0 ,0
Exp/Cntr=0.3,0.1

Type RM Length L Ch R = 1 ,64050   ,2323,2323,2323
BEGIN DESCRIPTION:
WICKSON CREEK 31.0
END DESCRIPTION:
XS GIS Cut Line= 4
      3585395.84     10247321.49      3585493.49      10244337.5
      3584115.46     10242872.66      3582520.43      10242840.1
#Sta/Elev= 30
   879.2   265.2  1459.4  248.49  1819.5   243.9    2610   245.8  3020.2  242.45
  3280.3  245.96  3450.4  242.83  3600.5  246.01  3919.4  243.32  4018.5  235.85
  4053.7   238.3  4121.8     235  4170.6  233.82  4952.3  240.25  4966.5  237.89
  4977.7  230.65  4984.5  228.37  4987.3  227.87  4990.5  228.37    5009  229.53
  5037.3  240.15    5090  240.31  5277.6  237.94  5744.5  242.98  5815.4   240.3
  6239.4   249.7  6739.5  252.01  6799.5  258.33  7387.5   258.1  7471.3  260.36
#Mann= 8 ,-1 , 0
   879.2     .05       0  4121.8     .16       0  4170.6     .05       0
  4977.7     .16       0  4984.5     .07       0  4990.5     .16       0
    5090     .05       0  7387.5      .1       0
Bank Sta=4952.3,5037.3
XS Rating Curve= 0 ,0
Exp/Cntr=0.3,0.1

Type RM Length L Ch R = 1 ,61727   ,4187,4187,4187
BEGIN DESCRIPTION:
WICKSON CREEK 30.0
END DESCRIPTION:
XS GIS Cut Line= 4
       3585692.1     10247541.67      3586146.72     10242995.49
      3584312.21     10239794.68      3582871.25     10239968.28
#Sta/Elev= 30
  -967.8  277.11  -730.5  268.42    -660  265.64   -15.5  249.68   901.5  248.34
  2936.6  233.92  3061.6  235.16  3172.8  235.92  3200.4  231.11  3243.1  235.76
  4015.3  237.09  4217.3  236.99  4516.2  237.27  4537.7  237.06    4889  238.74
    4935  232.94  4963.8  233.76  4988.1  226.05  4990.9  225.55  4994.1  226.05
  5028.5  235.27  5044.4  231.23  5076.3  235.67  5087.5  231.68  5130.7  238.68
  5760.9  237.23  7300.5  248.21  7814.2  268.49  8394.5  279.97  8741.7  285.94
#Mann= 14 ,-1 , 0
  -967.8     .05       0  -730.5      .1       0    -660     .05       0
  2936.6     .12       0  3061.6     .05       0  4015.3     .16       0
  4217.3     .05       0  4516.2     .16       0  4537.7     .05       0
    4935     .16       0  4988.1     .07       0  4994.1     .16       0
  5076.3     .05       0  8394.5      .1       0
Bank Sta=4963.8,5028.5
XS Rating Curve= 0 ,0
Exp/Cntr=0.3,0.1

Type RM Length L Ch R = 1 ,57540   ,3758,3758,3758
BEGIN DESCRIPTION:
Mapping XS c13d5a63
END DESCRIPTION:
XS GIS Cut Line= 3
      3588205.18     10244715.37      3586934.35     10238527.88
      3585538.77      10237486.4
#Sta/Elev= 30
  1317.6  262.78  1539.7  258.66    2516  232.21  2777.9  231.41  2862.9  233.42
  2934.4  225.55  3126.9  232.83  4067.6   235.1  4168.7   235.2  4251.3  227.43
  4288.7  235.12  4626.6  234.08  4976.1  233.75  4993.6  222.79  4996.3  222.29
  4999.6  222.79  5047.6  234.64  5130.9   233.4  5413.3  232.05  5706.1  231.38
  6272.6  231.01  6440.8   230.9  7354.8  233.85  7919.2  259.77  8086.1  260.65
  8455.6   262.6  8810.8  261.58  9206.5   261.4  9320.9  258.71  9375.6  259.16
#Mann= 20 ,-1 , 0
  1317.6     .16       0  1539.7     .05       0    2516     .05       0
  2777.9     .12       0  3126.9     .12       0  4067.6     .05       0
  4168.7     .12       0  4626.6     .16       0  4993.6     .07       0
  4999.6     .16       0  5130.9     .05       0  5413.3      .1       0
  5706.1     .05       0  6272.6      .1       0  6440.8     .05       0
  8086.1      .1       0  8455.6     .05       0  8810.8      .1       0
  9206.5      .1       0  9320.9     .05       0
Bank Sta=4976.1,5047.6
XS Rating Curve= 0 ,0
Exp/Cntr=0.3,0.1

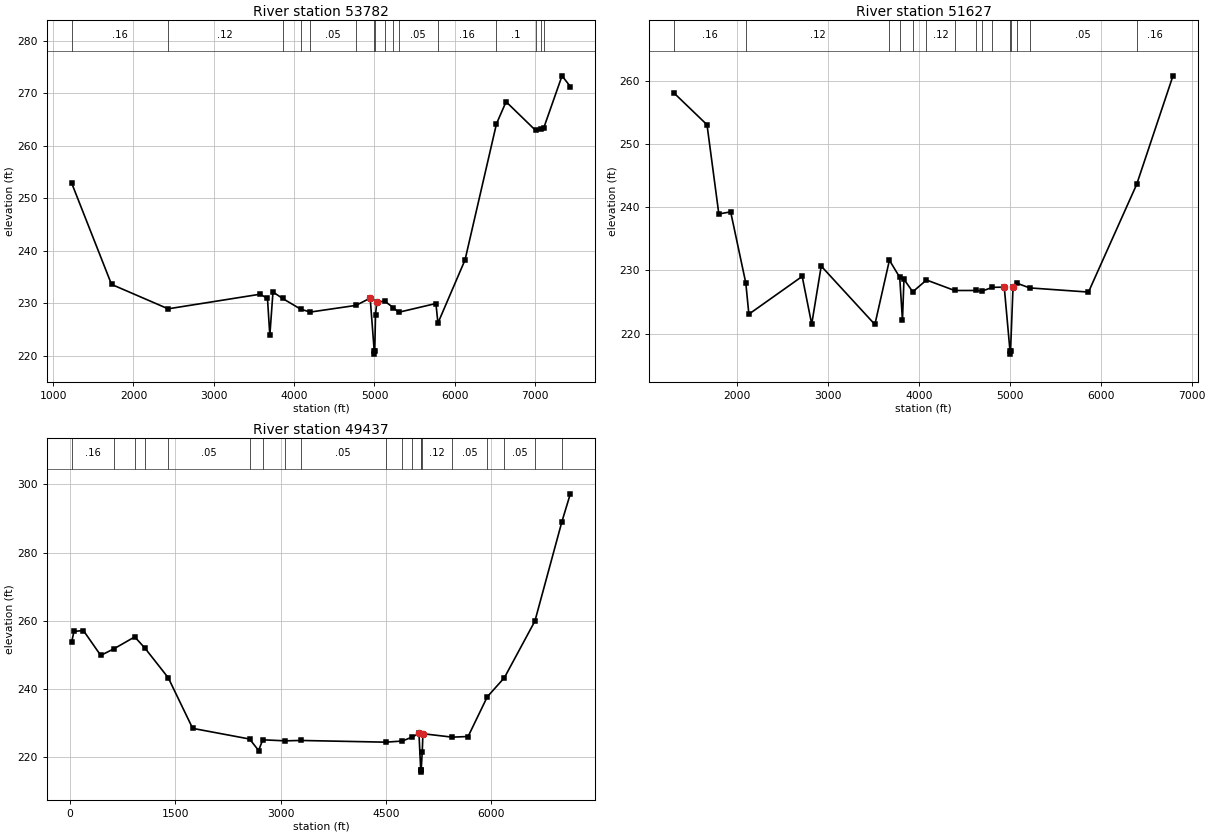
Type RM Length L Ch R = 1 ,53782   ,2155,2155,2155
BEGIN DESCRIPTION:
Mapping XS 5e6967f8
END DESCRIPTION:
XS GIS Cut Line= 3
      3590015.01     10241515.43      3589824.03     10240664.71
      3587549.73     10235838.32
#Sta/Elev= 30
  1230.2  252.92    1727  233.62  2431.7  228.97  3577.1  231.75  3668.2  230.95
  3697.4  223.91  3736.6  232.17  3856.5  230.94  4080.8  228.91  4199.4  228.35
  4768.2  229.62  4946.5     231  4997.1  220.85  4999.8  220.35  5003.1  220.85
  5012.9  227.84  5028.4   230.2  5125.3  230.46  5235.9  229.17  5300.4  228.31
  5764.6  229.98  5789.7  226.25  6126.9  238.27  6518.5  264.18  6637.9  268.37
  7006.5   262.9  7073.7   263.1  7108.2  263.45  7334.3   273.3  7437.5  271.26
#Mann= 16 ,-1 , 0
  1230.2     .16       0  2431.7     .12       0  3856.5     .16       0
  4080.8      .1       0  4199.4     .05       0  4768.2     .16       0
  4997.1     .07       0  5003.1     .16       0  5125.3     .05       0
  5235.9     .16       0  5300.4     .05       0  5789.7     .16       0
  6518.5      .1       0  7006.5     .16       0  7073.7     .05       0
  7108.2     .16       0
Bank Sta=4946.5,5028.4
XS Rating Curve= 0 ,0
Exp/Cntr=0.3,0.1

Type RM Length L Ch R = 1 ,51627   ,2190,2190,2190
BEGIN DESCRIPTION:
Mapping XS a3ced9d5
END DESCRIPTION:
XS GIS Cut Line= 3
       3590553.2     10240421.62      3590605.28     10239206.37
      3588626.59     10235422.57
#Sta/Elev= 30
  1308.2  258.03  1668.5  253.05  1798.6  238.93  1928.7  239.26  2095.4  227.99
  2128.9  223.07  2715.5  229.05  2820.2  221.49  2924.9  230.68  3515.3  221.44
  3675.1  231.61  3788.3  228.91  3818.7  222.09  3835.1   228.6  3931.7  226.61
    4083  228.48  4392.4  226.82  4622.6  226.82  4693.9  226.72  4807.1  227.32
  4938.4  227.35  5001.6  217.25  5004.3  216.75  5007.6  217.25  5035.1  227.44
  5074.6  227.99  5217.1  227.23    5865  226.57  6394.9   243.6  6794.5  260.79
#Mann= 15 ,-1 , 0
  1308.2     .16       0  2095.4     .12       0  3675.1     .05       0
  3788.3     .12       0  3931.7     .16       0    4083     .12       0
  4392.4     .16       0  4622.6     .05       0  4693.9     .16       0
  4807.1     .12       0  5001.6     .07       0  5007.6     .12       0
  5074.6     .16       0  5217.1     .05       0  6394.9     .16       0
Bank Sta=4938.4,5035.1
XS Rating Curve= 0 ,0
Exp/Cntr=0.3,0.1

Type RM Length L Ch R = 1 ,49437   ,634,634,634
BEGIN DESCRIPTION:
WICKSON CREEK 29.0
END DESCRIPTION:
XS GIS Cut Line= 3
      3592401.05     10240235.23       3592244.8     10238368.89
      3588607.39     10234606.86
#Sta/Elev= 30
    23.3  253.73      57   256.9   191.4  257.16   438.3  249.86   629.3  251.83
   922.7  255.29  1070.1  251.95    1400  243.31  1748.3  228.46  2559.4  225.33
  2688.1  221.95  2746.3   225.1  3068.2   224.8  3287.5  224.91  4501.4  224.41
  4735.1  224.74  4879.8  225.94  4972.5  226.99  4997.8  216.12  5000.5  215.62
  5003.8  216.12  5019.2  221.54  5029.1  226.89  5445.4  225.88  5672.7  226.07
  5945.8  237.71  6189.8  243.33  6624.4  259.92  7008.1  289.02  7129.1  297.26
#Mann= 20 ,-1 , 0
    23.3     .16       0   629.3     .05       0   922.7      .1       0
  1070.1     .16       0    1400     .05       0  2559.4     .16       0
  2746.3     .05       0  3068.2      .1       0  3287.5     .05       0
  4501.4     .16       0  4735.1      .1       0  4879.8     .12       0
  4997.8     .07       0  5003.8     .12       0  5019.2     .12       0
  5445.4     .05       0  5945.8     .16       0  6189.8     .05       0
  6624.4     .16       0  7008.1     .05       0
Bank Sta=4972.5,5029.1
XS Rating Curve= 0 ,0
Exp/Cntr=0.3,0.1