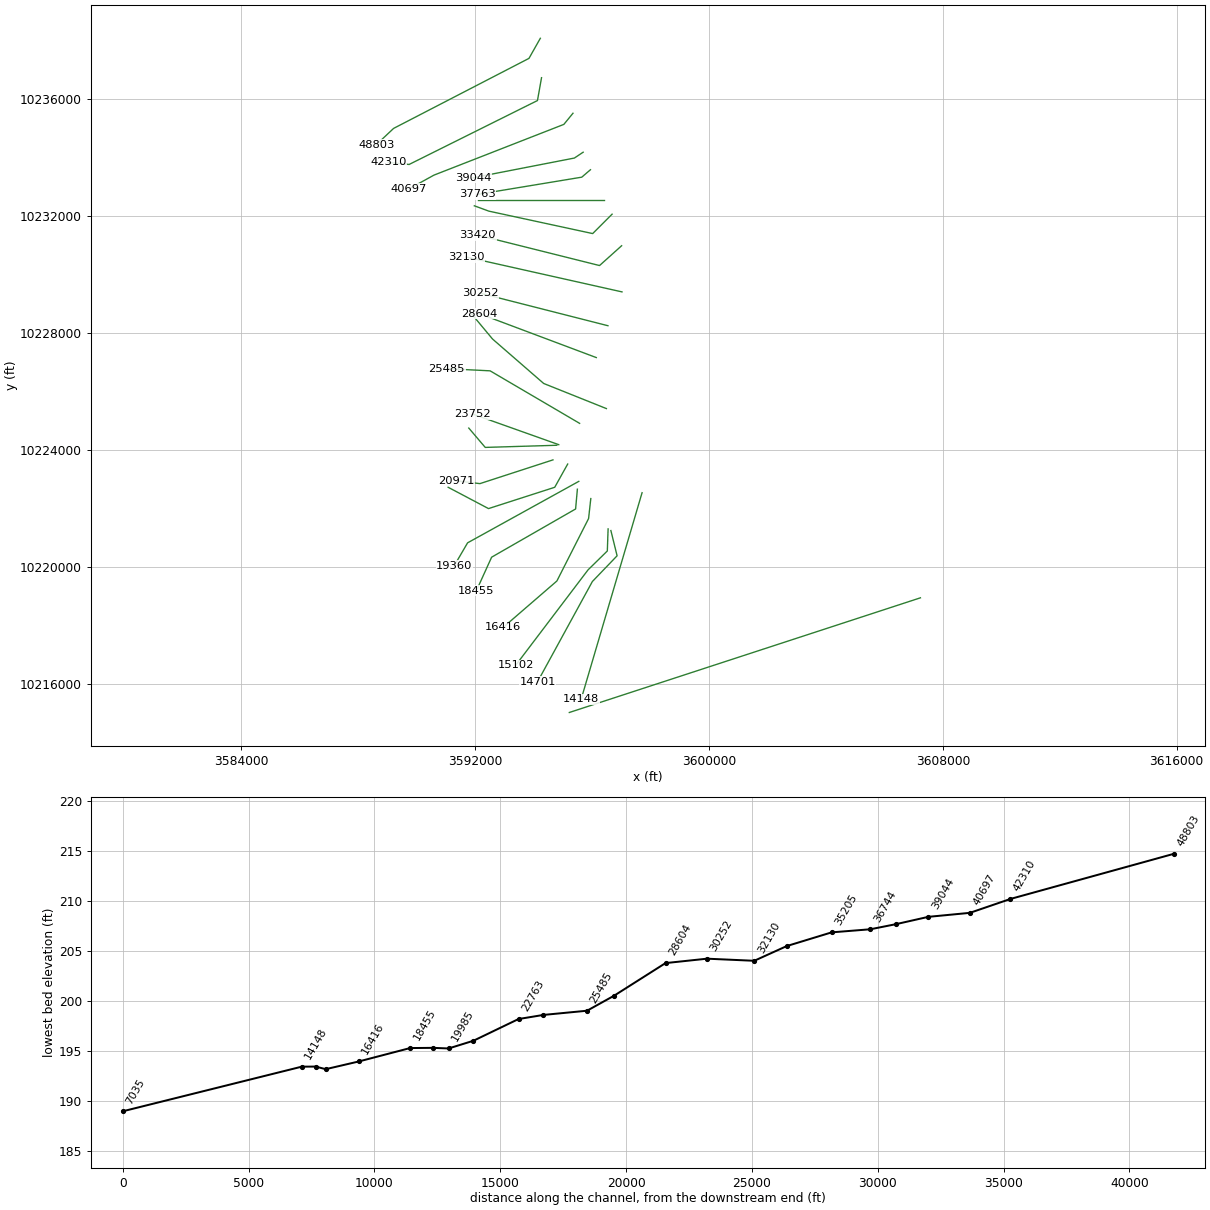
HEC-RAS study WICKSON CREEK.prj: WICKSON CREEK Base Level Engineering

--- WICKSON CREEK.g01 (geometry) --- (continued)

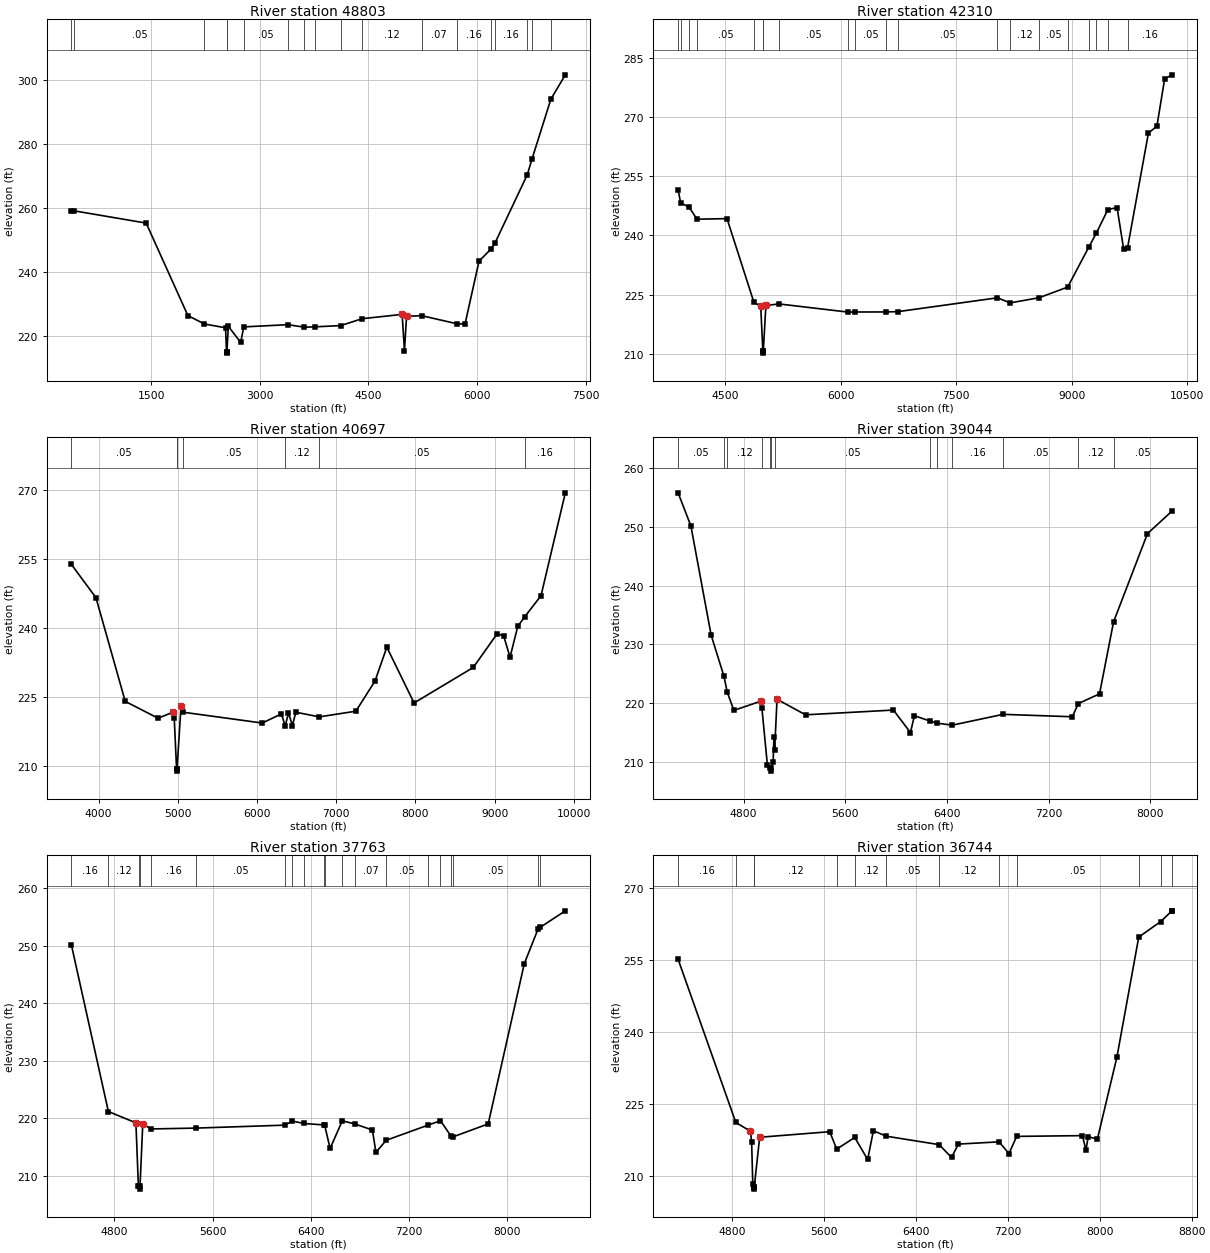
Type RM Length L Ch R = 1 ,48803   ,6493,6493,6493
BEGIN DESCRIPTION:
Mapping XS 652524df
END DESCRIPTION:
XS GIS Cut Line= 4
      3594227.44     10238089.38      3593838.55     10237401.88
       3589206.6     10235006.05      3588609.35     10234443.52
#Sta/Elev= 30
   394.8  259.12   436.9  259.14  1428.3  255.33  2004.8  226.43  2233.1   223.8
  2524.9  222.62  2538.5   215.2  2541.2   214.7  2544.5   215.2  2563.6   223.1
  2734.3  218.03    2777  222.89  3384.3  223.59  3615.7   222.8  3757.5  222.91
    4116   223.3  4411.4  225.45  4965.4  226.81  4997.3  215.43  5026.2  226.21
  5235.8   226.4  5718.5  223.89  5834.2   223.8  6027.8  243.45  6199.5  247.37
  6251.3  249.26  6694.4  270.44    6759   275.3  7020.6  294.07    7220  301.65
#Mann= 18 ,-1 , 0
   394.8     .16       0   436.9     .05       0  2233.1     .16       0
  2538.5     .07       0  2544.5     .16       0    2777     .05       0
  3384.3      .1       0  3615.7     .16       0  3757.5      .1       0
    4116     .05       0  4411.4     .12       0  5235.8     .07       0
  5718.5     .16       0  6199.5     .05       0  6251.3     .16       0
  6694.4     .05       0    6759     .16       0  7020.6     .05       0
Bank Sta=4965.4,5026.2
XS Rating Curve= 0 ,0
Exp/Cntr=0.3,0.1

Type RM Length L Ch R = 1 ,42310   ,1613,1613,1613
BEGIN DESCRIPTION:
WICKSON CREEK 28.0
END DESCRIPTION:
XS GIS Cut Line= 4
      3594268.47     10236741.08      3594129.59     10235959.84
      3589737.23     10233772.34      3589026.22     10233841.71
#Sta/Elev= 30
  3890.3  251.59  3923.1  248.22  4031.4  247.23  4135.6  244.12  4525.5  244.26
  4875.5  223.02    4963  222.13  4990.8  210.69  4993.5  210.19  4996.8  210.69
  5030.2  222.26  5200.2  222.65  6094.7  220.59  6193.3  220.61  6590.7  220.62
  6748.9  220.71  8036.3   224.2  8203.6  222.92  8577.2  224.22  8949.6  226.92
  9226.3  237.15  9320.4  240.54    9471  246.54  9590.7  247.07  9676.2  236.55
  9726.9  236.86  9997.8  265.92 10108.3  267.69 10208.8  279.69 10305.1  280.69
#Mann= 20 ,-1 , 0
  3890.3      .1       0  3923.1     .05       0  4031.4      .1       0
  4135.6     .05       0  4875.5     .16       0  4990.8     .07       0
  4996.8     .16       0  5200.2     .05       0  6094.7      .1       0
  6193.3     .05       0  6590.7      .1       0  6748.9     .05       0
  8036.3     .16       0  8203.6     .12       0  8577.2     .05       0
  8949.6     .16       0  9226.3     .16       0  9320.4     .12       0
    9471     .16       0  9726.9     .16       0
Bank Sta=4963,5030.2
XS Rating Curve= 0 ,0
Exp/Cntr=0.3,0.1

Type RM Length L Ch R = 1 ,40697   ,1653,1653,1653
BEGIN DESCRIPTION:
WICKSON CREEK 27.0
END DESCRIPTION:
XS GIS Cut Line= 4
      3595344.86     10235525.81      3595032.36     10235143.87
      3590587.92     10233407.76      3589737.21       10232939.
#Sta/Elev= 30
  3655.3   253.8    3966  246.54  4335.3  223.98  4750.7  220.31  4943.6  221.67
  4954.3  220.28  4983.5   209.3  4986.2   208.8  4989.5   209.3  5040.1  223.02
  5066.6  221.62  6065.2  219.27    6307  221.26  6355.6  218.62  6396.5  221.48
  6445.5  218.72  6489.5  221.62  6784.5  220.61  7246.6  221.84  7487.9  228.37
  7638.2  235.77  7981.8  223.64  8729.4  231.36  9030.8   238.7  9112.2  238.26
  9193.6  233.61  9291.1   240.3  9380.5  242.43  9584.6  246.98  9891.6  269.37
#Mann= 7 ,-1 , 0
  3655.3     .05       0  4983.5     .07       0  4989.5     .05       0
  5066.6     .05       0  6355.6     .12       0  6784.5     .05       0
  9380.5     .16       0
Bank Sta=4943.6,5040.1
XS Rating Curve= 0 ,0
Exp/Cntr=0.3,0.1

Type RM Length L Ch R = 1 ,39044   ,1281,1281,1281
BEGIN DESCRIPTION:
WICKSON CREEK 25.0
END DESCRIPTION:
XS GIS Cut Line= 3
      3595692.09     10234191.63      3595392.92     10233992.19
      3591932.33     10233318.55
#Sta/Elev= 30
  4285.5   255.8  4386.1  250.15  4545.4  231.55  4645.3  224.62  4672.3  221.82
  4724.4  218.75    4936  220.31  4944.8  219.09  4987.6  209.47  5009.6   208.9
  5012.4   208.4  5015.6   208.9    5033  210.01  5039.3  214.27  5044.6  211.96
  5063.6  220.64  5287.7  217.99  5978.9   218.8  6112.9  214.97    6144  217.84
  6268.2  216.92  6319.7  216.58  6442.1  216.23  6841.4  218.07  7386.4  217.66
  7432.9   219.9  7600.1  221.56  7710.4  233.82  7977.3  248.86  8170.6   252.7
#Mann= 13 ,-1 , 0
  4285.5     .05       0  4645.3     .16       0  4672.3     .12       0
  4944.8     .16       0  5009.6     .07       0  5015.6     .16       0
  5044.6     .05       0  6268.2     .07       0  6319.7     .05       0
  6442.1     .16       0  6841.4     .05       0  7432.9     .12       0
  7710.4     .05       0
Bank Sta=4936,5063.6
XS Rating Curve= 0 ,0
Exp/Cntr=0.3,0.1

Type RM Length L Ch R = 1 ,37763   ,1019,1019,1019
BEGIN DESCRIPTION:
WICKSON CREEK 24.0
END DESCRIPTION:
XS GIS Cut Line= 3
      3595942.11     10233591.64      3595645.05      10233337.8
       3592062.5     10232745.63
#Sta/Elev= 30
  4450.4  250.18  4751.8  221.17  4975.9   219.2  4996.2  208.17  5003.3  208.17
    5006  207.67  5009.3  208.17  5031.9  219.07  5096.2  218.14  5467.1  218.29
  6187.1   218.8  6249.5  219.51  6346.2  219.09  6505.4  218.84  6513.1  218.76
  6557.1  214.74  6656.4  219.56  6759.6     219  6901.7  217.95  6930.1  214.07
    7014  216.17  7356.2  218.82  7455.6  219.57  7542.1  216.89    7555  216.74
  7844.3  219.02  8138.2   246.9    8251  252.97  8267.3  253.21  8472.3  256.09
#Mann= 20 ,-1 , 0
  4450.4     .16       0  4751.8     .12       0  5003.3     .07       0
  5009.3     .12       0  5096.2     .16       0  5467.1     .05       0
  6187.1     .12       0  6249.5     .05       0  6346.2     .12       0
  6505.4     .16       0  6513.1     .12       0  6656.4     .16       0
  6759.6     .07       0    7014     .05       0  7356.2     .16       0
  7455.6     .05       0  7542.1     .16       0    7555     .05       0
    8251      .1       0  8267.3     .16       0
Bank Sta=4975.9,5031.9
XS Rating Curve= 0 ,0
Exp/Cntr=0.3,0.1

Type RM Length L Ch R = 1 ,36744   ,1539,1539,1539
BEGIN DESCRIPTION:
WICKSON CREEK 23.0
END DESCRIPTION:
XS GIS Cut Line= 3
      3596392.07     10232541.64      3595692.11     10232541.64
      3592092.07     10232541.64
#Sta/Elev= 30
  4329.5  255.14    4832  221.07  4959.5  219.25  4969.5  217.01  4979.5  208.28
  4986.5  207.66  4989.2  207.16  4992.5  207.66  5039.5  217.99  5649.5  219.15
  5709.9  215.51  5867.2  217.95  5979.5  213.35  6029.5  219.35  6141.3  218.21
  6601.7  216.45  6709.5  213.77  6769.5  216.56  7123.3  217.03  7209.5  214.59
    7277  218.17  7849.5  218.33  7879.5   215.3  7899.5  218.09  7979.5  217.62
  8149.5  234.74  8339.4  259.78    8530  263.01  8628.8  265.26  8629.5  265.26
#Mann= 13 ,-1 , 0
  4329.5     .16       0    4832     .12       0  4986.5     .07       0
  4992.5     .12       0  5709.9     .16       0  5867.2     .12       0
  6141.3     .05       0  6601.7     .12       0  7123.3     .07       0
    7277     .05       0  8339.4     .16       0    8530     .05       0
  8628.8     .16       0
Bank Sta=4959.5,5039.5
XS Rating Curve= 0 ,0
Exp/Cntr=0.3,0.1

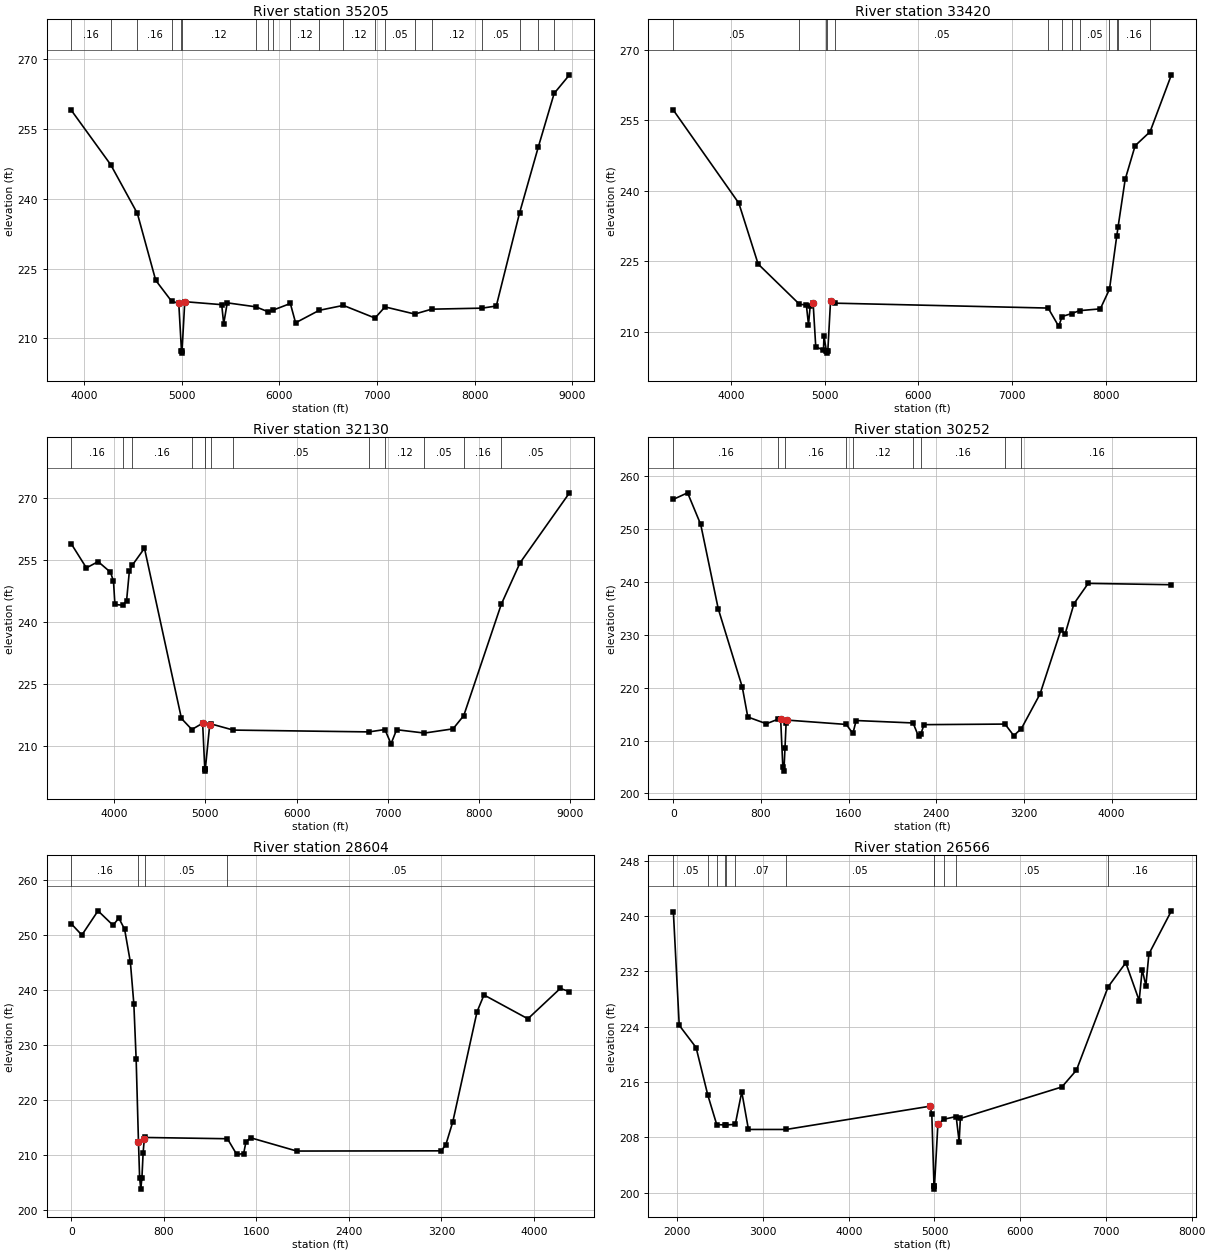
Type RM Length L Ch R = 1 ,35205   ,1785,1785,1785
BEGIN DESCRIPTION:
WICKSON CREEK 22.0
END DESCRIPTION:
XS GIS Cut Line= 4
       3596683.1     10232071.84      3596019.02     10231407.76
      3592464.33     10232175.99      3591969.55     10232358.28
#Sta/Elev= 30
  3868.5  259.02  4270.8  247.36  4543.9  236.89    4732   222.5  4895.6  217.98
  4968.2  217.59  4995.9  207.35  4998.6  206.85  5001.9  207.35  5029.6  217.91
  5408.1  217.27  5428.6  213.15  5464.7  217.66  5756.7  216.81  5886.6  215.72
  5929.1  216.05  6111.4  217.52  6165.2  213.37  6406.9  216.05  6654.9  217.11
  6979.2  214.39  7081.1  216.79  7386.7  215.25  7559.1   216.3  8075.6  216.52
  8221.6  216.98  8460.2  236.99    8651  251.08  8814.6  262.69  8971.7  266.68
#Mann= 20 ,-1 , 0
  3868.5     .16       0  4270.8      .1       0  4543.9     .16       0
  4895.6     .12       0  4995.9     .07       0  5001.9     .12       0
  5756.7     .16       0  5886.6     .05       0  5929.1     .16       0
  6111.4     .12       0  6406.9     .16       0  6654.9     .12       0
  6979.2     .16       0  7081.1     .05       0  7386.7     .07       0
  7559.1     .12       0  8075.6     .05       0  8460.2     .16       0
    8651     .05       0  8814.6     .16       0
Bank Sta=4968.2,5029.6
XS Rating Curve= 0 ,0
Exp/Cntr=0.3,0.1

Type RM Length L Ch R = 1 ,33420   ,1290,1290,1290
BEGIN DESCRIPTION:
WICKSON CREEK 20.0
END DESCRIPTION:
XS GIS Cut Line= 3
      3597008.63     10230991.12      3596253.39     10230314.01
      3592086.95     10231355.62
#Sta/Elev= 30
  3388.8  257.14  4086.9  237.35  4292.5  224.42  4732.9  215.87  4806.5  215.71
  4829.3  211.52  4847.7  215.54  4878.6  216.16  4906.6  206.85    4989  206.09
  4994.2  209.07  5019.9  205.98  5022.7  205.48  5025.9  205.98  5035.4     206
  5064.2  216.49  5111.9   216.1  7383.9  215.06  7496.8  211.17  7531.8  213.26
  7635.1  213.89  7718.2  214.51    7940  214.89  8037.9  219.07  8114.6  230.28
  8129.3   232.3  8205.1  242.41  8311.1  249.57  8470.4  252.54  8697.8  264.64
#Mann= 13 ,-1 , 0
  3388.8     .05       0  4732.9     .16       0  5019.9     .07       0
  5025.9     .16       0  5111.9     .05       0  7383.9     .16       0
  7531.8     .05       0  7635.1     .16       0  7718.2     .05       0
  8037.9     .16       0  8114.6     .07       0  8129.3     .16       0
  8470.4     .05       0
Bank Sta=4878.6,5064.2
XS Rating Curve= 0 ,0
Exp/Cntr=0.3,0.1

Type RM Length L Ch R = 1 ,32130   ,1878,1878,1878
BEGIN DESCRIPTION:
WICKSON CREEK 19.0
END DESCRIPTION:
XS GIS Cut Line= 2
        3597022.     10229412.42      3591692.11     10230606.01
#Sta/Elev= 30
  3531.3  258.88  3695.2  253.13  3824.2  254.64  3959.5  252.08  3992.3  249.93
    4008  244.29  4091.5  244.11  4135.8  245.17  4166.5  252.35  4197.3  253.73
  4332.1  257.88  4737.8  216.73  4851.7  214.07  4970.1  215.59  4993.6  204.51
  4996.4  204.01  4999.6  204.51  5047.8  215.27  5060.3  215.43  5306.7  213.93
  6793.8  213.49  6969.2  214.06  7035.9  210.61  7097.4  214.02  7402.9  213.21
  7716.1  214.23  7833.6  217.43  8245.4  244.35  8451.1  254.36  8993.2  271.27
#Mann= 13 ,-1 , 0
  3531.3     .16       0  4091.5      .1       0  4197.3     .16       0
  4851.7     .12       0  4993.6     .07       0  4999.6     .12       0
  5060.3     .16       0  5306.7     .05       0  6793.8     .16       0
  6969.2     .12       0  7402.9     .05       0  7833.6     .16       0
  8245.4     .05       0
Bank Sta=4970.1,5047.8
XS Rating Curve= 0 ,0
Exp/Cntr=0.3,0.1

Type RM Length L Ch R = 1 ,30252   ,1648,1648,1648
XS GIS Cut Line= 2
     3596541.328    10228254.861     3592161.988    10229370.312
#Sta/Elev= 30
       0  255.57  129.87   256.8  249.74  250.82  409.58   234.9  629.36  220.07
   679.3  214.45  849.13  213.17  959.02  214.06     979  214.16  998.98  205.04
 1008.97  204.22 1018.96  208.67 1028.95  213.23 1038.94  213.86 1578.39  213.04
 1638.32  211.33 1668.29  213.78 2187.76  213.32 2237.71  210.78 2257.69  211.17
 2287.66     213  3026.9  213.11 3106.82  210.92 3176.75  212.27 3346.58   218.8
 3536.38  230.85 3576.34   230.2 3656.26  235.86 3786.13  239.69 4545.35  239.44
#Mann= 9 ,-1 , 0
       0     .16       0  959.02     .07       0 1018.96     .16       0
 1578.39     .05       0 1638.32     .12       0 2187.76     .05       0
 2257.69     .16       0  3026.9     .07       0 3176.75     .16       0
Bank Sta=979,1038.94
XS Rating Curve= 0 ,0
Exp/Cntr=0.3,0.1

Type RM Length L Ch R = 1 ,28604   ,2038,2038,2038
XS GIS Cut Line= 2
     3596142.023    10227165.451     3592131.606    10228671.527
#Sta/Elev= 30
       0  252.04   89.95  250.02  229.87  254.43   359.8   251.8  409.77  253.11
  459.74  251.09  509.71  245.08  539.69   237.5  559.68  227.39  579.67  212.42
  589.67  205.83  599.66  203.78  609.66  205.86  619.65  210.28  629.64  212.87
  639.64  213.18 1349.24  212.95 1429.19   210.1 1489.16  210.24 1509.15  212.36
 1549.12  213.13  1948.9  210.71 3198.19  210.75 3238.17  211.87 3298.13  216.02
 3508.02  236.06 3567.98  239.12 3947.77  234.78 4227.61   240.3 4307.56  239.73
#Mann= 4 ,-1 , 0
       0     .16       0  579.67     .07       0  639.64     .05       0
 1349.24     .05       0
Bank Sta=579.67,629.64
XS Rating Curve= 0 ,0
Exp/Cntr=0.3,0.1

Type RM Length L Ch R = 1 ,26566   ,1081,1081,1081
BEGIN DESCRIPTION:
WICKSON CREEK 14.0
END DESCRIPTION:
XS GIS Cut Line= 4
      3596487.98     10225420.04      3594342.11     10226279.43
      3592592.11     10227800.26      3591837.24     10228706.36
#Sta/Elev= 30
  1954.3  240.63  2022.9   224.2  2219.3  220.99  2356.3  214.11  2460.3  209.85
  2556.9  209.81  2568.3  209.81  2676.4  209.88  2752.2  214.59  2830.3  209.15
  3269.4  209.15  4947.9  212.51  4968.8  211.42  4994.3  201.03    4997  200.53
  5000.3  201.03    5040  209.93  5111.3  210.63  5253.1  211.02  5287.8  207.38
  5302.1  210.74  6486.2  215.29  6656.2  217.72  7025.4  229.75  7231.6  233.24
  7387.8  227.77  7422.9  232.25  7465.9  229.93    7501   234.5  7763.7  240.74
#Mann= 12 ,-1 , 0
  1954.3     .05       0  2356.3      .1       0  2460.3     .05       0
  2556.9     .07       0  2568.3     .05       0  2676.4     .07       0
  3269.4     .05       0  4994.3     .07       0  5000.3     .16       0
  5111.3     .16       0  5253.1     .05       0  7025.4     .16       0
Bank Sta=4947.9,5040
XS Rating Curve= 0 ,0
Exp/Cntr=0.3,0.1

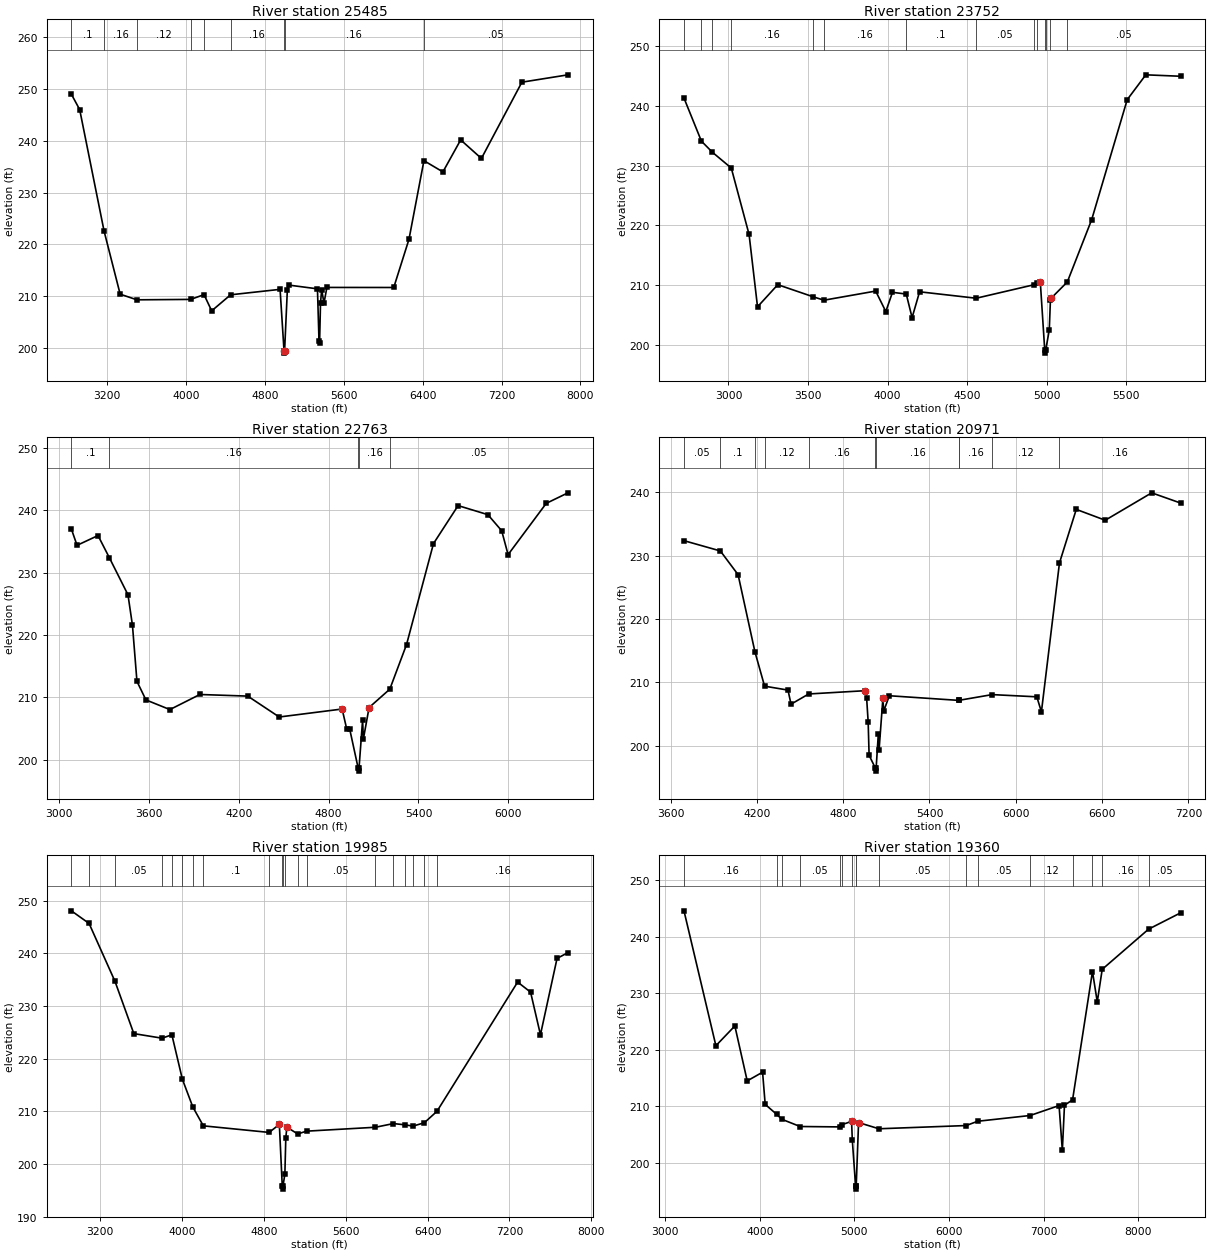
Type RM Length L Ch R = 1 ,25485   ,1733,1733,1733
BEGIN DESCRIPTION:
WICKSON CREEK 13.0
END DESCRIPTION:
XS GIS Cut Line= 3
      3595571.31     10224914.83      3592508.78     10226711.72
      3591025.28     10226785.69
#Sta/Elev= 30
  2837.9     249  2922.2  246.03  3169.5  222.59  3332.6   210.4  3503.2  209.31
  4047.4  209.39  4183.3  210.31  4260.8  207.18  4452.7  210.28  4954.4  211.33
  4994.3  199.52  4997.1  199.02  5000.3  199.52  5028.3   211.3  5040.3  212.16
  5333.4  211.43  5349.1  201.44  5354.9  201.01  5364.5  208.73  5376.4  211.29
  5399.3  208.66  5429.2   211.7  6107.2  211.69  6261.6     221  6413.2  236.17
  6605.6     234  6785.8  240.18  6996.1   236.6  7406.6  251.32    7874  252.74
#Mann= 9 ,-1 , 0
  2837.9      .1       0  3169.5     .16       0  3503.2     .12       0
  4047.4     .16       0  4183.3     .12       0  4452.7     .16       0
  4994.3     .07       0  5000.3     .16       0  6413.2     .05       0
Bank Sta=4994.3,5000.3
XS Rating Curve= 0 ,0
Exp/Cntr=0.3,0.1

Type RM Length L Ch R = 1 ,23752   ,989,989,989
BEGIN DESCRIPTION:
WICKSON CREEK 11.0
END DESCRIPTION:
XS GIS Cut Line= 2
      3594857.72     10224185.69      3591916.02      10225232.2
#Sta/Elev= 30
  2720.1  241.35  2829.6  234.13  2898.5  232.27  3017.6  229.62  3129.4  218.49
  3182.5  206.36  3309.8  210.07  3531.7  208.05  3600.2  207.47  3925.4     209
  3989.1  205.57    4031  208.79  4117.6   208.5  4154.3  204.55  4201.4  208.88
  4557.3   207.8  4917.7  210.04  4941.6  210.37  4960.4  210.54  4988.3   199.1
    4991   198.6  4994.3   199.1  5016.8  202.47    5024  207.44  5029.3  207.82
  5130.3  210.53  5283.7  220.99  5506.9  241.08  5623.7  245.24  5842.4     245
#Mann= 14 ,-1 , 0
  2720.1      .1       0  2829.6     .16       0  2898.5      .1       0
  3017.6     .16       0  3531.7     .05       0  3600.2     .16       0
  4117.6      .1       0  4557.3     .05       0  4917.7     .16       0
  4941.6     .12       0  4988.3     .07       0  4994.3     .12       0
    5024     .16       0  5130.3     .05       0
Bank Sta=4960.4,5029.3
XS Rating Curve= 0 ,0
Exp/Cntr=0.3,0.1

Type RM Length L Ch R = 1 ,22763   ,1792,1792,1792
BEGIN DESCRIPTION:
WICKSON CREEK 10.0
END DESCRIPTION:
XS GIS Cut Line= 3
      3594789.99     10224164.85      3592342.11     10224091.64
      3591779.61     10224753.39
#Sta/Elev= 30
  3081.2  237.02  3119.1   234.4  3259.2  235.97  3335.7  232.38  3459.3  226.47
  3489.3  221.57  3519.3  212.58  3579.3  209.61  3739.4  208.06  3939.5  210.48
  4259.6  210.22  4469.7  206.87  4889.9  208.15  4919.9  205.01  4939.9     205
  4996.9  198.69  4999.7  198.19  5002.9  198.69  5026.7  206.41  5031.7  203.32
    5070  208.39  5208.3  211.33  5320.1  218.48  5500.2  234.68  5664.7  240.77
  5863.5  239.32  5955.8  236.74  5998.6  232.91  6253.4  241.13  6398.7  242.82
#Mann= 5 ,-1 , 0
  3081.2      .1       0  3335.7     .16       0  4996.9     .07       0
  5002.9     .16       0  5208.3     .05       0
Bank Sta=4889.9,5070
XS Rating Curve= 0 ,0
Exp/Cntr=0.3,0.1

Type RM Length L Ch R = 1 ,20971   ,986,986,986
BEGIN DESCRIPTION:
WICKSON CREEK 9.0
END DESCRIPTION:
XS GIS Cut Line= 3
      3594659.85     10223664.86      3592159.82     10222852.35
      3591342.13      10222951.3
#Sta/Elev= 30
  3693.4  232.34  3946.3  230.72  4069.6  226.98  4186.5  214.84  4253.8  209.41
  4416.6  208.79  4437.6  206.57  4560.4  208.18  4948.5  208.69  4963.3  207.51
  4973.8  203.79  4980.4  198.52  5023.4  196.52  5026.2  196.02  5029.4  196.52
  5044.3  201.82  5049.6  199.34  5076.3  207.51  5081.5  205.47    5121   207.9
  5602.8  207.17  5603.1  207.17  5835.9  208.08  6146.4  207.73  6178.3  205.36
  6303.8  228.83  6420.6  237.27    6622  235.56    6945  239.88  7145.8  238.27
#Mann= 11 ,-1 , 0
  3693.4     .05       0  3946.3      .1       0  4186.5     .16       0
  4253.8     .12       0  4560.4     .16       0  5023.4     .07       0
  5029.4     .16       0  5602.8     .12       0  5603.1     .16       0
  5835.9     .12       0  6303.8     .16       0
Bank Sta=4948.5,5076.3
XS Rating Curve= 0 ,0
Exp/Cntr=0.3,0.1

Type RM Length L Ch R = 1 ,19985   ,625,625,625
BEGIN DESCRIPTION:
WICKSON CREEK 8.0
END DESCRIPTION:
XS GIS Cut Line= 4
      3595162.88     10223521.66      3594720.15     10222727.36
      3592454.53      10221998.2      3591074.32     10222727.36
#Sta/Elev= 30
  2921.5  248.06  3094.3  245.67  3347.6  234.67  3531.5  224.76  3807.7  223.89
    3903  224.54  4005.5  216.11  4107.9  210.83  4210.3  207.26  4853.1  206.01
  4952.9  207.53  4981.4  195.75  4984.1  195.25  4987.4  195.75  5006.7  198.07
  5015.9  204.98  5026.4  207.01    5132  205.72  5218.4  206.25  5890.8  206.99
  6067.3  207.69  6175.9  207.46    6258  207.21  6368.4  207.84  6492.1  210.01
  7280.2  234.54  7406.6  232.63    7503  224.55  7665.1  239.03  7771.9  240.13
#Mann= 20 ,-1 , 0
  2921.5      .1       0  3094.3      .1       0  3347.6     .05       0
  3807.7     .16       0    3903     .05       0  4005.5      .1       0
  4107.9     .16       0  4210.3      .1       0  4853.1     .12       0
  4981.4     .07       0  4987.4     .12       0  5006.7     .16       0
    5132      .1       0  5218.4     .05       0  5890.8     .12       0
  6067.3     .16       0  6175.9     .05       0    6258     .16       0
  6368.4     .12       0  6492.1     .16       0
Bank Sta=4952.9,5026.4
XS Rating Curve= 0 ,0
Exp/Cntr=0.3,0.1

Type RM Length L Ch R = 1 ,19360   ,905,905,905
BEGIN DESCRIPTION:
Mapping XS 0d9a8824
END DESCRIPTION:
XS GIS Cut Line= 3
      3595543.21     10222929.54      3591738.38     10220826.32
      3591283.11     10220045.85
#Sta/Elev= 30
  3198.2   244.6  3535.7  220.71  3736.2  224.21  3866.8  214.48  4029.4  216.02
  4056.9  210.32  4180.2  208.53  4231.7  207.69  4426.2   206.4  4843.9  206.33
  4867.8  206.72  4970.5  207.31  4978.2  203.96  5013.2  195.81    5016  195.31
  5019.2  195.81  5044.3   207.1  5259.6     206  6182.3  206.57  6303.1  207.33
  6858.3  208.35  7164.3  210.11  7198.9  202.16  7221.5  210.16  7307.1  211.13
  7517.5  233.85  7568.2  228.47  7620.5  234.24  8110.5  241.35  8449.2  244.24
#Mann= 17 ,-1 , 0
  3198.2     .16       0  4180.2     .05       0  4231.7     .16       0
  4426.2     .05       0  4843.9      .1       0  4867.8     .16       0
  4978.2     .12       0  5013.2     .07       0  5019.2     .12       0
  5259.6     .05       0  6182.3     .16       0  6303.1     .05       0
  6858.3     .12       0  7307.1     .16       0  7517.5     .05       0
  7620.5     .16       0  8110.5     .05       0
Bank Sta=4970.5,5044.3
XS Rating Curve= 0 ,0
Exp/Cntr=0.3,0.1

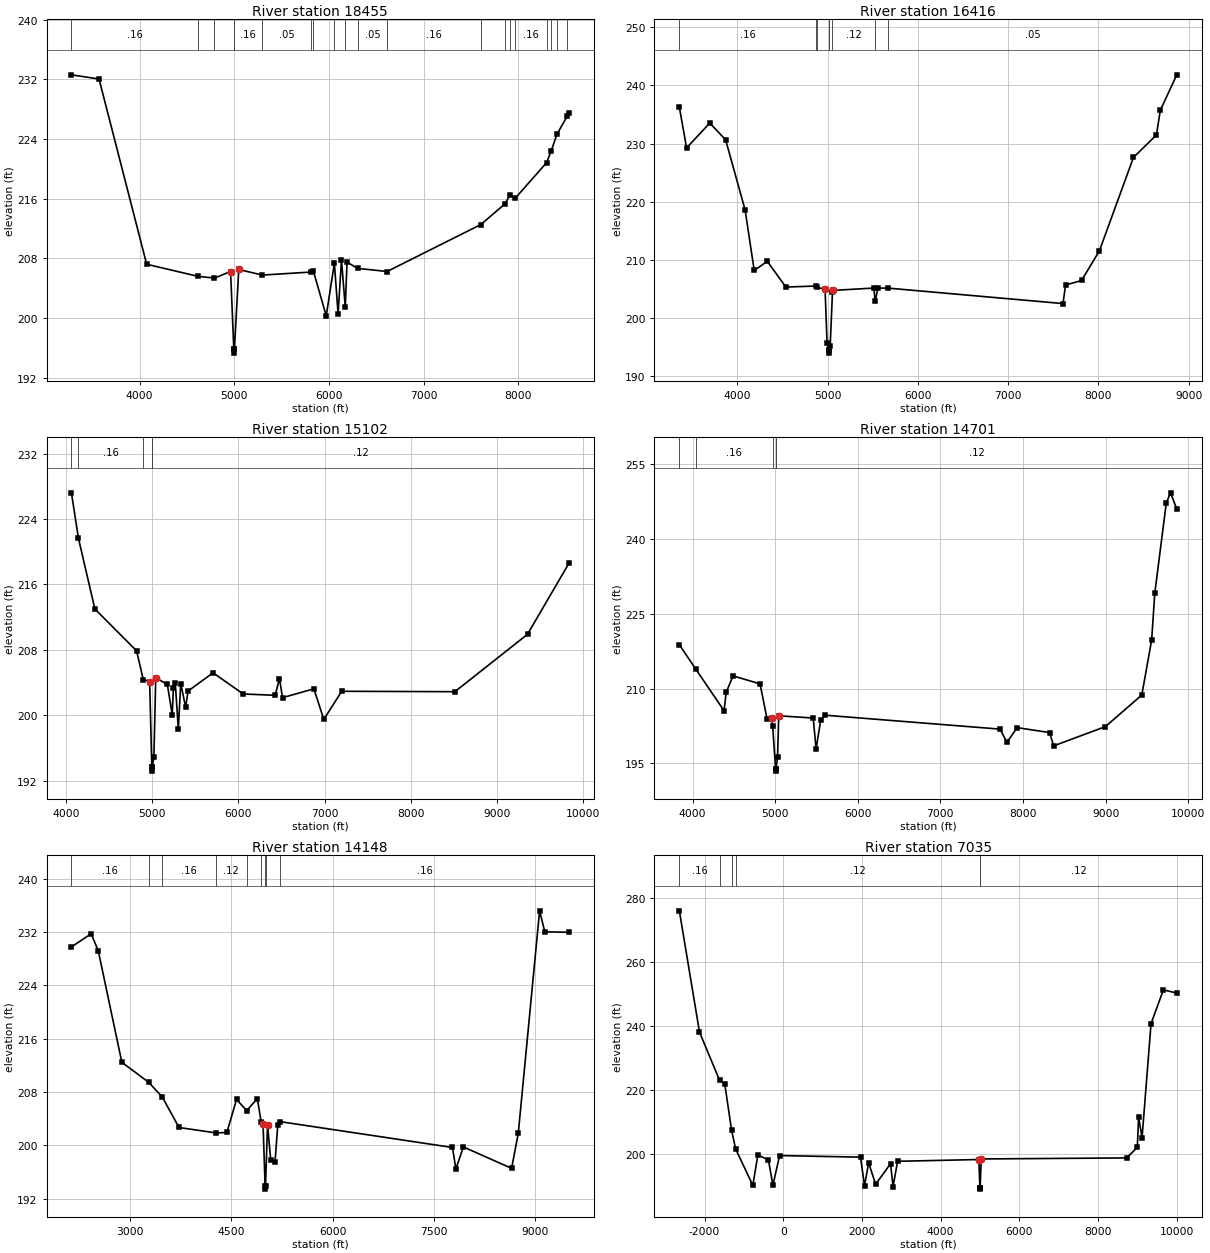
Type RM Length L Ch R = 1 ,18455   ,2039,2039,2039
BEGIN DESCRIPTION:
Mapping XS b46b449f
END DESCRIPTION:
XS GIS Cut Line= 4
      3595495.04     10222662.08      3595434.27     10221985.02
      3592561.01     10220335.71      3592040.18     10219189.89
#Sta/Elev= 30
  3281.1  232.59  3572.7  232.03  4075.5   207.2  4614.7  205.59  4791.3  205.35
  4961.4  206.23  4995.7  195.79  4998.5  195.29  5001.7  195.79  5047.7   206.5
  5296.7  205.75  5813.6  206.16  5836.7  206.24  5970.9  200.29  6057.1  207.34
  6096.5  200.53  6131.9  207.78    6172   201.5  6190.9  207.49  6301.9  206.65
  6613.5  206.23  7602.7  212.52  7858.6   215.3  7906.8  216.42  7968.5  216.08
  8298.2  220.83    8346   222.4  8408.1  224.66    8518  227.11  8532.5  227.45
#Mann= 20 ,-1 , 0
  3281.1     .16       0  4614.7      .1       0  4791.3     .16       0
  4995.7     .07       0  5001.7     .16       0  5296.7     .05       0
  5813.6      .1       0  5836.7     .16       0  6057.1     .12       0
    6172     .16       0  6301.9     .05       0  6613.5     .16       0
  7602.7     .05       0  7858.6     .16       0  7906.8     .05       0
  7968.5     .16       0  8298.2     .05       0    8346      .1       0
  8408.1     .05       0    8518      .1       0
Bank Sta=4961.4,5047.7
XS Rating Curve= 0 ,0
Exp/Cntr=0.3,0.1

Type RM Length L Ch R = 1 ,16416   ,1314,1314,1314
BEGIN DESCRIPTION:
Mapping XS c7a4849f
END DESCRIPTION:
XS GIS Cut Line= 4
      3595954.33     10222341.24      3595878.38     10221657.68
      3594793.31     10219520.09      3592959.98     10217936.27
#Sta/Elev= 30
  3359.2  236.24  3439.3  229.25  3696.1  233.51  3871.9  230.63  4087.4  218.56
  4188.3  208.16  4332.7  209.74  4538.7  205.31  4869.5  205.49    4886  205.25
  4972.7  204.95    4995  195.61  5014.2  194.45    5017  193.95  5020.2  194.45
  5029.4  195.19  5054.6  204.45  5061.7  204.74  5512.6  205.14  5527.4  202.84
  5557.1  205.13  5671.5  205.13    7607  202.47  7635.1  205.66  7812.2  206.44
  8010.7  211.56  8386.9   227.6  8641.5  231.47  8684.2  235.69  8866.9  241.81
#Mann= 8 ,-1 , 0
  3359.2     .16       0  4869.5     .12       0    4886     .16       0
  5014.2     .07       0  5020.2     .16       0  5054.6     .12       0
  5527.4     .16       0  5671.5     .05       0
Bank Sta=4972.7,5061.7
XS Rating Curve= 0 ,0
Exp/Cntr=0.3,0.1

Type RM Length L Ch R = 1 ,15102   ,401,401,401
BEGIN DESCRIPTION:
WICKSON CREEK 6.0
END DESCRIPTION:
XS GIS Cut Line= 4
      3596545.93     10221303.62      3596519.89     10220548.39
      3595860.16     10219901.68      3593388.67     10216642.89
#Sta/Elev= 30
  4064.4   227.2  4146.2  221.63  4336.5     213  4820.1  207.89  4897.8  204.38
  4971.7  204.13    4997  193.68  4999.8  193.18    5003  193.68  5021.3  194.96
  5042.4   204.6  5176.9  203.77  5233.5   200.1  5247.6  203.32  5268.7  204.01
  5304.2  198.33  5332.5  203.89    5389  200.99  5417.3  202.97  5707.2   205.2
  6057.4  202.61  6427.7  202.45  6477.6  204.49    6513  202.16    6877  203.24
  6991.4   199.5  7199.4  202.94    8512  202.89  9354.4  209.91  9833.9  218.57
#Mann= 5 ,-1 , 0
  4064.4     .05       0  4146.2     .16       0  4897.8     .12       0
    4997     .07       0    5003     .12       0
Bank Sta=4971.7,5042.4
XS Rating Curve= 0 ,0
Exp/Cntr=0.3,0.1

Type RM Length L Ch R = 1 ,14701   ,553,553,553
BEGIN DESCRIPTION:
WICKSON CREEK 5.0
END DESCRIPTION:
XS GIS Cut Line= 4
      3596641.41     10221247.17      3596854.09     10220383.46
      3596007.73     10219502.38      3594130.89     10216070.04
#Sta/Elev= 30
  3839.1  218.82  4036.1  213.96  4380.3  205.57  4406.4  209.26  4489.4  212.56
  4816.1  210.96    4901  203.96  4957.6  204.04  4968.7  202.54  5004.2  193.94
    5007  193.44  5010.2  193.94  5028.3  196.37  5042.5  204.55  5459.8   204.1
    5495   197.9  5551.6  203.79  5608.2  204.66  7723.4  201.87    7805  199.22
  7930.2  202.17  8321.8  201.18  8371.3  198.51  8997.4  202.37  9438.8  208.72
    9558  219.77  9595.9  229.18  9735.1  247.28  9786.6  249.31  9862.3  246.04
#Mann= 5 ,-1 , 0
  3839.1     .05       0  4036.1     .16       0  4968.7     .12       0
  5004.2     .07       0  5010.2     .12       0
Bank Sta=4957.6,5042.5
XS Rating Curve= 0 ,0
Exp/Cntr=0.3,0.1

Type RM Length L Ch R = 1 ,14148   ,7113,7113,7113
BEGIN DESCRIPTION:
WICKSON CREEK 4.0
END DESCRIPTION:
XS GIS Cut Line= 2
      3597708.54      10222541.6       3595625.2     10215479.06
#Sta/Elev= 30
  2132.6  229.79  2425.1  231.75  2530.2   229.2    2879  212.47  3276.1  209.46
  3476.3  207.28  3725.3  202.68  4272.2  201.87  4433.3  201.93  4576.9  206.89
  4727.5  205.21    4885  207.02    4941  203.53  4969.4  203.15  4999.7  193.93
  5002.5  193.43  5005.7  193.93    5036  203.09  5083.1  197.76  5146.4  197.48
  5187.4  203.07  5226.6  203.55    7773  199.68    7824  196.45  7934.4  199.76
  8648.8  196.55  8747.4  201.83  9062.9   235.2  9139.9  232.05    9496  231.98
#Mann= 9 ,-1 , 0
  2132.6     .16       0  3276.1     .05       0  3476.3     .16       0
  4272.2     .12       0  4727.5     .16       0    4941     .12       0
  4999.7     .07       0  5005.7     .12       0  5226.6     .16       0
Bank Sta=4969.4,5036
XS Rating Curve= 0 ,0
Exp/Cntr=0.3,0.1

Type RM Length L Ch R = 1 ,7035    ,0,0,0
BEGIN DESCRIPTION:
WICKSON CREEK 1.0
END DESCRIPTION:
XS GIS Cut Line= 2
      3607233.36     10218945.67      3595219.43     10215022.05
#Sta/Elev= 30
 -2639.3  275.94 -2127.4  238.05   -1619  223.03 -1484.5  221.76 -1311.4   207.3
 -1208.9  201.52  -772.5  190.15  -644.9  199.63  -376.2  198.12  -262.3  190.18
   -92.2  199.46  1964.1  198.96    2065  189.99  2169.6  197.22  2346.7  190.48
  2727.1  196.91  2790.2  189.77  2905.9  197.67 4971.26  198.22  4996.4  189.47
  4999.1  188.97  5002.4  189.47  5030.9   198.4  8728.4  198.72  8996.9  202.04
  9028.5  211.52  9116.2     205  9344.7  240.67  9658.3  251.25  9999.1  250.23
#Mann= 6 ,-1 , 0
 -2639.3     .16       0   -1619      .1       0 -1311.4     .16       0
 -1208.9     .12       0  4996.4     .07       0  5002.4     .12       0
Bank Sta=4971.26,5030.9
XS Rating Curve= 0 ,0
Exp/Cntr=0.3,0.1

Chan Stop Cuts=-1
Use User Specified Reach Order=0
Composite Channel Slope=5